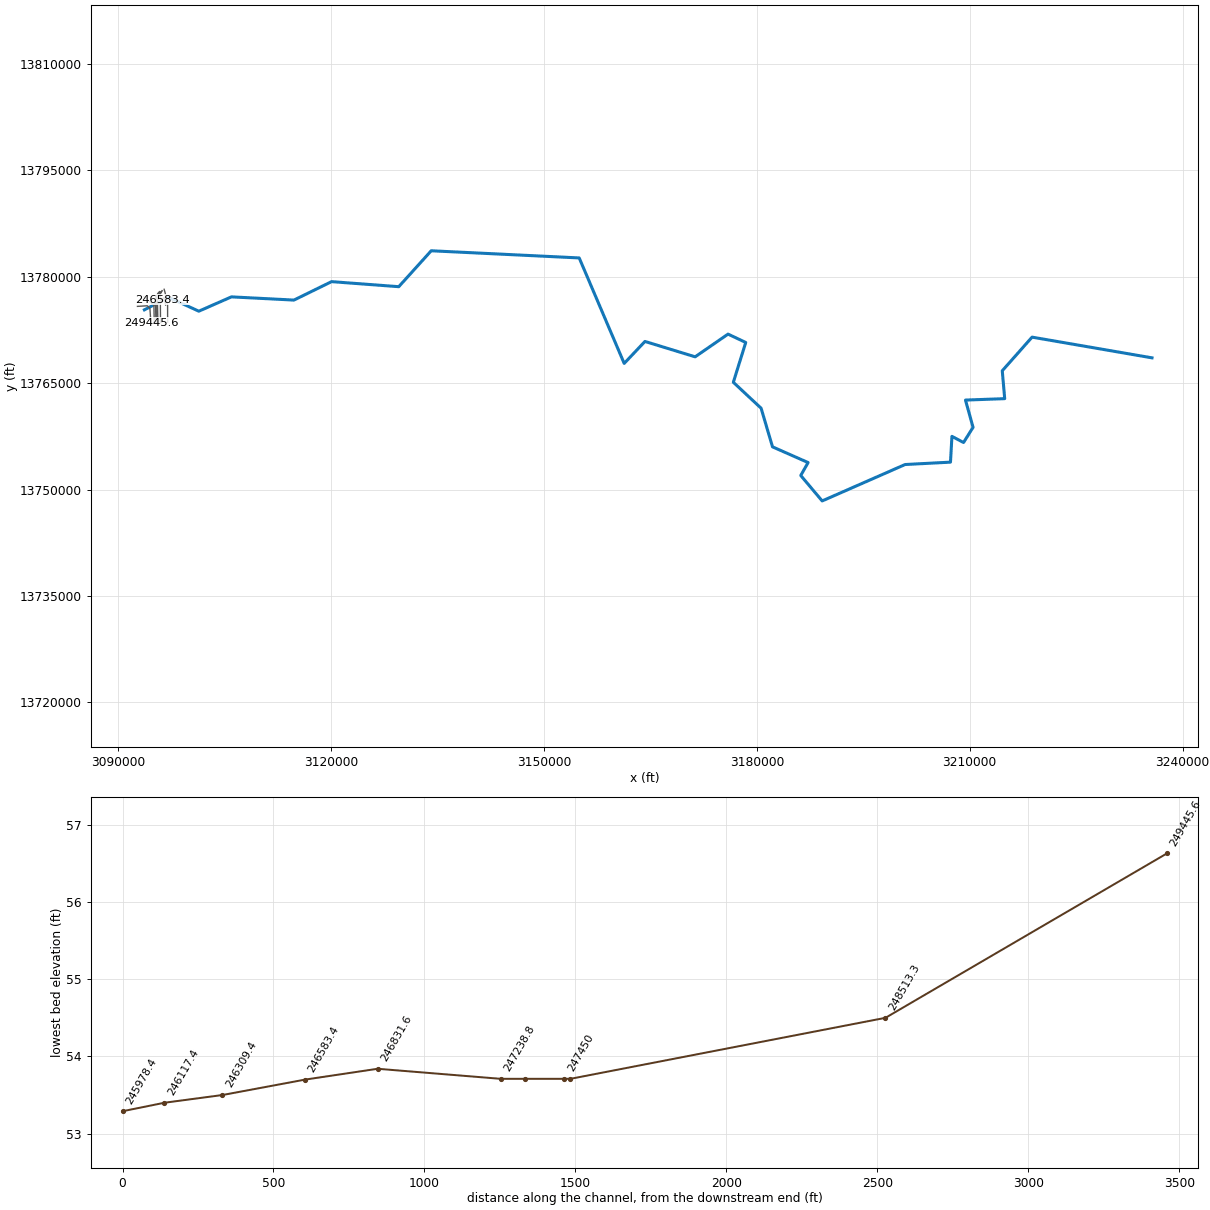
--- A100-00-00.prj (project) ---

Proj Title=A100-00-00
Current Plan=p02
Default Exp/Contr=.3,.1
English Units
Geom File=g01
Flow File=f01
Flow File=f02
Plan File=p01
Plan File=p02
Y Axis Title=Elevation
X Axis Title(PF)=Main Channel Distance
X Axis Title(XS)=Station
BEGIN DESCRIPTION:
 HCFCD Watershed Unit ID: A
M3 Study Identifier: 2007_Effective_A
Engineer: HCFCD
Project Name: EffectiveFEMA Study for watershed Clear Creek (A)
Study Completion Date: 6/18/2007
FEMA Case Number: [No Data]
FEMA Approval Date: [No Date in Database]
Vertical Datum: NAVD 1988
Datum Note: 2001 ADJ
HYDRAULICS
HCFCD Unit No.:  A100-00-00
Hydraulic Program Name: HEC-RAS
Hydraulic Program Version: 3.0.1
Steady Hydraulic Model: Yes
Unsteady Hydraulic Model: No
Update1:
The effective FEMA hydraulic model for unit number A100-00-00 has been updated by FEMA LOMR 09-06-1180P with an effective date of 5/28/2009.
Update2:
The effective FEMA hydraulic model for unit number A100-00-00 has been updated by FEMA LOMR 08-06-0819P with an effective date of 10/29/2009.
Update3:
The effective FEMA hydraulic model for unit number A100-00-00 has been updated by FEMA LOMR 12-06-1209P with an effective date of 11/08/2012.
Update4:
The effective FEMA hydraulic model for unit number A100-00-00 has been updated by FEMA LOMR 13-06-1986P with an effective date of 11/14/2013.
Update5:
The effective FEMA hydraulic model for unit number A100-00-00 has been updated by FEMA LOMR 13-06-1908P with an effective date of 2/6/2014.
Update6:
The effective FEMA hydraulic model for unit number A100-00-00 has been updated by FEMA LOMR 13-06-1076P with an effective date of 3/6/2014.
Update7:
The effective FEMA hydraulic model for unit number A100-00-00 has been updated by FEMA LOMR 14-06-3038P with an effective date of 12/26/2014.
Update8:
This update includes a LOMR that the previous update did not include. The model for unit number A100-00-00 has an effective date of 12/26/2014.
Update9:
The effective FEMA hydraulic model for unit number A100-00-00 has been updated by FEMA LOMR 19-06-2864P with an effective date of XX/XX/2020.
END DESCRIPTION:
DSS File=dss
DSS Export Rating Curves= 0
DSS Export Rating Curve Sorted= 0
DSS Export Volume Flow Curves= 0
DXF OffsetX= 0
DXF OffsetY= 0
DXF ScaleX= 1
DXF ScaleY= 10

--- A100-00-00.p02 (plan) ---

Plan Title=Effective Floodway 2020
Program Version=5.07
Short Identifier=Effective FW 2020
Geom File=g01
Flow File=f02
Subcritical Flow
K Sum by GR= 0
Std Step Tol= 0.01
Critical Tol= 0.01
Num of Std Step Trials= 20
Max Error Tol= 0.3
Flow Tol Ratio= 0.001
Split Flow NTrial= 30
Split Flow Tol= 0.02
Split Flow Ratio= 0.02
Log Output Level= 0
Friction Slope Method= 1
Unsteady Friction Slope Method= 2
Unsteady Bridges Friction Slope Method= 1
Parabolic Critical Depth
Global Vel Dist= 0 , 0 , 0
Global Log Level= 0
CheckData=True
Encroach Param=-1 ,0,0, 2
Encroach River=A100-00-00
Encroach Reach=A100-00-00_0000
Encroach Node=249445.6
       1    4800    5100
Encroach Node=248513.3
       1 4911.58 5028.99
Encroach Node=247470.2
       1  4927.7 5034.88
Encroach Node=247450
       1  4937.7 5041.49
Encroach Node=247318.8
       1  4922.7 5026.49
Encroach Node=247238.8
       1  4922.7 5026.49
Encroach Node=246831.6
       1 4904.06  5057.4
Encroach Node=246583.4
       1    4956    5045
Encroach Node=246309.4
       1    4947    5044
Encroach Node=246117.4
       1    4945    5041
Encroach Node=245978.4
       1    4745    5233
Encroach Node=244940.7
       1    4746    5227
Encroach Node=243897.7
       1 4737.48    5244
Encroach Node=243191.7
       1    4700 5162.87
Encroach Node=243088.7
       1    4277    4749
Encroach Node=242938.7
       1    4268    4740
Encroach Node=242837.9
       1  4903.3    5244
Encroach Node=242220.2
       1 4915.79    5248
Encroach Node=241521
       1    4750    5234
Encroach Node=240179.8
       1 4705.47    5215
Encroach Node=240152
       1    4750    5205
Encroach Node=240008.4
       1 4955.03 5010.54
Encroach Node=239967.4
       1  4962.1 5042.54
Encroach Node=239844.7
       1 4887.45 5038.11
Encroach Node=239715.9
       1 4828.03 5048.53
Encroach Node=239432.8
       1 4958.93 5026.97
Encroach Node=238465.7
       1 4942.63  5086.6
Encroach Node=238434.6
       1 4937.63 5030.92
Encroach Node=238300.5
       1 4927.63 5020.92
Encroach Node=238168.1
       1    4763    5240
Encroach Node=237689.3
       1    4550    5400
Encroach Node=236608.9
       1    2412    3174
Encroach Node=235828.2
       1    2737    3853
Encroach Node=235070.7
       1    2959    4337
Encroach Node=234461.3
       1  3036.5    4574
Encroach Node=234420.7
       1    3164    4600
Encroach Node=233734.5
       1    3267    4700
Encroach Node=232999.9
       1 3205.18    4735
Encroach Node=232232.1
       1 2994.23 4424.07
Encroach Node=231533.3
       1 2725.89    4347
Encroach Node=230878.1
       1 2592.68 4257.47
Encroach Node=230159.2
       1    2961    4745
Encroach Node=229428.1
       1    3182    4912
Encroach Node=229112.0
       1 4110.35 5407.67
Encroach Node=229073.3
       1 4120.53 5375.74
Encroach Node=228828.4
       1 4201.94 5293.76
Encroach Node=228792.0
       1 4358.87 5436.85
Encroach Node=228044.5
       1    5151    6758
Encroach Node=227358.8
       1    5415    7229
Encroach Node=226430.5
       1    5800    7631
Encroach Node=225542.2
       1 6207.84    7397
Encroach Node=225035.7
       1 6234.62    7279
Encroach Node=224533.
       1 4558.89 5404.16
Encroach Node=224031.4
       1 7032.65    7600
Encroach Node=223668.1
       1 7483.58  7727.1
Encroach Node=223445.1
       1 7840.55    8043
Encroach Node=222868.7
       1    7527    8184
Encroach Node=222149.2
       1    7423    8258
Encroach Node=221401.5
       1    6954    8686
Encroach Node=220697.2
       1 6877.25 8448.01
Encroach Node=219890.1
       1    7197    8681
Encroach Node=219197.5
       1    8500   10085
Encroach Node=218474.0
       1 7904.93 9943.78
Encroach Node=217869.1
       1  7199.7 9963.01
Encroach Node=216969.0
       1 7086.8410097.85
Encroach Node=216257.9
       1 7026.08  9730.2
Encroach Node=215408.2
       1    7135 9396.55
Encroach Node=214705.8
       1 7143.97 9608.54
Encroach Node=213801.7
       1    7628 9468.54
Encroach Node=213290.6
       1 7806.96 9186.69
Encroach Node=212735.5
       1 7759.44 8947.97
Encroach Node=212049.2
       1    7681 9242.06
Encroach Node=211277.7
       1    7277    9638
Encroach Node=211227.4
       1    7277    9638
Encroach Node=210409.0
       1    7160 9181.24
Encroach Node=209667.7
       1    7218    9332
Encroach Node=208585.5
       1    6997    9174
Encroach Node=207766.7
       1    6807    9155
Encroach Node=207043.7
       1    6139    8362
Encroach Node=206058.0
       1    5109    7319
Encroach Node=205915.5
       1    4522    6824
Encroach Node=205888.3
       1    4450    6800
Encroach Node=205249.9
       1    4351    6151
Encroach Node=204504.6
       1    4435    6031
Encroach Node=203730.2
       1 4129.19 5536.35
Encroach Node=202849.1
       1 4327.33 5964.05
Encroach Node=202121.9
       1 4245.45 6387.76
Encroach Node=201418.5
       1    3778    6242
Encroach Node=200707.1
       1    4132    6390
Encroach Node=199968.0
       1    4480    6845
Encroach Node=199334.1
       1 4776.59    6625
Encroach Node=198574.5
       1    5401    6772
Encroach Node=197996.2
       1    5391    6793
Encroach Node=197191.3
       1    5159    7349
Encroach Node=196544.9
       1    5383    7304
Encroach Node=195885.8
       1    5130    7252
Encroach Node=195225.4
       1    5042    7023
Encroach Node=194562.3
       1    5693    7134
Encroach Node=193683.1
       1 7938.24 9313.73
Encroach Node=192943.9
       1    7767    9778
Encroach Node=191949.2
       1    8174    9667
Encroach Node=191313.0
       1    8032    9599
Encroach Node=190633.6
       1    8063    9248
Encroach Node=189991.2
       1    8278    9166
Encroach Node=189525.6
       1    8977    9259
Encroach Node=189432.4
       1    9054    9319
Encroach Node=189401.7
       1    9185 9298.28
Encroach Node=189373.4
       1 9312.24 9405.66
Encroach Node=188789.9
       1    9100   10100
Encroach Node=188162.9
       1    8238    9021
Encroach Node=187534.8
       1    9621   10387
Encroach Node=186897.6
       1    9100   10050
Encroach Node=186299.8
       1    8493    9377
Encroach Node=185606.0
       1    8000    9613
Encroach Node=185547.5
       1    7937    9613
Encroach Node=184837.1
       1    7626   10030
Encroach Node=184168.8
       1    7532   10020
Encroach Node=183604.5
       1    7492   10242
Encroach Node=183041.6
       1    7691   10216
Encroach Node=182508.8
       1    7601   10002
Encroach Node=181536.1
       1    7544 9771.69
Encroach Node=180697.6
       1    7842    9660
Encroach Node=179876.8
       1 8381.96 9684.73
Encroach Node=179278.5
       1 9313.28   10877
Encroach Node=178638.8
       1 10235.211806.67
Encroach Node=178408.8
       110155.71   11689
Encroach Node=177942.3
       1 6016.42 7420.76
Encroach Node=177527.3
       1  6387.3  7077.5
Encroach Node=177504.3
       1  6387.3  7077.5
Encroach Node=177454.3
       1  6387.3  7077.5
Encroach Node=177404.3
       1  6387.3  7077.5
Encroach Node=177381.3
       1  6387.3  7077.5
Encroach Node=176737.7
       1 5981.63 6725.42
Encroach Node=175962.3
       1 5355.75 7036.37
Encroach Node=175051.0
       1    3234 5557.05
Encroach Node=174558.5
       1    3427 5377.26
Encroach Node=173895.4
       1 3960.88 5679.09
Encroach Node=173103.5
       1 4645.09 6112.04
Encroach Node=172458.4
       1    4726    6421
Encroach Node=171705.5
       1    4000 6349.27
Encroach Node=170870.1
       1    4000 6805.32
Encroach Node=170732.7
       1    4500  6932.7
Encroach Node=170703.4
       1    4500    6900
Encroach Node=170247.8
       1    4800 6698.08
Encroach Node=169549.2
       1    5094    6765
Encroach Node=168792.3
       1 5472.06  6733.1
Encroach Node=168066.6
       1 5575.14 6366.35
Encroach Node=167576.9
       1  5425.7  5826.5
Encroach Node=167392.7
       1  5309.6  5656.9
Encroach Node=167264.8
       1  5318.7  5712.2
Encroach Node=167166.6
       1  5277.7  5670.3
Encroach Node=166625.9
       1 5541.37 6127.57
Encroach Node=165983.9
       1 5686.39 6212.39
Encroach Node=165236.1
       1 5230.24  6054.2
Encroach Node=164557.7
       1 5472.45 6292.24
Encroach Node=163802.3
       1 5797.32 6505.62
Encroach Node=163075.4
       1 5775.25 6516.52
Encroach Node=162398.3
       1 6208.07 6740.25
Encroach Node=161782.5
       1    6719    7273
Encroach Node=161060.4
       1 7202.28 7863.08
Encroach Node=160583.7
       1 7381.69 8227.54
Encroach Node=160421.2
       1 7435.08 8477.28
Encroach Node=160102.4
       1 7516.57 8292.33
Encroach Node=160052.5
       1 7467.41 8391.65
Encroach Node=159946.5
       1 7335.34    8000
Encroach Node=158714.0
       1    6862    7550
Encroach Node=158159.6
       1    6873    7782
Encroach Node=157136.7
       1    6784    7721
Encroach Node=156373.5
       1    6301    6980
Encroach Node=155812.6
       1 6108.48 6613.67
Encroach Node=155128.0
       1    5500    5972
Encroach Node=154437.2
       1    4377 5088.01
Encroach Node=153811.0
       1 2498.24 3818.01
Encroach Node=153192.6
       1    2026 2653.34
Encroach Node=152591.1
       1    1476    2531
Encroach Node=152196.2
       1 1359.94 2315.29
Encroach Node=152079.2
       1 1325.56 2251.38
Encroach Node=151871.2
       1    1285    2176
Encroach Node=151785.2
       1 1386.87 2277.16
Encroach Node=151242.6
       1  1741.2    2629
Encroach Node=150467.1
       1    1841    3116
Encroach Node=149741.7
       1    1847    2821
Encroach Node=148981.8
       1    1428    2583
Encroach Node=148395.9
       1    1433    1975
Encroach Node=147716.3
       1    1515    1958
Encroach Node=147046.0
       1 2913.61 3701.42
Encroach Node=146484.9
       1    3050 4226.86
Encroach Node=145837.0
       1    7387    8685
Encroach Node=144892.8
       1   10120   12039
Encroach Node=144315.3
       1    941210088.56
Encroach Node=143670.8
       1    955510229.27
Encroach Node=143428.5
       115056.84 15165.7
Encroach Node=143346.3
       1   1200015213.93
Encroach Node=141725.5
       1   11870   16208
Encroach Node=140561.5
       1   11790   16121
Encroach Node=139436.9
       1   1171015647.87
Encroach Node=138379.4
       1   11650   15258
Encroach Node=137393.2
       1    9218   14521
Encroach Node=137087.3
       1    9205   14383
Encroach Node=136801.7
       1    9160   14088
Encroach Node=136414.1
       1    9148   14091
Encroach Node=136231.7
       1    9124   13973
Encroach Node=135343.4
       1    9102   13990
Encroach Node=134986.0
       1    9002   13973
Encroach Node=133890.1
       1    8908   13983
Encroach Node=133559.2
       1    8891   13955
Encroach Node=132391.9
       1    8800   13861
Encroach Node=131741.5
       1    8675   13886
Encroach Node=131360.9
       1    8637   13878
Encroach Node=130901.7
       1    8592   14011
Encroach Node=130694.4
       1    8594   13869
Encroach Node=129920.7
       1    8573   13587
Encroach Node=129631.0
       1    8491   13592
Encroach Node=128562.0
       1    8446   13388
Encroach Node=127103.5
       18312.149   13139
Encroach Node=126994.4
       18422.273   12902
Encroach Node=126444.0
       1    8996   12622
Encroach Node=125781.7
       1    8540   12079
Encroach Node=124241.3
       1    8178   12283
Encroach Node=123196.7
       1    6085   10101
Encroach Node=122169.1
       1    3778    8084
Encroach Node=119200.8
       1    5106    8264
Encroach Node=119094.3
       1    5309    8464
Encroach Node=118697.3
       1    5530    8541
Encroach Node=117811.8
       1    5809    8165
Encroach Node=117443.4
       1    6183    8370
Encroach Node=117108.9
       1 6320.99 8312.46
Encroach Node=116862.8
       1 6700.96 8704.44
Encroach Node=116205.8
       1 7165.07 9138.08
Encroach Node=115845.9
       1    7559 9297.86
Encroach Node=115336.8
       1  7599.410156.78
Encroach Node=114846.9
       1 8131.97 9891.93
Encroach Node=114343.0
       1 8444.38 9567.73
Encroach Node=113771.2
       1 8378.44 9462.75
Encroach Node=113220.5
       1    8256    9880
Encroach Node=112796.0
       1    8241   10271
Encroach Node=112517.0
       1    7037    8922
Encroach Node=112393.5
       1    7127    9727
Encroach Node=112198.7
       1    2559    5596
Encroach Node=111295.8
       1    2562    5628
Encroach Node=110479.3
       1    2577    5594
Encroach Node=110033.0
       1    2588    5374
Encroach Node=109598.1
       1    2437    5113
Encroach Node=108588.6
       1    2151    4926
Encroach Node=107933.1
       1    2603    5119
Encroach Node=107243.0
       1    4352    6555
Encroach Node=106986.3
       1    6328    8270
Encroach Node=106343.5
       1    7417    8903
Encroach Node=105863.2
       1    6883    7771
Encroach Node=105183.9
       1    5465    7177
Encroach Node=104713.5
       1    4441    6138
Encroach Node=103329.9
       1    3086    5332
Encroach Node=103035.3
       1    3450    5164
Encroach Node=102354.7
       1    3578    5272
Encroach Node=101866.7
       1    3898    5264
Encroach Node=101082.9
       1    3684    5286
Encroach Node=100234.2
       1    3978    5350
Encroach Node=99799.69
       1    4204    5329
Encroach Node=99364.63
       1    4257    5355
Encroach Node=98306.72
       1    4258    5784
Encroach Node=97470.49
       1    4355    5889
Encroach Node=97180.24
       1    4417    6104
Encroach Node=96307.12
       1    4625    5975
Encroach Node=95781.87
       1    4625    5795
Encroach Node=95457.09
       1    4633    5783
Encroach Node=95406.35
       1    4612    5700
Encroach Node=94641.43
       1  4917.4 5651.62
Encroach Node=94111.47
       1    4985    6291
Encroach Node=93497.69
       1 5668.49 7069.65
Encroach Node=92709.32
       1    6100    7550
Encroach Node=92296.93
       1    6300    7700
Encroach Node=92000.23
       1    6600    8000
Encroach Node=91128.72
       1    7800    9600
Encroach Node=90216.02
       1    8700    9422
Encroach Node=90072.02
       1    8700    9615
Encroach Node=89784.58
       1 8252.02    9600
Encroach Node=89314.28
       1    8200    9645
Encroach Node=88917.60
       1    8050    9481
Encroach Node=88061.18
       1 7620.53  8703.9
Encroach Node=87585.76
       1 7306.04  8635.8
Encroach Node=87139.14
       1 6539.56  8619.3
Encroach Node=86715.28
       1  6171.4 8681.77
Encroach Node=86095.77
       1    6000    8507
Encroach Node=85656.10
       1    5800    8278
Encroach Node=85188.46
       1 5700.04 8115.64
Encroach Node=84787.06
       1    5900 8013.25
Encroach Node=83977.63
       1  6425.3    7900
Encroach Node=83496.46
       1  6275.2    8300
Encroach Node=82967.02
       1 6316.56 8799.62
Encroach Node=82338.22
       1 6246.16 8890.19
Encroach Node=81909.22
       1 5953.53 8693.78
Encroach Node=81354.43
       1 5786.73 8595.62
Encroach Node=80754.51
       1 5672.79 8307.37
Encroach Node=80330.40
       1 7268.63 8231.63
Encroach Node=79844.64
       1    7308    8307
Encroach Node=79318.73
       1 7156.48 8078.54
Encroach Node=78339.78
       1 6863.45 8373.78
Encroach Node=77642.36
       1    6649    7379
Encroach Node=77113.22
       1 6274.79    7200
Encroach Node=76553.81
       1 6158.17    7425
Encroach Node=74948.85
       1 5958.25 8061.33
Encroach Node=73997.74
       1    5864    8100
Encroach Node=73892.70
       1    5800    8034
Encroach Node=73438.09
       1    2188    3826
Encroach Node=72765.55
       1    2000    3200
Encroach Node=72158.00
       1 2044.67    2763
Encroach Node=71426.94
       1    1775    2752
Encroach Node=70698.11
       1    1800    2976
Encroach Node=70154.42
       1    1900 3048.33
Encroach Node=69288.24
       1    1700    3248
Encroach Node=68855.92
       1 2200.46 2865.42
Encroach Node=68350.94
       1 1951.04 2691.05
Encroach Node=67728.79
       1    1800 2750.37
Encroach Node=67105.73
       1 1838.27 2765.48
Encroach Node=66639.54
       1 1803.73 2607.64
Encroach Node=66278.07
       1 2738.72    3550
Encroach Node=65855.65
       1 2994.31 3901.07
Encroach Node=65278.99
       1 3024.04 4291.93
Encroach Node=64820.26
       1 2864.64 4054.88
Encroach Node=64342.25
       1 3535.68  4351.9
Encroach Node=63836.08
       1    3931    4552
Encroach Node=63388.22
       1    4500    5800
Encroach Node=62915.31
       1    4800    6300
Encroach Node=62430.47
       1    5492    6812
Encroach Node=61909.39
       1    5400 6865.25
Encroach Node=61501.83
       1 7336.72 8728.76
Encroach Node=61032.89
       1 7448.82  8354.1
Encroach Node=60519.12
       1 7178.89 8219.72
Encroach Node=60116.03
       1 7021.44 8046.61
Encroach Node=59615.46
       1    6900    8200
Encroach Node=59124.95
       1    7300    8100
Encroach Node=58716.18
       1 7322.59    8300
Encroach Node=58138.03
       1    7800    8800
Encroach Node=57696.46
       1 8365.32  9070.5
Encroach Node=57171.49
       1    8530 9292.37
Encroach Node=55860.57
       1 8729.14    9700
Encroach Node=55615.42
       1    8600    9400
Encroach Node=54910.52
       1    4800    6200
Encroach Node=54018.04
       1    3713    5100
Encroach Node=53599.25
       1 3793.74 5196.31
Encroach Node=53094.82
       1 5108.31 6151.63
Encroach Node=52493.20
       1 5467.17 6259.69
Encroach Node=51920.67
       1    5400 6798.02
Encroach Node=51508.69
       1    5200 6967.58
Encroach Node=51010.65
       1    5150    6844
Encroach Node=50212.01
       1    5131 6664.39
Encroach Node=49467.98
       1    4800    7000
Encroach Node=48780.15
       1    4228    5350
Encroach Node=48325.42
       1 3405.68 4247.18
Encroach Node=47709.01
       1 3032.88 4640.99
Encroach Node=47050.92
       1    3249    4896
Encroach Node=46388.40
       1 3249.89    5147
Encroach Node=46279.31
       1 3316.21    5168
Encroach Node=46239.39
       1 3349.85    5500
Encroach Node=46214.15
       1    3369    5547
Encroach Node=44075.74
       1 4496.12 5665.46
Encroach Node=43257.53
       1 4156.13 5413.28
Encroach Node=42651.33
       1 4621.04 5839.14
Encroach Node=42050.86
       1    4528    6312
Encroach Node=41420.54
       1 4316.99 5358.16
Encroach Node=41099.91
       1 3653.68 5253.97
Encroach Node=40310.46
       1 3497.36 5076.79
Encroach Node=39765.40
       1 3463.75 4512.19
Encroach Node=39372.55
       1    3537    5049
Encroach Node=38390.74
       1 2253.16 3742.16
Encroach Node=37273.21
       1    8860    9829
Encroach Node=37212.22
       1 8956.01 9887.37
Encroach Node=36556.81
       1    896010237.56
Encroach Node=35779.77
       1 9248.8910004.59
Encroach Node=34479.79
       1 4005.95 5126.94
Encroach Node=33866.14
       1    3494 4470.43
Encroach Node=33491.25
       1    3736    5243
Encroach Node=32502.26
       1 3869.04 5655.76
Encroach Node=31499.75
       1    4165    5516
Encroach Node=30794.12
       1    4045    6446
Encroach Node=30139.49
       1    3501 5872.26
Encroach Node=28989.75
       1    3504  5574.6
Encroach Node=27859.82
       1    2148 4712.65
Encroach Node=26873.54
       1 1763.69 4789.67
Encroach Node=25385.56
       1 1516.56 4377.39
Encroach Node=24490.10
       1 2367.68 5608.97
Encroach Node=23262.63
       1 3998.36 6175.31
Encroach Node=20859.46
       1 6210.7610258.16
Encroach Node=18407.60
       1 8914.82 13307.9
Encroach Node=16112.37
       1 4718.11 8631.08
Encroach Node=14000.00
       1 8617.3811546.16
Encroach Node=11846.42
       1 2060.67 6353.78
Encroach Node=9741.539
       1 5604.75 9327.26
Encroach Node=8199.469
       1    6608 9477.15
Encroach Node=7495.891
       1    5956    8827
Encroach Node=7019.933
       1    2500    5370
Encroach Node=6304.094
       1    2400    5950
Encroach Node=5608.017
       1    2400    6800
Encroach Node=4937.113
       1    2166    7097
Encroach Node=4227.846
       1    2101    7766
Encroach Node=3488.651
       1    2101    7366
Encroach Node=3144.491
       1    2282    7666
Encroach Node=3054.182
       1    2132    7932
Encroach Node=2800.539
       1    2300    7900
Encroach Node=2102.301
       1    2484    8538
Encroach Node=1412.242
       1 3456.63 7336.26
Encroach Node=1057.807
       1    350910465.99
Encroach Node=711.868
       1 3992.5410767.47
Encroach Node=0.000
       1 2903.82 8232.37
Computation Interval=1HOUR
Output Interval=1HOUR
Instantaneous Interval=1HOUR
Mapping Interval=1HOUR
Computation Time Step Use Courant=        0
Computation Time Step Use Time Series=    0
Computation Time Step Count To Double=0
Computation Time Step Max Doubling=0
Computation Time Step Max Halving=0
Computation Time Step Residence Courant=0
Run HTab= 0
Run UNet= 0
Run Sediment= 0
Run PostProcess= 0
Run WQNet= 0
Run RASMapper= 0
UNET Theta= 1
UNET Theta Warmup= 1
UNET ZTol= 0.02
UNET ZSATol= 0.1
UNET MxIter= 20
UNET Max Iter WO Improvement= 0
UNET MaxInSteps= 20
UNET DtIC= 0
UNET DtMin= 0
UNET MaxCRTS= 20
UNET WFStab= 2
UNET SFStab= 1
UNET WFX= 1
UNET SFX= 1
UNET 1D Methodology=Finite Difference
UNET DSS MLevel= 4
UNET Pardiso=0
UNET DZMax Abort= 100
UNET Use Existing IB Tables=-1
UNET Froude Reduction=False
UNET Froude Limit= 0.8
UNET Froude Power= 4
UNET D1 Cores= 0
UNET D2 Coriolis=0
UNET D2 Cores= 0
UNET D2 Theta= 1
UNET D2 Theta Warmup= 1
UNET D2 Z Tol= 0.01
UNET D2 Volume Tol= 0.01
UNET D2 Max Iterations= 20
UNET D2 Equation= 0
UNET D2 RampUpFraction=0.1
UNET D2 TimeSlices= 1
UNET D2 BCVolumeCheck=0
UNET D1D2 MaxIter= 0
UNET D1D2 ZTol=0.01
UNET D1D2 QTol=0.1
UNET D1D2 MinQTol=1
DSS File=dss
Write IC File= 0
Write IC File at Fixed DateTime=0
IC Time=0,,
Write IC File at Sim End=0
Echo Input=False
Echo Parameters=False
Echo Output=False
Write Detailed= 0
HDF Write Warmup=0
HDF Write Time Slices=0
HDF Flush=0
HDF Face Node Velocities=0
HDF Compression= 1
HDF Chunk Size= 1
HDF Spatial Parts= 1
HDF Use Max Rows=0
HDF Fixed Rows= 1
Calibration Method= 0
Calibration Iterations= 20
Calibration Max Change=0.05
Calibration Tolerance=0.2
Calibration Maximum=1.5
Calibration Minimum=0.5
Calibration Optimization Method= 1
WQ AD Non Conservative
WQ ULTIMATE=-1
WQ Max Comp Step=1HOUR
WQ Output Interval=15MIN
WQ Output Selected Increments= 0
WQ Output face flow=0
WQ Output face velocity=0
WQ Output face area=0
WQ Output face dispersion=0
WQ Output cell volume=0
WQ Output cell surface area=0
WQ Output cell continuity=0
WQ Output cumulative cell continuity=0
WQ Output face conc=0
WQ Output face dconc_dx=0
WQ Output face courant=0
WQ Output face peclet=0
WQ Output face adv mass=0
WQ Output face disp mass=0
WQ Output cell mass=0
WQ Output cell source sink temp=0
WQ Output nsm pathways=0
WQ Output nsm derived pathways=0
WQ Output MaxMinRange=-1
WQ Daily Max Min Mean=-1
WQ Daily Range=0
WQ Daily Time=0
WQ Create Restart=0
WQ Fixed Restart=0
WQ System Summary=0
WQ Write To DSS=0
WQ Use Fixed Temperature=0
Sorting and Armoring Iterations= 10
XS Update Threshold= 0.02
Bed Roughness Predictor= 0
Hydraulics Update Threshold= 0.02
Energy Slope Method= 1
Volume Change Method= 1
Sediment Retention Method= 0
XS Weighting Method= 0
Number of US Weighted Cross Sections= 1
Number of DS Weighted Cross Sections= 1
Upstream XS Weight=0
Main XS Weight=1
Downstream XS Weight=0
Number of DS XS's Weighted with US Boundary= 1
Upstream Boundary Weight= 1
Weight of XSs Associated with US Boundary= 0
Number of US XS's Weighted with DS Boundary= 1
Downstream Boundary Weight= 0.5
Weight of XSs Associated with DS Boundary= 0.5
Percentile Method= 0
Sediment Output Level= 3
Mass or Volume Output= 0
Output Increment Type= 1
Profile and TS Output Increment= 1
XS Output Flag= 0
XS Output Increment= 10
Write Gradation File= 0
Read Gradation Hotstart= 0
Write HDF5 File= 1
Write Binary Output= 1
Write DSS Sediment File= 0
SV Curve= 0
Specific Gage Flag= 0

--- A100-00-00.p01 (plan) ---

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Plan Title=Effective Multi-Profile 2020
Version=Version 3.0.1  May 2012
Short Identifier=Effective MP
Geom File=g01
Flow File=f01
Encroach Param=-1 ,0,0, 0
BEGIN DESCRIPTION:
FEMA Post Project Multi-Profile June 2007 + LOMR 08-06-0819P + LOMR 09-06-1180P + LOMR 12-06-1209P + LOMR 13-06-1986P + 13-06-1908P + LOMR 13-06-1076P + 19-06-2864P
END DESCRIPTION:
Computation Interval=1MIN
UNET ZSATol= 0.02
UNET MaxInSteps= 0
UNET Convert EG Bridges=-1
IC Time=0
Write Velocity= 0

--- A100-00-00.f02 (steady flow) ---

Flow Title=Effective FW 2014
Version=Version 3.0.1  May 2012
Number of Profiles= 2
Profile Names=1PCT_100yr, 1PCTFloodway_100yrFW
River Rch & RM=A100-00-00,A100-00-00_0000      ,249445.6
    1077    1077
River Rch & RM=A100-00-00,A100-00-00_0000      ,247470.2
    1077    1077
River Rch & RM=A100-00-00,A100-00-00_0000      ,245978.4
    1077    1077
River Rch & RM=A100-00-00,A100-00-00_0000      ,243897.7
    1077    1077
River Rch & RM=A100-00-00,A100-00-00_0000      ,242220.2
    1077    1077
River Rch & RM=A100-00-00,A100-00-00_0000      ,241521
    1077    1077
River Rch & RM=A100-00-00,A100-00-00_0000      ,239967.4
    1077    1077
River Rch & RM=A100-00-00,A100-00-00_0000      ,239432.8
    1077    1077
River Rch & RM=A100-00-00,A100-00-00_0000      ,238465.7
    1077    1077
River Rch & RM=A100-00-00,A100-00-00_0000      ,237689.3
    1077    1077
River Rch & RM=A100-00-00,A100-00-00_0000      ,236608.9
    1077    1077
River Rch & RM=A100-00-00,A100-00-00_0000      ,235828.2
    1077    1077
River Rch & RM=A100-00-00,A100-00-00_0000      ,234461.3
    1077    1077
River Rch & RM=A100-00-00,A100-00-00_0000      ,233734.5
    1077    1077
River Rch & RM=A100-00-00,A100-00-00_0000      ,232999.9
    1077    1077
River Rch & RM=A100-00-00,A100-00-00_0000      ,232232.1
    1103    1103
River Rch & RM=A100-00-00,A100-00-00_0000      ,231533.3
    2382    2382
River Rch & RM=A100-00-00,A100-00-00_0000      ,222868.7
    2382    2382
River Rch & RM=A100-00-00,A100-00-00_0000      ,219890.1
    2382    2382
River Rch & RM=A100-00-00,A100-00-00_0000      ,216969.0
    2382    2382
River Rch & RM=A100-00-00,A100-00-00_0000      ,214705.8
    3826    3826
River Rch & RM=A100-00-00,A100-00-00_0000      ,209667.7
    4006    4006
River Rch & RM=A100-00-00,A100-00-00_0000      ,204504.6
    4170    4170
River Rch & RM=A100-00-00,A100-00-00_0000      ,199968.0
    4244    4244
River Rch & RM=A100-00-00,A100-00-00_0000      ,197996.2
    4244    4244
River Rch & RM=A100-00-00,A100-00-00_0000      ,192943.9
    4244    4244
River Rch & RM=A100-00-00,A100-00-00_0000      ,188162.9
    4244    4244
River Rch & RM=A100-00-00,A100-00-00_0000      ,184837.1
    4244    4244
River Rch & RM=A100-00-00,A100-00-00_0000      ,179278.5
    5376    5376
River Rch & RM=A100-00-00,A100-00-00_0000      ,165983.9
    5376    5376
River Rch & RM=A100-00-00,A100-00-00_0000      ,160102.4
    5376    5376
River Rch & RM=A100-00-00,A100-00-00_0000      ,154437.2
    5376    5376
River Rch & RM=A100-00-00,A100-00-00_0000      ,148981.8
    5376    5376
River Rch & RM=A100-00-00,A100-00-00_0000      ,141725.5
    5376    5376
River Rch & RM=A100-00-00,A100-00-00_0000      ,136801.7
    5376    5376
River Rch & RM=A100-00-00,A100-00-00_0000      ,129631.0
    7901    7901
River Rch & RM=A100-00-00,A100-00-00_0000      ,128562.0
    7901    7901
River Rch & RM=A100-00-00,A100-00-00_0000      ,127103.5
    7901    7901
River Rch & RM=A100-00-00,A100-00-00_0000      ,125781.7
    7901    7901
River Rch & RM=A100-00-00,A100-00-00_0000      ,124241.3
    7901    7901
River Rch & RM=A100-00-00,A100-00-00_0000      ,123196.7
   12497   12497
River Rch & RM=A100-00-00,A100-00-00_0000      ,111295.8
   12587   12587
River Rch & RM=A100-00-00,A100-00-00_0000      ,106343.5
   16162   16162
River Rch & RM=A100-00-00,A100-00-00_0000      ,103329.9
   16282   16282
River Rch & RM=A100-00-00,A100-00-00_0000      ,93497.69
   20934   20934
River Rch & RM=A100-00-00,A100-00-00_0000      ,77642.36
   22891   22891
River Rch & RM=A100-00-00,A100-00-00_0000      ,72765.55
   23659   23659
River Rch & RM=A100-00-00,A100-00-00_0000      ,61501.83
   23660   23660
River Rch & RM=A100-00-00,A100-00-00_0000      ,55615.42
   24535   24535
River Rch & RM=A100-00-00,A100-00-00_0000      ,36556.81
   24557   24557
River Rch & RM=A100-00-00,A100-00-00_0000      ,30794.12
   24879   24879
River Rch & RM=A100-00-00,A100-00-00_0000      ,20859.46
   42013   42013
River Rch & RM=A100-00-00,A100-00-00_0000      ,18407.60
   42013   42013
River Rch & RM=A100-00-00,A100-00-00_0000      ,16112.37
   47042   47042
River Rch & RM=A100-00-00,A100-00-00_0000      ,14000.00
   47042   47042
River Rch & RM=A100-00-00,A100-00-00_0000      ,9741.539
   47042   47042
Boundary for River Rch & Prof#=A100-00-00,A100-00-00_0000      , 1
Up Type= 0
Dn Type= 1
Dn Known WS=1.45
Boundary for River Rch & Prof#=A100-00-00,A100-00-00_0000      , 2
Up Type= 0
Dn Type= 1
Dn Known WS=2.45
Gate Openings=A100-00-00,A100-00-00_0000,3858    ,Gate #1     ,
      20       6       0       0
DSS Import GetInterval= 0
DSS Import GetPeak= 0
DSS Import FillOption= 0

--- A100-00-00.f01 (steady flow) ---

Flow Title=Effective MP 2014
Version=Version 3.0.1  Mar 2001
Number of Profiles= 4
Profile Names=10PCT_10yr, 2PCT_50yr, 1PCT_100yr, 0.2PCT_500yr
River Rch & RM=A100-00-00,A100-00-00_0000 ,249445.6
     414     821    1077    1925
River Rch & RM=A100-00-00,A100-00-00_0000 ,247470.2
     414     821    1077    1925
River Rch & RM=A100-00-00,A100-00-00_0000 ,245978.4
     414     821    1077    1925
River Rch & RM=A100-00-00,A100-00-00_0000 ,243897.7
     414     821    1077    1925
River Rch & RM=A100-00-00,A100-00-00_0000 ,242220.2
     414     821    1077    1925
River Rch & RM=A100-00-00,A100-00-00_0000 ,241521
     414     821    1077    1925
River Rch & RM=A100-00-00,A100-00-00_0000 ,239967.4
     414     821    1077    1925
River Rch & RM=A100-00-00,A100-00-00_0000 ,239432.8
     414     821    1077    1925
River Rch & RM=A100-00-00,A100-00-00_0000 ,238465.7
     422     821    1077    1925
River Rch & RM=A100-00-00,A100-00-00_0000 ,237689.3
     440     821    1077    1925
River Rch & RM=A100-00-00,A100-00-00_0000 ,236608.9
     453     821    1077    1925
River Rch & RM=A100-00-00,A100-00-00_0000 ,235828.2
     476     821    1077    1925
River Rch & RM=A100-00-00,A100-00-00_0000 ,234461.3
     489     832    1077    1925
River Rch & RM=A100-00-00,A100-00-00_0000 ,233734.5
     503     853    1077    1925
River Rch & RM=A100-00-00,A100-00-00_0000 ,232999.9
     517     876    1077    1925
River Rch & RM=A100-00-00,A100-00-00_0000 ,232232.1
     531     898    1103    1925
River Rch & RM=A100-00-00,A100-00-00_0000 ,231533.3
    1122    1902    2382    3951
River Rch & RM=A100-00-00,A100-00-00_0000 ,222868.7
    1138    1902    2382    3951
River Rch & RM=A100-00-00,A100-00-00_0000 ,219890.1
    1154    1902    2382    3951
River Rch & RM=A100-00-00,A100-00-00_0000 ,216969.0
    1166    1902    2382    3951
River Rch & RM=A100-00-00,A100-00-00_0000 ,214705.8
    1880    3105    3826    6201
River Rch & RM=A100-00-00,A100-00-00_0000 ,209667.7
    2016    3248    4006    6544
River Rch & RM=A100-00-00,A100-00-00_0000 ,204504.6
    2144    3379    4170    6860
River Rch & RM=A100-00-00,A100-00-00_0000 ,199968.0
    2203    3438    4244    7002
River Rch & RM=A100-00-00,A100-00-00_0000 ,197996.2
    2203    3438    4244    7002
River Rch & RM=A100-00-00,A100-00-00_0000 ,192943.9
    2203    3438    4244    7002
River Rch & RM=A100-00-00,A100-00-00_0000 ,188162.9
    2203    3438    4244    7002
River Rch & RM=A100-00-00,A100-00-00_0000 ,184837.1
    2203    3438    4244    7002
River Rch & RM=A100-00-00,A100-00-00_0000 ,179278.5
    2982    4553    5376    7991
River Rch & RM=A100-00-00,A100-00-00_0000 ,165983.9
    2982    4553    5376    7991
River Rch & RM=A100-00-00,A100-00-00_0000 ,160102.4
    2982    4553    5376    7991
River Rch & RM=A100-00-00,A100-00-00_0000 ,154437.2
    2982    4553    5376    7991
River Rch & RM=A100-00-00,A100-00-00_0000 ,148981.8
    2982    4553    5376    7991
River Rch & RM=A100-00-00,A100-00-00_0000 ,141725.5
    2982    4553    5376    7991
River Rch & RM=A100-00-00,A100-00-00_0000 ,136801.7
    2982    4553    5376    7991
River Rch & RM=A100-00-00,A100-00-00_0000 ,129631.0
    4361    6766    7901   10572
River Rch & RM=A100-00-00,A100-00-00_0000 ,128562.0
    4361    6766    7901   10572
River Rch & RM=A100-00-00,A100-00-00_0000 ,127103.5
    4361    6766    7901   10572
River Rch & RM=A100-00-00,A100-00-00_0000 ,125781.7
    4361    6766    7901   10572
River Rch & RM=A100-00-00,A100-00-00_0000 ,124241.3
    4361    6766    7901   10572
River Rch & RM=A100-00-00,A100-00-00_0000 ,123196.7
    6999   10803   12497   17621
River Rch & RM=A100-00-00,A100-00-00_0000 ,111295.8
    7051   10875   12587   17798
River Rch & RM=A100-00-00,A100-00-00_0000 ,106343.5
    9343   14080   16162   22566
River Rch & RM=A100-00-00,A100-00-00_0000 ,103329.9
    9428   14181   16282   22763
River Rch & RM=A100-00-00,A100-00-00_0000 ,93497.69
   11980   18188   20934   29187
River Rch & RM=A100-00-00,A100-00-00_0000 ,77642.36
   13201   19868   22891   30896
River Rch & RM=A100-00-00,A100-00-00_0000 ,72765.55
   13562   20517   23659   31516
River Rch & RM=A100-00-00,A100-00-00_0000 ,61501.83
   13563   20518   23660   31516
River Rch & RM=A100-00-00,A100-00-00_0000 ,55615.42
   14037   21289   24535   32653
River Rch & RM=A100-00-00,A100-00-00_0000 ,36556.81
   14051   21317   24557   32752
River Rch & RM=A100-00-00,A100-00-00_0000 ,30794.12
   14229   21633   24879   33496
River Rch & RM=A100-00-00,A100-00-00_0000 ,20859.46
   20938   35377   42013   64503
River Rch & RM=A100-00-00,A100-00-00_0000 ,18407.60
   20938   35377   42013   64575
River Rch & RM=A100-00-00,A100-00-00_0000 ,16112.37
   22481   38995   47042   72745
River Rch & RM=A100-00-00,A100-00-00_0000 ,14000.00
   22481   38995   47042   72745
River Rch & RM=A100-00-00,A100-00-00_0000 ,9741.539
   22481   38995   47042   72745
Boundary for River Rch & Prof#=A100-00-00,A100-00-00_0000 , 1
Up Type= 0
Dn Type= 1
Dn Known WS=.9
Boundary for River Rch & Prof#=A100-00-00,A100-00-00_0000 , 2
Up Type= 0
Dn Type= 1
Dn Known WS=1.3
Boundary for River Rch & Prof#=A100-00-00,A100-00-00_0000 , 3
Up Type= 0
Dn Type= 1
Dn Known WS=1.45
Boundary for River Rch & Prof#=A100-00-00,A100-00-00_0000 , 4
Up Type= 0
Dn Type= 1
Dn Known WS=1.75
Gate Openings=A100-00-00,A100-00-00_0000,3858    ,Gate #1     ,
      20       6       0       0       0       0       0       0
DSS Import GetInterval= 0
DSS Import GetPeak= 0
DSS Import FillOption= 0

--- A100-00-00.g01 (geometry) ---

Geom Title=A100-00-00 2020
Version=Version 3.0.1  May 2012

River Reach=A100-00-00      ,A100-00-00_0000
Reach XY= 30
      3093656.01    13775343.735     3097062.568    13777112.683
     3101329.068    13775153.683     3105929.372    13777173.552
     3114740.079    13776720.541     3120043.492    13779319.834
     3129516.796    13778608.278     3134091.536    13783671.454
     3154953.039    13782662.071     3161293.676    13767792.077
     3164222.605    13770889.955     3171296.098    13768722.225
       3175932.9    13771923.971     3178428.338    13770747.228
     3176679.246    13765133.007     3180594.904    13761473.501
     3182202.683    13756033.169     3187217.551    13753817.087
     3186183.662    13751994.186      3189202.57    13748406.593
     3200892.424    13753538.942     3207288.755    13753874.594
     3207494.155    13757512.393      3209130.93    13756640.908
     3210472.575    13758784.026     3209404.617    13762625.108
     3214933.081    13762825.558     3214588.618    13766756.786
     3218791.127    13771496.882     3235698.331    13768577.461

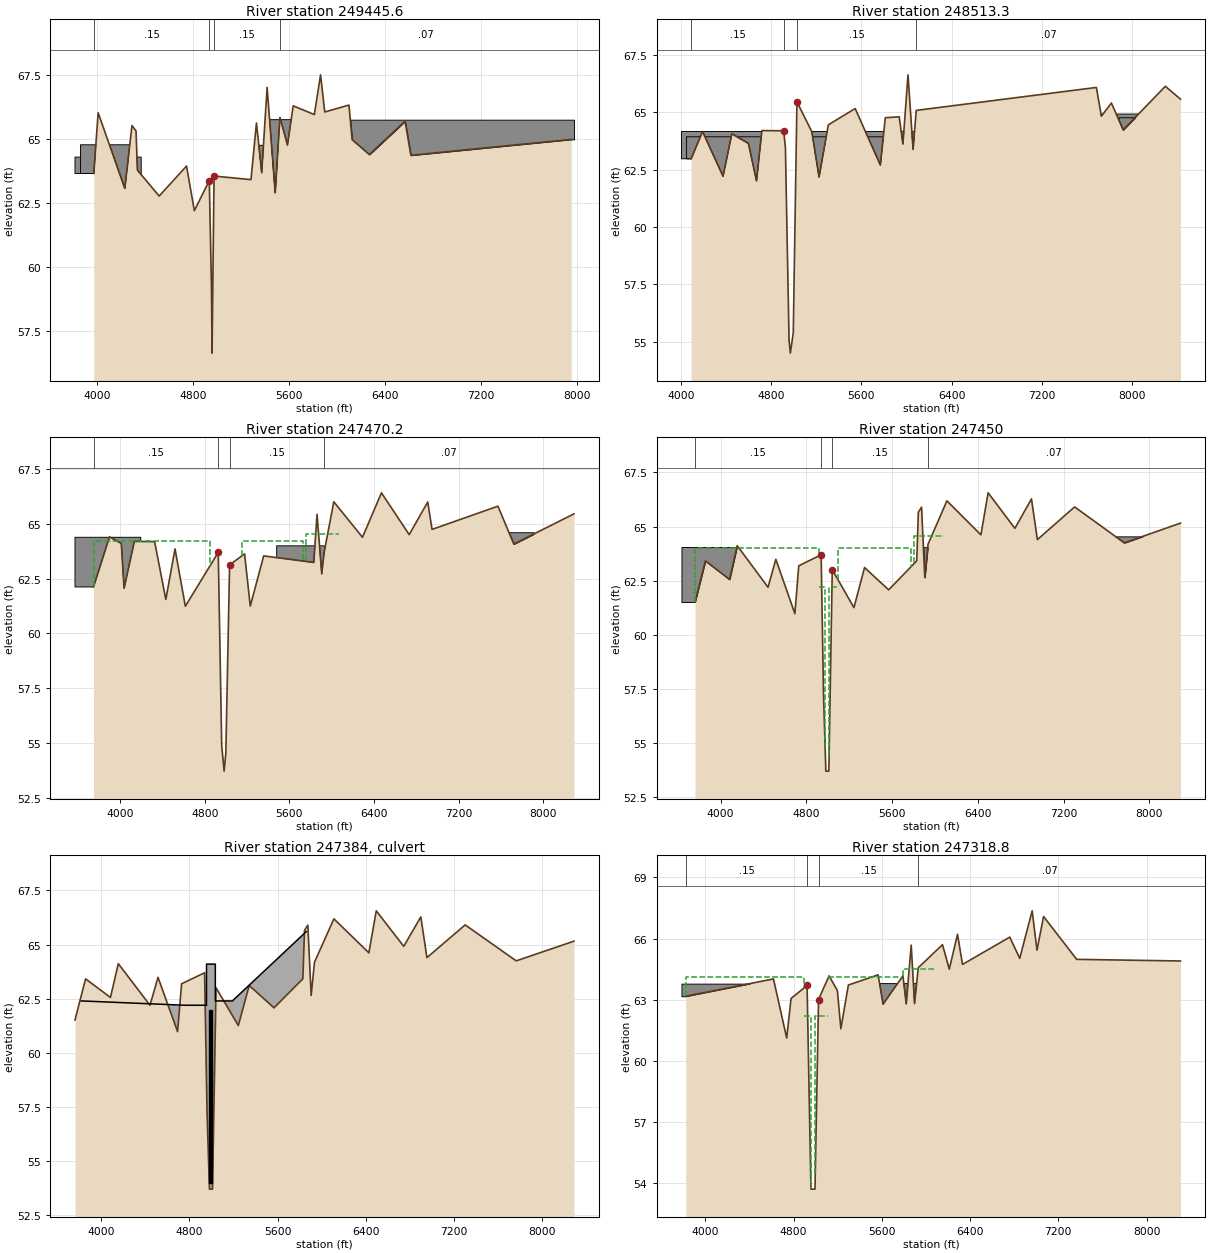
Type RM Length L Ch R = 1 ,249445.6,1324.63,932.22,672.17
XS GIS Cut Line= 4
     3092678.817    13775834.303      3094062.75    13775918.484
     3094433.486     13775586.82     3094574.666    13773498.126
#Sta/Elev= 30
 3975.82   63.64 4012.07   66.01 4234.35   63.06 4293.97   65.51 4327.65    65.3
 4339.48   63.77 4520.63   62.76 4748.43   63.93 4813.73   62.19 4938.22   63.36
 4956.27   59.22 4961.27   56.63  4977.8   63.54 5285.59    63.4 5331.21   65.61
 5375.04   63.67 5420.03      67 5487.52   62.89    5527   65.83 5589.77   64.75
  5637.3   66.28 5813.48   65.94 5865.36   67.49 5900.43   66.04 6101.94   66.31
 6128.32   64.96 6272.51   64.38 6569.54   65.68 6617.91   64.35 7953.21   64.97
#Mann= 4 ,-1 , 0
 3975.82     .15       0 4938.22     .04       0  4977.8     .15       0
    5527     .07       0
#Block Obstruct= 6 ,-1
 3819.11 4370.88   64.28 3864.62 4296.93   64.76 5343.57 5690.56   64.31
 5343.57 5684.87   64.74  5428.9 6100.11   65.74 6094.43 7977.25   65.74
Bank Sta=4938.22,4977.8
XS Rating Curve= 0
Exp/Cntr=.3,.1

Type RM Length L Ch R = 1 ,248513.3,1599.59,1043.08,251.68
XS GIS Cut Line= 3
      3093595.82    13777186.329     3094999.773    13776022.718
     3095046.798    13773511.241
#Sta/Elev= 30
4091.735   62.97 4192.61   64.16 4374.18   62.21 4452.16   64.06 4599.04   63.64
 4670.91   62.01 4718.19    64.2 4911.58   64.19 4926.86   63.46 4959.21   55.05
 4970.56    54.5 4996.31   55.38 5028.99   65.45 5160.95   64.15 5224.87   62.18
 5306.97   64.45 5545.01   65.16 5768.17    62.7 5811.61   64.76 5935.37    64.8
 5967.95   63.62 6012.95   66.63 6057.96   63.386086.01565.07993 7682.17   66.08
 7726.41   64.83 7815.59    65.4 7919.64   64.23 8293.35   66.13 8427.14   65.57
#Mann= 4 ,-1 , 0
4091.735     .15       0 4911.58     .04       0 5028.99     .15       0
6086.015     .07       0
#XS Ineff= 1 ,-1
 6013.65 6440.27   65.25
Permanent Ineff=
       F
#Block Obstruct= 6 ,-1
 4005.69 4910.12   64.16 4051.19 4739.48   63.93 5075.09 6241.18   64.16
 5143.34 6172.92   63.93 7651.88 8425.48   64.92 7879.41 8129.69   64.78
Bank Sta=4911.58,5028.99
XS Rating Curve= 0
Exp/Cntr=.3,.1

Type RM Length L Ch R = 1 ,247470.2,70.38,20.22,21.76
XS GIS Cut Line= 6
     3095777.821    13777904.688     3095540.477    13777630.236
     3095305.709    13777152.416     3095249.267    13776680.389
     3095241.877      13775976.8     3095309.093    13773511.241
#Sta/Elev= 30
3748.835   62.12 3899.72   64.41 4011.17   64.11 4037.75   62.06 4134.63    64.2
 4326.36   64.19 4432.05   61.55 4519.08   63.86 4616.51   61.24  4927.7    63.7
  4960.3   54.88 4983.13   53.71 4999.37   54.54 5034.88   63.13 5176.47   63.63
 5230.44   61.25  5357.1   63.54  5830.6   63.24 5861.42   65.44 5905.63   62.72
5928.72563.69987 6019.74   66.01 6291.16   64.39 6470.34   66.42 6732.58   64.51
 6907.79      66 6948.53   64.75 7571.25   65.81  7721.3   64.08 8290.27   65.46
#Mann= 4 ,-1 , 0
3748.835     .15       0  4927.7     .04       0 5034.88     .15       0
5928.725     .07       0
#XS Ineff= 3 ,-1
 3748.84 4849.83    64.2 5150.17 5730.38    64.2 5757.68 6064.85   64.55
Permanent Ineff=
       F       F       F
#Block Obstruct= 3 ,-1
 3573.48 4194.74   64.39 7600.68 7907.85   64.62    5480    6200      64
Bank Sta=4927.7,5034.88
XS Rating Curve= 0
Exp/Cntr=.5,.3

Type RM Length L Ch R = 1 ,247450  ,280.58,131.22,160.07
XS GIS Cut Line= 6
     3095818.663    13777884.267     3095572.485    13777595.525
     3095318.088    13777078.379     3095269.131    13776678.025
     3095261.879    13775976.734     3095348.437    13773511.241
#Sta/Elev= 30
 3761.55   61.52 3857.68   63.42 4083.17   62.56 4154.71   64.12 4442.03    62.2
 4514.92   63.49 4692.66   60.98 4728.74   63.19  4937.7    63.7 4959.68   57.27
 4981.61   53.71 5009.37   53.71 5041.49   63.01 5243.62   61.26 5342.58   63.11
 5567.47   62.08 5829.43   63.42 5844.44   65.66 5874.46    65.9 5904.47   62.65
 5935.06   64.19  6111.1   66.19 6428.23   64.62 6495.32   66.56 6744.99   64.92
 6899.76   66.28 6955.12    64.4 7302.23   65.91 7765.58   64.25  8289.7   65.16
#Mann= 4 ,-1 , 0
 3761.55     .15       0  4937.7     .04       0 5041.49     .15       0
 5935.06     .07       0
#XS Ineff= 7 ,-1
 3761.55 4918.09      64 4918.09    4975    62.2    5012 5095.56    62.2
 5095.56 5778.16      64 5778.16 5805.46    62.2 5805.46 6085.32   64.55
 6085.32  8289.7    62.2
Permanent Ineff=
       F       F       F       F       F       F       F
#Block Obstruct= 3 ,-1
 3634.52  4154.4   64.06 5853.05 6189.96   64.05 7518.77  8262.8   64.55
Bank Sta=4937.7,5041.49
XS Rating Curve= 0
Exp/Cntr=.5,.3

Type RM Length L Ch R = 2 ,247384  ,,,
BEGIN DESCRIPTION:
Hiram Clarke Rd
END DESCRIPTION:
Bridge Culvert--1,0,-1,-1, 0
Deck Dist Width WeirC Skew NumUp NumDn MinLoCord MaxHiCord MaxSubmerge Is_Ogee
10,110,2.6,0, 8, 8, , , .95, 0, 0,0,,
    3820    4760    4955    4955    5035    5035    5190    5860
    62.4    62.2    62.2    64.1    64.1    62.4    62.4    65.6
       0       0       0       0       0       0       0       0
    3820    4760    4940    4940    5020    5020    5190    5860
    62.4    62.2    62.2    64.1    64.1    62.4    62.4    65.6
       0       0       0       0       0       0       0       0
BR Coef=-1 , 1 , 0 ,, 0 ,,,.8,-1,,0,
WSPro=,,,, 1 ,,,, 0 ,,,, 0 ,,,,-1 ,-1 ,-1 , 0 , 0 , 0 , 0 , 0
Multiple Barrel Culv=2,8,8,110,.012,.4,1,8,1,54,54, 3,Culvert #1  , 0 ,10
    4983    4968    4993    4978    5003    4988
Culvert Bottom n=.012
BC Design=,, 0 ,, 0 ,,,,,,
BC HTab HWMax=66.56

Type RM Length L Ch R = 1 ,247318.8,120.03,80.01,85.29
XS GIS Cut Line= 6
     3095937.785    13777843.425     3095661.287    13777484.982
     3095566.805    13777278.446     3095420.174    13776873.068
     3095414.331    13776431.886     3095468.138    13773499.296
#Sta/Elev= 30
3822.635   63.17 4617.78   64.02 4737.77   61.12 4777.29   63.06  4922.7    63.7
 4957.63   53.71 4994.37   53.71 5026.49   63.01 5121.98   64.17 5197.29   63.45
 5228.82   61.58    5297   63.72 5566.68   64.22 5611.68   62.78 5791.71   64.17
 5821.72    62.8 5866.73   65.68 5896.73   62.815930.67564.56993 6150.33    65.7
 6211.89    64.5 6286.53   66.21 6331.81   64.73 6760.13   66.07 6850.69   65.03
 6963.44   67.36 7006.92   65.43 7066.93   67.08 7366.98   64.98 8307.84    64.9
#Mann= 4 ,-1 , 0
3822.635     .15       0  4922.7     .04       0 5026.49     .15       0
5930.675     .07       0
#XS Ineff= 7 ,-1
 3822.64 4897.61    64.1 4897.61    4959    62.2    4997 5116.04    62.2
 5116.04 5778.16    64.1 5778.16 5791.81    62.2 5791.81 6085.32   64.52
 6085.32 8307.84    62.2
Permanent Ineff=
       F       F       F       F       F       F       F
#Block Obstruct= 3 ,-1
 3783.65  4600.7   63.79 7457.34 8242.32   64.65    5450    6100   63.79
Bank Sta=4922.7,5026.49
XS Rating Curve= 0
Exp/Cntr=.5,.3

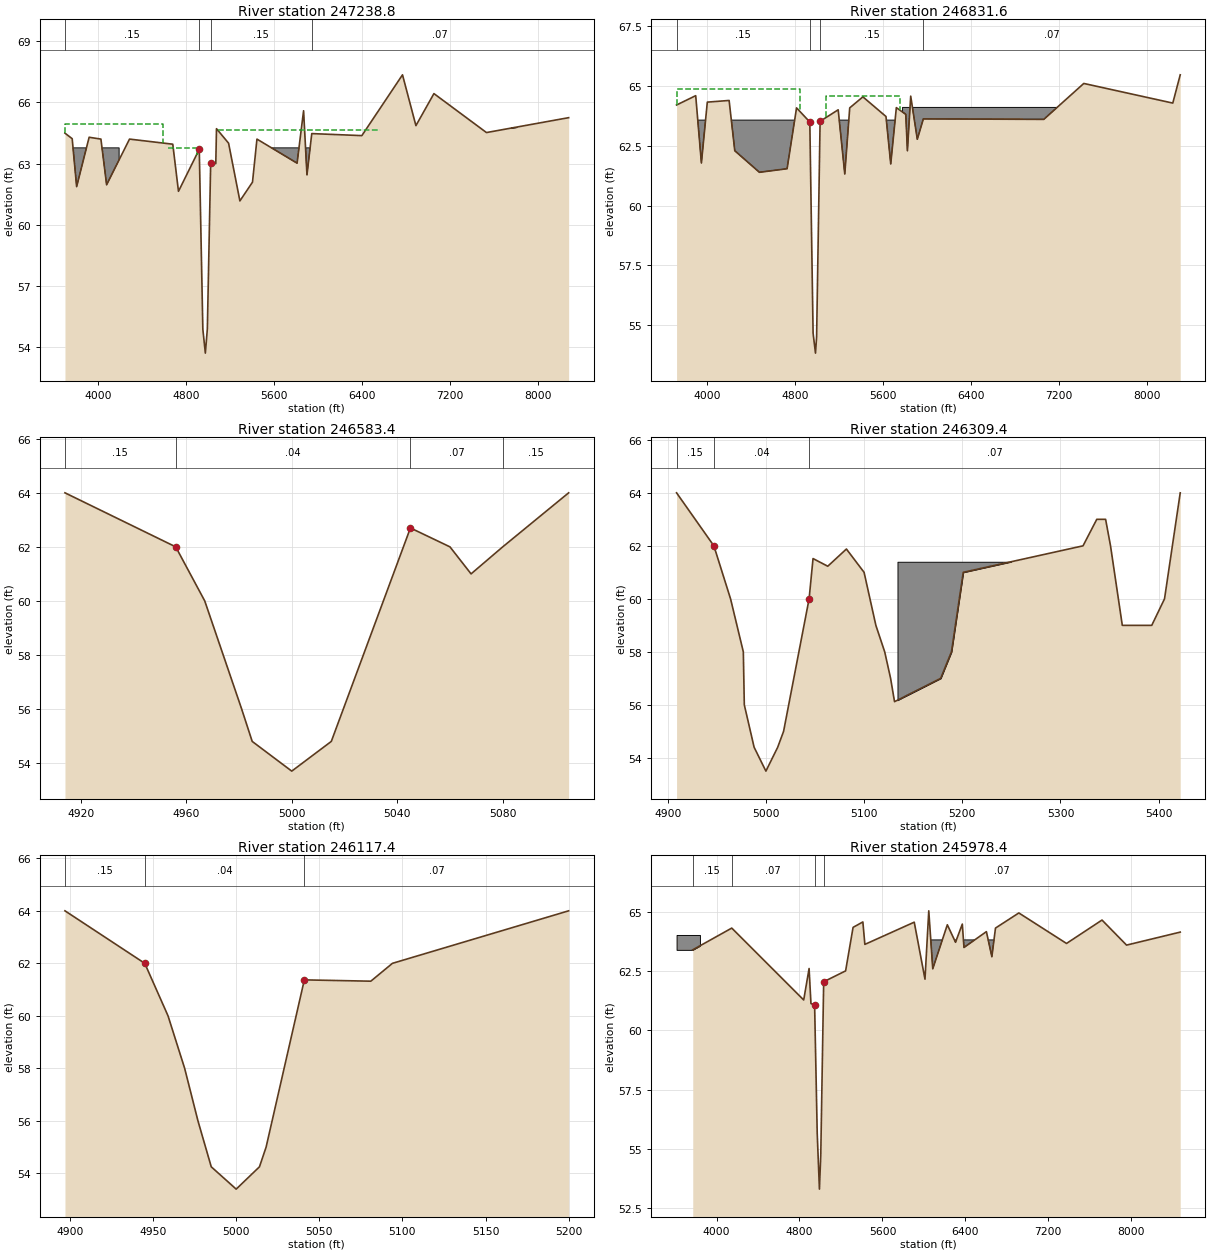
Type RM Length L Ch R = 1 ,247238.8,94.39,407.19,412.08
XS GIS Cut Line= 6
     3096073.924     13777955.74      3095962.35     13777787.55
     3095709.751    13777448.621      3095500.03     13776861.67
     3095494.336     13776431.74     3095567.007    13773532.253
#Sta/Elev= 30
 3702.08   64.49 3767.59   64.22 3808.14   61.87 3921.71   64.29 4028.79    64.2
  4080.6   61.96 4288.72    64.2 4681.99   63.95 4733.82   61.64  4922.7    63.7
  4955.3   54.88 4978.13   53.71 4996.26    54.9 5026.49   63.01 5072.92      63
 5079.36   64.71 5189.23      64 5292.11   61.17 5406.63   62.09 5447.15    64.2
 5811.92   63.02 5870.95   65.59 5901.78   62.45  5945.4   64.47 6400.67   64.37
 6770.11   67.35 6892.09   64.86 7055.82   66.43 7533.43   64.52 8280.27   65.25
#Mann= 4 ,-1 , 0
 3702.08     .15       0  4922.7     .04       0 5026.49     .15       0
  5945.4     .07       0
#XS Ineff= 3 ,-1
 3702.08 4590.44   64.95 4638.23 4897.61   63.75 5088.74 6569.97   64.65
Permanent Ineff=
       F       F       F
#Block Obstruct= 3 ,-1
 3696.88 4194.31   63.77 7757.68 8385.67   64.79    5500    6100   63.77
Bank Sta=4922.7,5026.49
XS Rating Curve= 0
Exp/Cntr=.3,.1

Type RM Length L Ch R = 1 ,246831.6,221,240,260
BEGIN DESCRIPTION:
Lengths revised 11/11/07 to reflect added section but total length between existing sections the same.
END DESCRIPTION:
XS GIS Cut Line= 4
     3096160.225    13778047.297     3095899.598    13777585.932
     3095912.978     13776020.47     3095929.529    13773532.253
#Sta/Elev= 30
 3721.15    64.2 3895.36   64.59  3947.2   61.78 4000.94   64.32 4199.39   64.39
 4251.04   62.29 4475.24   61.39 4726.99   61.54 4813.19   64.08 4933.77   63.49
 4963.71   54.67 4985.46   53.84 4995.67   54.52 5027.45   63.52 5192.01      64
 5252.01   61.32 5297.01   64.08 5416.91   64.54 5627.02   63.72  5670.3   61.74
 5721.32   64.09 5807.03   63.81 5822.03   62.29 5852.03   64.57 5912.03   62.77
 5967.15   63.62 7063.25    63.6 7427.06    65.1 8237.08   64.28 8304.83   65.46
#Mann= 4 ,-1 , 0
 3721.15     .15       0 4933.77     .04       0 5027.45     .15       0
 5967.15     .07       0
#XS Ineff= 2 ,-1
 3721.15    4843   64.86 5081.91 5750.85   64.56
Permanent Ineff=
       F       F
#Block Obstruct= 3 ,-1
 3759.86 4827.96   63.57 5778.16 8228.67    64.1    5150    5770   63.57
Bank Sta=4933.77,5027.45
XS Rating Curve= 0
Exp/Cntr=.3,.1

Type RM Length L Ch R = 1 ,246583.4,274,274,274
BEGIN DESCRIPTION:
New Section for CLOMR.  See note about lenghts on 246831.6
END DESCRIPTION:
XS GIS Cut Line= 2
      3096123.97     13776953.69      3096171.64       13776768.
#Sta/Elev= 13
    4914      64    4956      62    4967      60    4974      58    4981      56
    4985    54.8    5000    53.7    5015    54.8    5045    62.7    5060      62
    5068      61    5080      62    5105      64
#Mann= 4 ,-1 , 0
    4914     .15       0    4956     .04       0    5045     .07       0
    5080     .15       0
Bank Sta=4956,5045
XS Rating Curve= 0
Exp/Cntr=.3,.1

Type RM Length L Ch R = 1 ,246309.4,192,192,192
BEGIN DESCRIPTION:
New Section for CLOMR.  See note about lenghts on 246831.6
END DESCRIPTION:
XS GIS Cut Line= 3
      3096383.66     13777047.88      3096593.42     13776230.76
      3096645.68     13776027.15
#Sta/Elev= 29
    4909      64    4947      62    4964      60    4977      58    4978      56
    4988    54.4    5000    53.5    5012    54.4    5018      55    5044      60
    5048   61.52    5063   61.23    5082   61.88    5100      61    5112      59
    5121      58    5127      57    5131   56.12    5178      57    5189      58
    5201      61    5323      62    5337      63    5346      63    5351      62
    5363      59    5393      59    5406      60    5422      64
#Mann= 3 ,-1 , 0
    4909     .15       0    4947     .04       0    5044     .07       0
#XS Ineff= 2 , 0
    4809                    5346    4809      63
Permanent Ineff=
       F       F
#Block Obstruct= 1 ,-1
    5134    5323    61.4
Bank Sta=4947,5044
XS Rating Curve= 0
Exp/Cntr=.3,.1

Type RM Length L Ch R = 1 ,246117.4,152,139,131
BEGIN DESCRIPTION:
New Section for CLOMR, east property line, reflects constriction.  See note about lenghts on 246831.6
END DESCRIPTION:
XS GIS Cut Line= 2
      3096564.49     13777113.34      3096639.47     13776821.24
#Sta/Elev= 13
    4897      64    4945      62    4959      60    4969      58    4977      56
    4985   54.25    5000    53.4    5014   54.25    5018      55    5041   61.37
    5081   61.32    5094      62    5200      64
#Mann= 3 ,-1 , 0
    4897     .15       0    4945     .04       0    5041     .07       0
Bank Sta=4945,5041
XS Rating Curve= 0
Exp/Cntr=.3,.1

Type RM Length L Ch R = 1 ,245978.4,2201.27,1037.77,329.46
XS GIS Cut Line= 4
     3096440.355    13778245.036     3096581.018    13777749.115
     3096927.861    13776065.102     3096934.703    13773598.166
#Sta/Elev= 30
3770.485   63.414146.62564.33007 4840.66   61.29 4892.56   62.62 4910.43   61.14
 4945.83   61.08 4971.03   55.64 4992.23   53.29 5005.22   54.73 5033.29   62.06
  5244.8   62.52  5316.8   64.36 5411.24   64.59 5430.53   63.64  5906.8   64.58
 6010.44   62.17 6046.93   65.06 6085.44   62.61 6225.95   64.47    6305   63.73
 6370.44    64.5 6386.52   63.51 6602.82   64.18 6655.44   63.12 6690.36   64.33
  6915.7   64.97 7375.44   63.68 7717.83   64.67 7954.58   63.61 8472.28   64.16
#Mann= 4 ,-1 , 0
3770.485     .15       04146.625     .07       0 4945.83     .04       0
 5033.29     .07       0
#XS Ineff= 1 ,-1
 5846.42    6843   64.13
Permanent Ineff=
       F
#Block Obstruct= 2 ,-1
 3614.33 3839.59   64.04 6044.37  7027.3   63.83
Bank Sta=4945.83,5033.29
XS Rating Curve= 0
Exp/Cntr=.3,.1