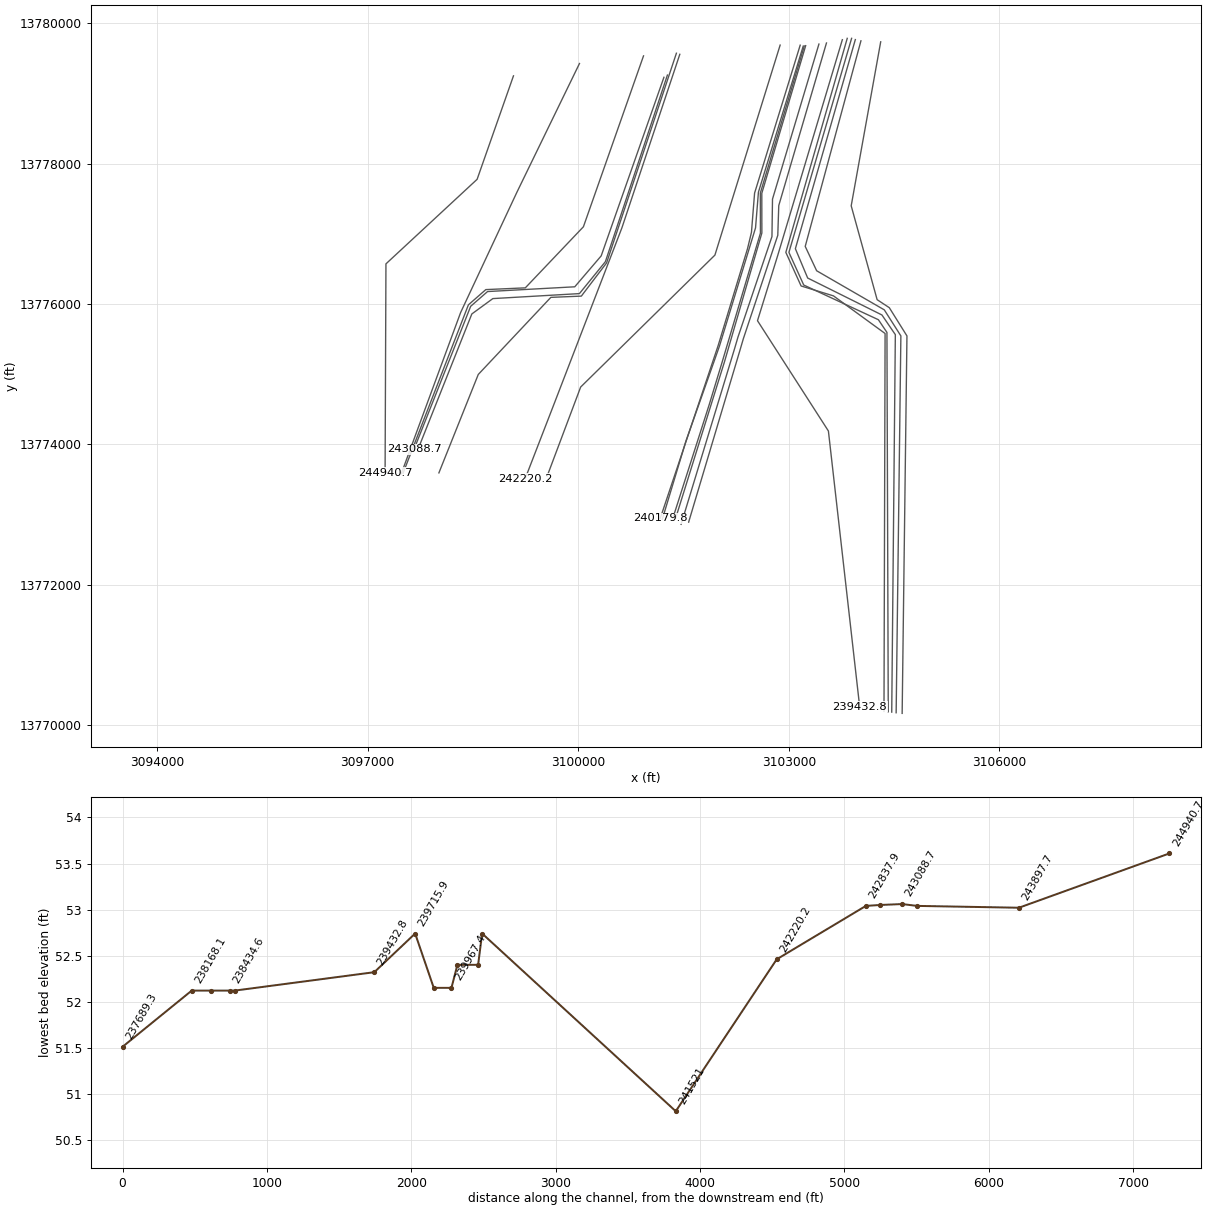
HEC-RAS study A100-00-00.prj: A100-00-00

--- A100-00-00.g01 (geometry) --- (continued)

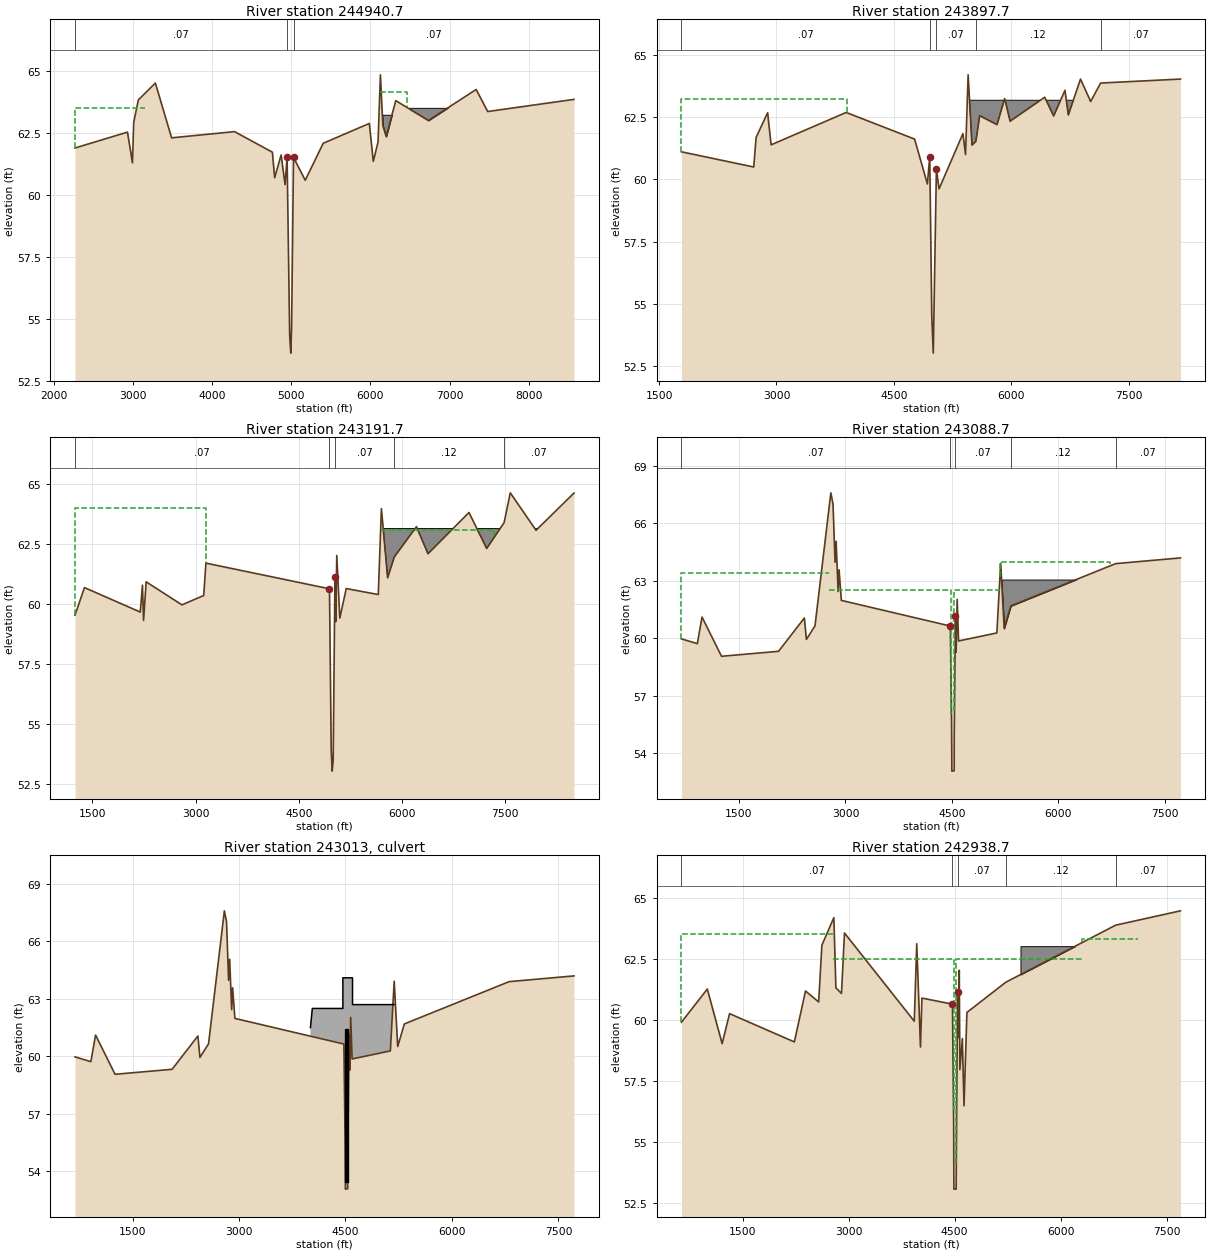
Type RM Length L Ch R = 1 ,244940.7,697.19,1042.99,1049.47
XS GIS Cut Line= 4
     3099076.878     13779250.21     3098558.929    13777776.137
     3097259.915    13776571.441      3097247.79    13773598.166
#Sta/Elev= 30
2265.755   61.88  2929.6   62.52 2992.04   61.28 3007.94   62.91 3066.53   63.82
 3281.74    64.5 3487.05   62.29 4282.61   62.54 4760.95   61.71 4789.34   60.68
 4871.56    61.6 4920.94    60.4 4946.82   61.51 4979.34   54.31 4993.59   53.61
 5003.55   54.65 5027.86    61.5 5176.24   60.58 5403.41   62.07 5986.26   62.87
 6036.27   61.34 6096.27   62.12 6126.27   64.83 6157.06   62.78 6199.59   62.34
  6320.3   63.79 6732.83   62.99  7336.5   64.24 7482.47   63.35 8573.13   63.84
#Mann= 3 ,-1 , 0
2265.755     .07       0 4946.82     .04       0 5027.86     .07       0
#XS Ineff= 3 ,-1
2265.755 3154.72   63.51 6109.21 6124.68   63.36 6124.68 6458.63   64.15
Permanent Ineff=
       F       F       F
#Block Obstruct= 2 ,-1
 6131.42 6415.77   63.22    6495 7136.52    63.5
Bank Sta=4946.82,5027.86
XS Rating Curve= 0
Exp/Cntr=.3,.1

Type RM Length L Ch R = 1 ,243897.7,1021.54,705.99,58.86
XS GIS Cut Line= 4
     3100017.294    13779426.001     3099126.981    13777594.361
     3098323.728    13775877.606     3097478.486    13773581.687
#Sta/Elev= 30
1785.235    61.1 2709.21   60.49 2739.78   61.68 2886.96   62.67 2930.83   61.38
 3891.18   62.68  4765.6   61.61 4928.68   59.81 4958.98   60.89 4985.23   54.47
 5004.11   53.02 5044.06   60.42 5077.37   59.61 5383.32   61.83 5416.44   60.99
 5449.56   64.19 5499.24   61.375548.55561.52008 5597.37   62.55 5818.91   62.19
 5916.46   63.24 5986.36   62.33 6428.54   63.29 6543.18   62.54 6687.37   63.57
 6730.75   62.58 6885.77   64.02 7016.03   63.127143.17563.85995 8163.74   64.02
#Mann= 5 ,-1 , 0
1785.235     .07       0 4958.98     .04       0 5044.06     .07       0
5548.555     .12       07143.175     .07       0
#XS Ineff= 2 ,-1
 1785.24  3903.3    63.2 5441.41 6897.61   63.13
Permanent Ineff=
       F       F
#Block Obstruct= 1 ,-1
 5457.05 7332.33   63.17
Bank Sta=4958.98,5044.06
XS Rating Curve= 0
Exp/Cntr=.3,.1

Type RM Length L Ch R = 1 ,243191.7,393.74,102.95,34.88
XS GIS Cut Line= 6
      3100929.79    13779534.754     3100073.419    13777099.961
     3099245.585     13776229.55     3098682.899    13776204.781
     3098434.801    13775987.696     3097503.172    13773587.265
#Sta/Elev= 30
 1247.46   59.54 1385.01   60.69 2195.94   59.67 2227.75   60.79 2243.65   59.32
 2281.63   60.93 2801.68   59.97 3118.19   60.36 3149.99   61.71 4945.51   60.64
 4970.84   53.92 4984.84   53.04 4999.45    53.5 5024.85   61.14 5035.68   59.27
 5051.69   62.03 5095.76   59.42 5189.11   60.65 5654.61    60.4 5700.16   63.98
 5790.72    61.1 5888.28   61.97 6209.42   63.23 6377.27    62.1 6972.76   63.82
 7230.05   62.32 7483.56    63.4 7572.82   64.64 7947.23   63.08 8498.74   64.63
#Mann= 5 ,-1 , 0
 1247.46     .07       0 4945.51     .04       0 5024.85     .07       0
 5888.28     .12       0 7483.56     .07       0
#XS Ineff= 2 ,-1
       0    3152      64 5696.25 7334.47   63.07
Permanent Ineff=
       F       F
#Block Obstruct= 1 ,-1
 5705.33 8130.48   63.15
Bank Sta=4945.51,5024.85
XS Rating Curve= 0
Exp/Cntr=.5,.3

Type RM Length L Ch R = 1 ,243088.7,60.79,150.05,55.17
XS GIS Cut Line= 6
 3101220.584826113779229.7976261     3100326.736     13776685.21
     3099950.122    13776244.671     3098707.709     13776176.87
     3098467.319    13775967.042 3097660.725542413773931.1549715
#Sta/Elev= 30
 689.727   59.97 913.368   59.72 979.628   61.111254.194   59.06 2057.21   59.32
2421.328   61.06 2450.14   59.942571.177   60.652794.238    67.62824.961   67.01
2853.592   63.972868.808   65.072896.823   62.442910.264   63.582942.256   61.98
4477.623   60.644494.978   55.61 4499.02   53.06 4531.94   53.084532.373   54.89
4549.529   61.144559.345   59.274573.854   62.034593.675   59.865132.747   60.28
5186.772   63.92 5236.12   60.515329.425   61.696805.692    63.97719.577    64.2
#Mann= 5 ,-1 , 0
 689.727     .07       04477.623     .04       04549.529     .07       0
5329.425     .12       06805.692     .07       0
#XS Ineff= 5 ,-1
 689.7272773.575   63.412773.5754493.474    62.5    4536 5175.96    62.5
 5175.96 6732.87      64 6732.877719.577    62.5
Permanent Ineff=
       F       F       F       F       F
#Block Obstruct= 1 ,-1
 5182.63 6805.31   63.07
Bank Sta=4477.623,4549.529
XS Rating Curve= 0
Skew Angle= 25
Exp/Cntr=.5,.3

Type RM Length L Ch R = 2 ,243013  ,,,
BEGIN DESCRIPTION:
FM 2234 Rd
END DESCRIPTION:
Bridge Culvert--1,0,-1,-1, 0
Deck Dist Width WeirC Skew NumUp NumDn MinLoCord MaxHiCord MaxSubmerge Is_Ogee
25,110,2.6,25, 7, 8, , , .95, 0, 0,0,,
4006.787 4033.074463.5664463.5664599.5124599.5125184.081
    61.5    62.5    62.5    64.1    64.1    62.7    62.7
       0       0       0       0       0       0       0
 3974.16 4033.074463.5664463.5664599.5124599.5125184.0815274.711
    62.5    62.5    62.5    64.1    64.1    62.7    62.7    62.2
       0       0       0       0       0       0       0       0
BR Coef=-1 , 1 , 0 ,, 0 ,,,.8,-1,,0,
WSPro=,,,, 1 ,,,, 0 ,,,, 0 ,,,,-1 ,-1 ,-1 , 0 , 0 , 0 , 0 , 0
Multiple Barrel Culv=2,8,8,110,.012,.4,1,8,1,53.45,53.45, 3,Culvert #1  , 0 ,25
 4501.95 4490.95 4510.65 4499.65 4519.35 4508.35
Culvert Bottom n=.012
Culvert=2,8,7.6,110,.012,.4,1,8,1,53.45,4528.05,53.45,4517.05,Culvert #2  , 0 ,25
Culvert Bottom n=.012
BC Design=,, 0 ,, 0 ,,,,,,
BC HTab HWMax=67.6

Type RM Length L Ch R = 1 ,242938.7,23.56,100.84,577.87
XS GIS Cut Line= 6
 3101270.261054213779261.4389529     3100386.721    13776602.925
     3100016.263    13776147.648     3098782.913    13776076.602
     3098483.663    13775857.713 3097720.428155213773938.8351479
#Sta/Elev= 30
 634.538    59.91000.401   61.261210.229   59.021315.234   60.252231.846   59.09
2389.662   61.182575.899   60.732621.341   63.062790.767   64.192819.432   61.31
2898.309   61.082940.968   63.563928.329   59.943963.384   63.124015.958   58.88
4036.233   60.89 4468.56   60.644485.915   55.61 4488.65   53.05 4520.78   53.05
4540.466   61.144550.283   59.274564.791   62.034573.637   57.954608.304   59.23
4632.212   56.474673.059    60.35223.39261.53995 6776.5563.879837694.326   64.47
#Mann= 5 ,-1 , 0
 634.538     .07       0 4468.56     .04       04540.466     .07       0
5223.392     .12       0 6776.55     .07       0
#XS Ineff= 5 ,-1
 634.538 2784.98   63.51 2784.984483.505    62.54523.382 6307.17    62.5
 6307.17 7098.98   63.33 7098.987694.326    62.5
Permanent Ineff=
       F       F       F       F       F
#Block Obstruct= 1 ,-1
 5430.92 6927.09   63.02
Bank Sta=4468.56,4540.466
XS Rating Curve= 0
Skew Angle= 25
Exp/Cntr=.5,.3

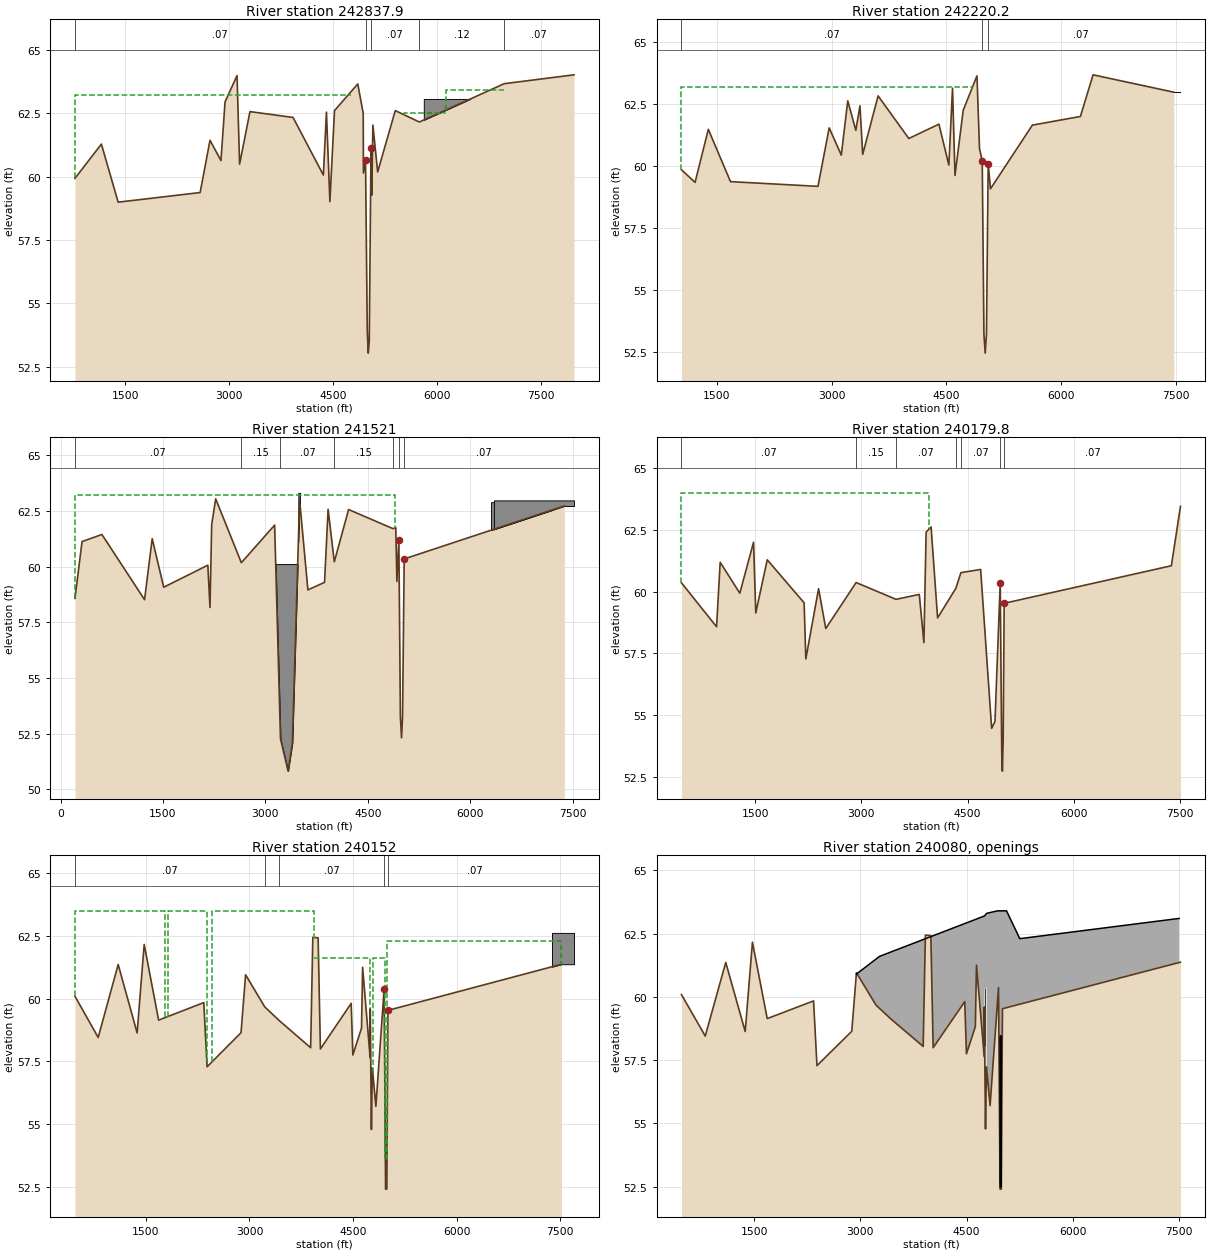
Type RM Length L Ch R = 1 ,242837.9,52.46,617.66,984.64
XS GIS Cut Line= 6
     3101398.367    13779572.624     3100403.131    13776584.301
     3100043.784    13776111.984     3099609.393    13776094.108
     3098575.431     13774995.76     3098014.407    13773593.339
#Sta/Elev= 30
  775.13   59.93 1155.95   61.28 1397.57   58.99 2580.24   59.37 2722.53   61.43
 2880.63   60.63 2939.44   62.94 3112.35   63.98  3149.4   60.49 3298.88   62.56
 3920.27   62.33 4357.44   60.06 4401.88   62.54 4451.68   59.01  4518.3    62.6
 4853.96   63.65 4932.43   62.49 4935.28   60.14 4965.51   60.64 4990.84   53.92
 5004.84   53.04 5019.45    53.5 5044.85   61.14 5055.68   59.27 5071.69   62.03
 5140.76   60.18 5394.68    62.6 5741.33   62.15 6964.89   63.66 7972.52   64.01
#Mann= 5 ,-1 , 0
  775.13     .07       0 4965.51     .04       0 5044.85     .07       0
 5741.33     .12       0 6964.89     .07       0
#XS Ineff= 3 ,-1
  775.13 4759.95    63.2 5515.36 6125.14   62.49 6125.14 6962.46    63.4
Permanent Ineff=
       F       F       F
#Block Obstruct= 1 ,-1
 5805.77 7045.08   63.06
Bank Sta=4965.51,5044.85
XS Rating Curve= 0
Exp/Cntr=.3,.1

Type RM Length L Ch R = 1 ,242220.2,1461.62,699.21,354.17
XS GIS Cut Line= 4
     3101446.804    13779557.148     3100622.182    13777085.902
     3099664.492    13774599.267     3099243.523    13773511.241
#Sta/Elev= 30
1038.335   59.86 1216.45   59.35 1389.65   61.49 1679.65   59.38 2823.18   59.19
  2969.8   61.55 3127.93   60.45 3212.45   62.64 3317.94   61.45 3372.04   62.44
 3407.91   60.48  3609.2   62.84 4010.65   61.12  4404.1    61.7 4533.93   60.05
 4582.16   63.15  4614.3   59.63 4721.86   62.26 4901.69   63.65 4935.04   60.71
 4970.57   60.21  4992.7   53.22 5009.19   52.46 5025.85   53.23 5048.39   60.11
 5078.29   59.09 5626.06   61.66 6253.85   62.01 6419.64   63.69 7474.84   62.99
#Mann= 3 ,-1 , 0
1038.335     .07       0 4970.57     .04       0 5048.39     .07       0
#XS Ineff= 1 ,-1
 1015.93 4830.49    63.2
Permanent Ineff=
       F
#Block Obstruct= 1 ,-1
 6805.46    7562      63
Bank Sta=4970.57,5048.39
XS Rating Curve= 0
Exp/Cntr=.3,.1

Type RM Length L Ch R = 1 ,241521  ,305.52,1341.23,1587.56
XS GIS Cut Line= 5
     3102876.313    13779688.296     3101946.974    13776696.289
      3100034.18    13774816.474     3099919.113    13774510.361
     3099558.277    13773550.585
#Sta/Elev= 30
 212.255   58.57  315.54   61.12  606.57   61.44 1231.43   58.51 1343.17   61.25
 1511.83   59.07 2158.13   60.06 2189.55   58.16 2214.47   61.88 2273.25   63.04
2649.13560.17039 3136.61   61.863222.51552.26012 3333.74   50.81 3397.11   52.09
 3502.27   62.99 3624.01   58.95 3867.85   59.29 3919.75   62.574010.91560.20976
 4220.15   62.564870.98561.69989 4911.35   61.75 4927.44   59.33 4956.01   61.21
 4978.94   53.24 4995.73   52.31  5010.9    53.3 5034.57   60.34 7379.54   62.72
#Mann= 7 ,-1 , 0
 212.255     .07       02649.135     .15       03222.515     .07       0
4010.915     .15       04870.985     .07       0 4956.01     .04       0
 5034.57     .07       0
#XS Ineff= 1 ,-1
       0    4895    63.2
Permanent Ineff=
       F
#Block Obstruct= 4 ,-1
 3085.32 3485.78   60.11 3484.05 3507.24   63.31 6307.17 7217.29   62.89
 6348.74 7521.79   62.97
Bank Sta=4956.01,5034.57
XS Rating Curve= 0
Exp/Cntr=.3,.1

Type RM Length L Ch R = 1 ,240179.8,50.51,27.73,22.51
XS GIS Cut Line= 6
      3103162.04    13779687.334     3102512.254    13777579.891
     3102467.795    13777021.752     3102411.643    13776787.996
      3101992.15    13775404.188     3101168.946    13772948.093
#Sta/Elev= 30
  461.15   60.36  956.55   58.58 1007.75   61.19 1284.73   59.94 1478.65      62
 1510.05   59.14 1671.94   61.29  2192.3   59.55  2216.4   57.28 2396.26   60.12
 2497.81   58.51    2926   60.37  3489.4   59.69 3817.35   59.89 3882.69   57.94
 3914.04   62.41 3984.23   62.62 4075.96   58.94 4334.49   60.14 4404.91   60.77
 4683.43    60.9 4838.81   54.47 4885.87   54.75 4960.03   60.37 4981.37   53.45
 4990.36   52.74 5001.66   53.98 5015.54   59.53 7375.38   61.05 7503.58   63.45
#Mann= 7 ,-1 , 0
  461.15     .07       0    2926     .15       0  3489.4     .07       0
 4334.49     .15       0 4404.91     .07       0 4960.03     .04       0
 5015.54     .07       0
#XS Ineff= 1 ,-1
  327.65 3949.94      64
Permanent Ineff=
       F
Bank Sta=4960.03,5015.54
XS Rating Curve= 0
Exp/Cntr=.5,.3

Type RM Length L Ch R = 1 ,240152  ,26.42,143.57,151.64
XS GIS Cut Line= 6
 3103205.055532313779672.9902152     3102567.111    13777593.275
     3102525.721    13777083.876     3102011.161    13775397.958
      3101533.92     13774045.67     3101197.623    13772933.754
#Sta/Elev= 30
 473.685   60.09  809.56   58.45 1099.19   61.36 1373.57   58.63 1475.74   62.16
 1684.74   59.14 2338.68   59.84 2386.77   57.28 2878.08   58.64 2944.19   60.95
3221.17559.669863432.51559.11982 3886.22   58.04 3917.57   62.44 3994.37   62.42
 4027.28   57.99 4473.09   59.81 4497.15   57.75  4622.9   58.82 4638.57   61.25
 4748.29   57.63    4749    59.6    4766   54.78 4779.64   57.23 4830.77    55.7
 4950.03   60.37 4971.37    52.4  4989.4    52.4 5005.54   59.53 7518.53   61.37
#Mann= 5 ,-1 , 0
 473.685     .07       03221.175     .15       03432.515     .07       0
 4950.03     .04       0 5005.54     .07       0
#XS Ineff= 6 ,-1
  473.69    1780    63.5    4992 7518.53    62.3 3940.84    4749    61.6
  4785.8    4968    61.6    2451 3940.84    63.5    1820 2382.31    63.5
Permanent Ineff=
       F       F       F       F       F       F
#Block Obstruct= 1 ,-1
 7381.11 7699.66   62.62
Bank Sta=4950.03,5005.54
XS Rating Curve= 0
Exp/Cntr=.5,.3

Type RM Length L Ch R = 4 ,240080  ,,,
BEGIN DESCRIPTION:
Railroad
END DESCRIPTION:
Bridge Culvert--1,0,-1,-1, 0
Deck Dist Width WeirC Skew NumUp NumDn MinLoCord MaxHiCord MaxSubmerge Is_Ogee
30,70,2.6,0, 10, 10, , , .95, 0, 0,0,,
    2944    3270  4753.9  4753.9  4781.1  4781.1    4937    5063    5250    7500
    60.9    61.6    63.2    63.2    63.3    63.3    63.4    63.4    62.3    63.1
       0       0       0   60.34   60.36       0       0       0       0       0
    3229    3270  4766.9  4766.9  4794.1  4794.1    4937    5063    5250    7500
    61.5    61.6    63.2    63.2    63.3    63.3    63.4    63.4    62.3    63.1
       0       0       0   60.32   60.47       0       0       0       0       0
Pier Skew, UpSta & Num, DnSta & Num=  ,4754.5, 2 ,4767.5, 2 , 0 , 0 , 0 ,,
     1.2     1.2
       0      62
     1.2     1.2
       0      62
BR Coef=-1 , 1 , 0 ,1.25, 0 ,,,.8,0,2,0,
WSPro=,,,, 1 ,,,, 0 ,,,, 0 ,,,,-1 ,-1 ,-1 , 0 , 0 , 0 , 0 , 0
Multiple Barrel Culv=1,6,,100,.024,.9,1,2,3,52.47,52.41, 2,Culvert #1  , 0 ,30
    4976    4981    4984    4989
Culvert Bottom n=.024
BC Mult= 3 ,400,4920,400,4930
BC Mult= 2 ,4840,8000,4870,8000
BC Design=,, 0 ,, 0 ,,,,,,
BC HTab HWMax=63.07

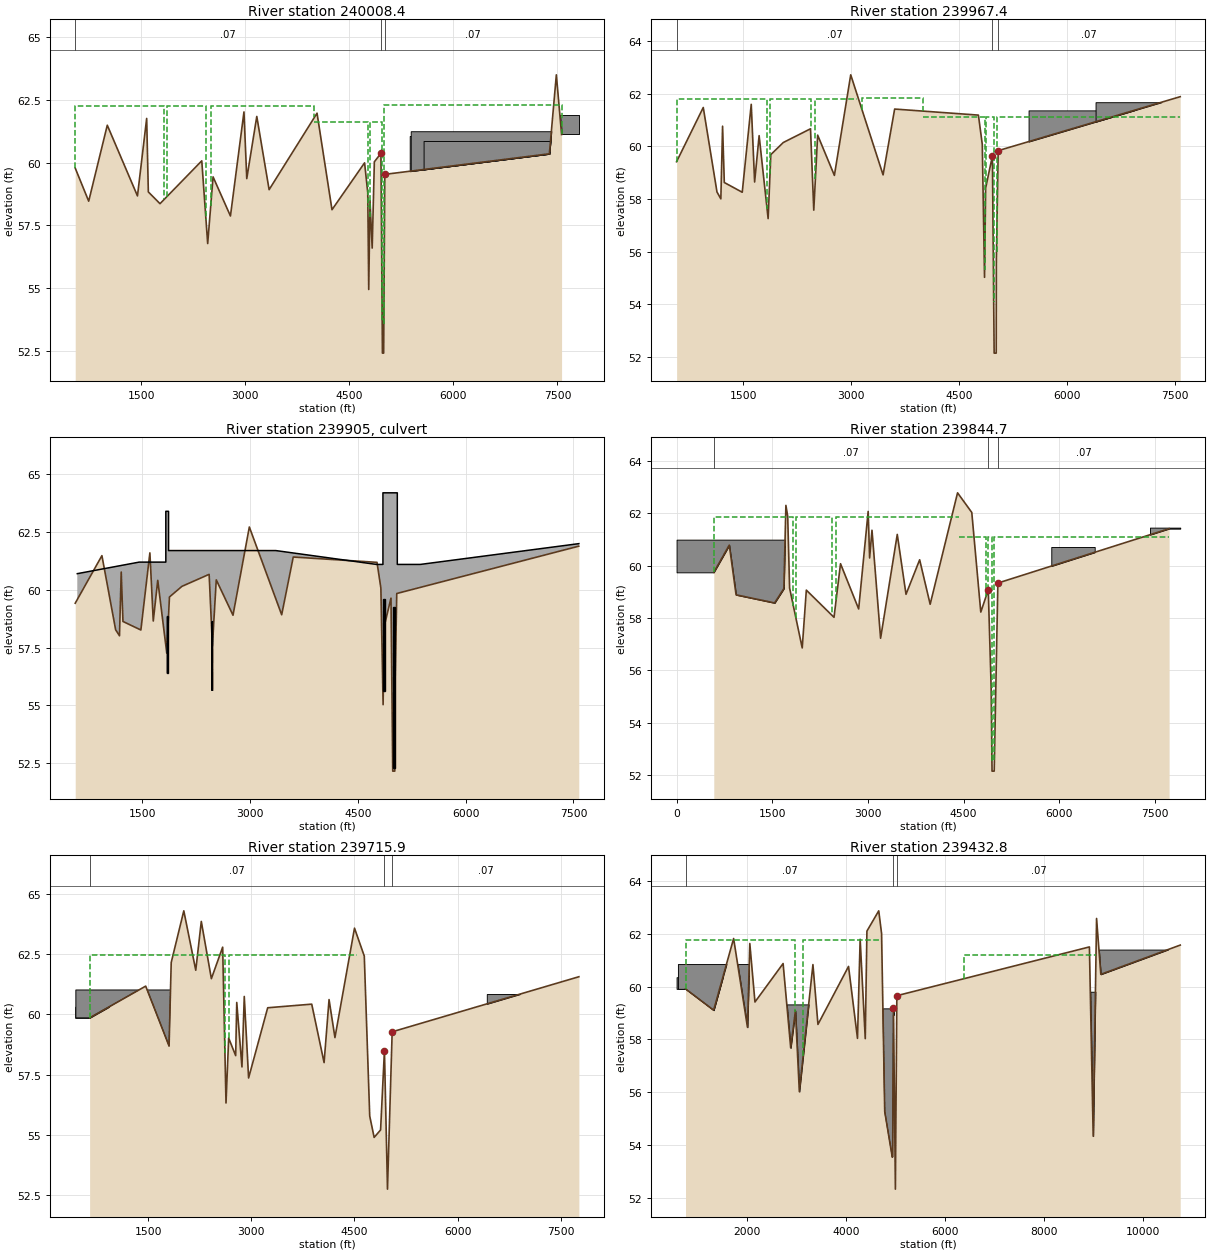
Type RM Length L Ch R = 1 ,240008.4,21.08,41.02,29.38
XS GIS Cut Line= 6
     3103220.653    13779676.143     3102594.185    13777580.465
     3102595.469    13777009.239     3102046.295    13775159.772
     3101867.182    13774570.473      3101346.37      13772943.8
#Sta/Elev= 30
 547.535   59.78  741.81   58.46 1009.79   61.49 1444.91   58.67 1577.49   61.76
  1601.6   58.83 1769.89   58.36 2372.01   60.07 2457.35   56.77 2534.86   59.43
 2785.32   57.87 2980.32   62.02 3020.66   59.36 3165.17   61.84 3342.94   58.92
 4033.73   61.97 4249.29   58.12 4719.22   59.99  4764.9    58.8    4779   54.94
 4797.54   58.48 4828.83   56.59 4860.08   60.03 4955.03   60.37 4976.37    52.4
  4994.4    52.4 5010.54   59.53 7383.42   60.35 7483.88    63.5  7559.3   61.12
#Mann= 3 ,-1 , 0
 547.535     .07       0 4955.03     .04       0 5010.54     .07       0
#XS Ineff= 6 ,-1
  547.54    1830   62.27 3995.45    4767    61.6  4794.1    4973    61.6
    4997  7559.3    62.3    2501 3995.45   62.27    1870 2433.31   62.27
Permanent Ineff=
       F       F       F       F       F       F
#Block Obstruct= 4 ,-1
 5369.74 7690.56   61.06 5384.21 7482.71   61.25 5569.97 7526.73   60.86
 7481.23 7808.87   61.89
Bank Sta=4955.03,5010.54
XS Rating Curve= 0
Exp/Cntr=.5,.3

Type RM Length L Ch R = 1 ,239967.4,181.39,122.73,95.65
XS GIS Cut Line= 5
     3103240.091    13779680.166     3102615.027    13777576.991
     3102615.944    13777011.131     3102083.457    13775176.773
     3101388.417      13772950.7
#Sta/Elev= 30
 571.175   59.42  942.39   61.48 1133.13   58.27 1186.86   58.01 1210.74   60.77
 1234.87   58.63 1484.18   58.26 1609.37    61.6 1656.31   58.65 1718.91   60.41
 1844.09   57.26 1881.54   59.69 2055.17   60.15 2433.31   60.67 2478.73   57.58
 2532.62   60.43 2765.27    58.9  2992.4   62.72 3442.13   58.92 3603.05   61.42
 4767.49   61.19 4821.34   60.08 4852.58   55.03  4868.2   58.42  4962.1   59.64
 4986.33   52.15 5015.02   52.15 5017.07   55.68 5042.54   59.84 7573.27   61.89
#Mann= 3 ,-1 , 0
 571.175     .07       0  4962.1     .04       0 5042.54     .07       0
#XS Ineff= 8 ,-1
  571.18    1830   61.82    2501 3076.22   61.82 3076.22 3149.03    61.1
 3149.03 3995.45   61.84 3995.45 4853.85    61.1 4878.85    4980    61.1
    5019 7573.27    61.1    1870 2433.31   61.82
Permanent Ineff=
       F       F       F       F       F       F       F       F
#Block Obstruct= 2 ,-1
 5464.77 7454.31   61.37 6396.12 7711.61   61.68
Bank Sta=4962.1,5042.54
XS Rating Curve= 0
Exp/Cntr=.5,.3

Type RM Length L Ch R = 2 ,239905  ,,,
BEGIN DESCRIPTION:
FM 521 Rd
END DESCRIPTION:
Bridge Culvert--1,0,-1,-1, 0
Deck Dist Width WeirC Skew NumUp NumDn MinLoCord MaxHiCord MaxSubmerge Is_Ogee
30,75,2.6,0, 14, 14, , , .95, 0, 0,0,,
     600    1460    1831    1831    1869    1869    3360    4760    4850    4850
    5050    5050    5370    7575
    60.7    61.2    61.2    63.4    63.4    61.7    61.7    61.1    61.1    64.2
    64.2    61.1    61.1      62
       0       0       0       0       0       0       0       0       0       0
       0       0       0       0
     600    1460    1831    1831    1869    1869    3360    4760    4850    4850
    5050    5050    5370    7575
    60.7    61.2    61.2    63.4    63.4    61.7    61.7    61.1    61.1    64.2
    64.2    61.1    61.1      62
       0       0       0       0       0       0       0       0       0       0
       0       0       0       0
BR Coef=-1 , 1 , 0 ,, 0 ,,,.8,-1,,0,
WSPro=,,,, 1 ,,,, 0 ,,,, 0 ,,,,-1 ,-1 ,-1 , 0 , 0 , 0 , 0 , 0
Multiple Barrel Culv=2,2.5,5.4,45,.012,.5,1,10,1,56.38,56.38, 3,Culvert #4  , 0 ,25
  1843.5  1843.5    1850    1850  1856.5  1856.5
Culvert Bottom n=.012
Multiple Barrel Culv=1,3,,34,.024,.9,1,2,3,55.63,55.63, 2,Culvert #3  , 0 ,82.73
 2475.03 2475.03 2480.03 2480.03
Culvert Bottom n=.024
Multiple Barrel Culv=2,4,5.83,47,.012,.5,1,10,1,55.62,55.37, 3,Culvert #2  , 0 ,50
    4859    4864 4866.33 4871.33 4873.67 4878.67
Culvert Bottom n=.012
Multiple Barrel Culv=2,7,13.6,75,.012,.5,1,10,1,52.27,52.27, 2,Culvert #1  , 0 ,30
  4992.5  4957.5  5007.5  4972.5
Culvert Bottom n=.012
BC Design=,, 0 ,, 0 ,,,,,,
BC HTab HWMax=62.72

Type RM Length L Ch R = 1 ,239844.7,113.5,128.84,95.13
XS GIS Cut Line= 6
     3103428.933    13779703.063     3102767.466    13777494.109
     3102759.732    13776960.117     3102275.451    13775527.908
     3102228.575    13775368.071     3101465.198    13772860.674
#Sta/Elev= 30
  584.29   59.75  826.89   60.79  933.16   58.89 1537.93   58.58 1682.43   59.13
 1714.36   62.31 1742.67   61.89 1772.28   59.15 1970.17   56.86 2034.74   59.07
 2468.78   58.03 2570.84   60.08 2855.35   58.35 3004.28   62.08 3027.02    60.3
 3064.28   61.36  3199.3   57.23  3460.6    61.2 3597.64   58.91 3811.61   60.23
  3976.3   58.53 4406.05   62.79 4628.98   62.04 4770.25   58.23 4887.45   59.08
  4932.8   55.34 4946.73   52.15 4980.44   52.15 5038.11   59.34 7723.67   61.42
#Mann= 3 ,-1 , 0
  584.29     .07       0 4887.45     .04       0 5038.11     .07       0
#XS Ineff= 6 ,-1
  584.29    1830   61.87 2501.81 4432.31   61.87    4984 7723.67    61.1
 4432.31    4851    61.1    4885    4945    61.1    1870  2434.3   61.87
Permanent Ineff=
       F       F       F       F       F       F
#Block Obstruct= 4 ,-1
 5875.76 6556.23   60.72 7423.36 7897.44   61.46 7490.33 7827.08   60.81
       0    1710      61
Bank Sta=4887.45,5038.11
XS Rating Curve= 0
Exp/Cntr=.5,.3

Type RM Length L Ch R = 1 ,239715.9,206.16,283.02,964
XS GIS Cut Line= 6
     3103536.325    13779718.405     3102856.745    13777401.961
     3102842.788    13776978.431     3102351.814     13775504.02
      3102305.39     13775345.72      3101572.59    13772891.357
#Sta/Elev= 30
 647.195   59.86  1462.3   61.18 1802.32   58.69 1833.58   62.16 2016.77   64.31
 2190.76   61.84 2271.28   63.87 2417.92   61.49 2582.27    62.8 2630.83   56.32
 2669.44   59.02 2771.51   58.29 2787.15    60.5 2862.82   57.82 2896.57   60.75
 2959.51   57.36 3237.38   60.28 3878.13   60.43 4057.92      58 4130.14   60.62
    4216   59.04 4500.54   63.59 4642.81   62.43 4721.85   55.78 4786.28   54.89
 4879.93    55.2  4936.1    58.5 4980.36   52.74 5048.53   59.28 7765.44   61.57
#Mann= 3 ,-1 , 0
 647.195     .07       0  4936.1     .04       0 5048.53     .07       0
#XS Ineff= 2 ,-1
  364.05 2615.19   62.46 2669.44 4541.52   62.46
Permanent Ineff=
       F       F
#Block Obstruct= 3 ,-1
  436.86 1310.58   60.32  445.96    2300   61.02 6425.48 7790.67   60.85
Bank Sta=4936.1,5048.53
XS Rating Curve= 0
Exp/Cntr=.3,.1

Type RM Length L Ch R = 1 ,239432.8,56.29,967.14,1359.18
XS GIS Cut Line= 5
     3103762.591    13779765.324     3102842.137     13776692.06
     3102553.665    13775761.588     3103563.999    13774189.959
     3104009.329     13770263.67
#Sta/Elev= 30
  754.09   59.92 1323.55   59.11    1727   61.83 2007.09   58.46 2054.07   61.64
 2158.53   59.42 2727.38   60.88 2881.15   57.68 2976.35   59.08 3055.66   56.02
 3330.47   60.84    3432   58.57 4050.27   60.77 4231.36   58.04  4284.9    61.8
 4388.41   58.03 4421.93   62.11 4660.88   62.88  4718.2   62.02 4781.96   55.26
 4935.27   53.53 4942.93   53.55 4958.93   59.19 4997.49   52.32 5026.97   59.66
 8920.01   61.51  8996.7   54.33 9064.77   62.59 9150.49   60.4710756.22   61.58
#Mann= 3 ,-1 , 0
  754.09     .07       0 4958.93     .04       0 5026.97     .07       0
#XS Ineff= 3 ,-1
    6380    9060    61.2  754.09 2977.55   61.77 3133.19 4696.25   61.77
Permanent Ineff=
       F       F       F
#Block Obstruct= 7 ,-1
  573.38 1542.66   60.36  600.68 1583.62   60.86 1648.75 2035.84   60.86
 2634.81 3317.41   59.33 4675.28 4960.43   59.16 8873.72 9146.76   59.81
 9075.8410921.22   61.41
Bank Sta=4958.93,5026.97
XS Rating Curve= 0
Exp/Cntr=.3,.1

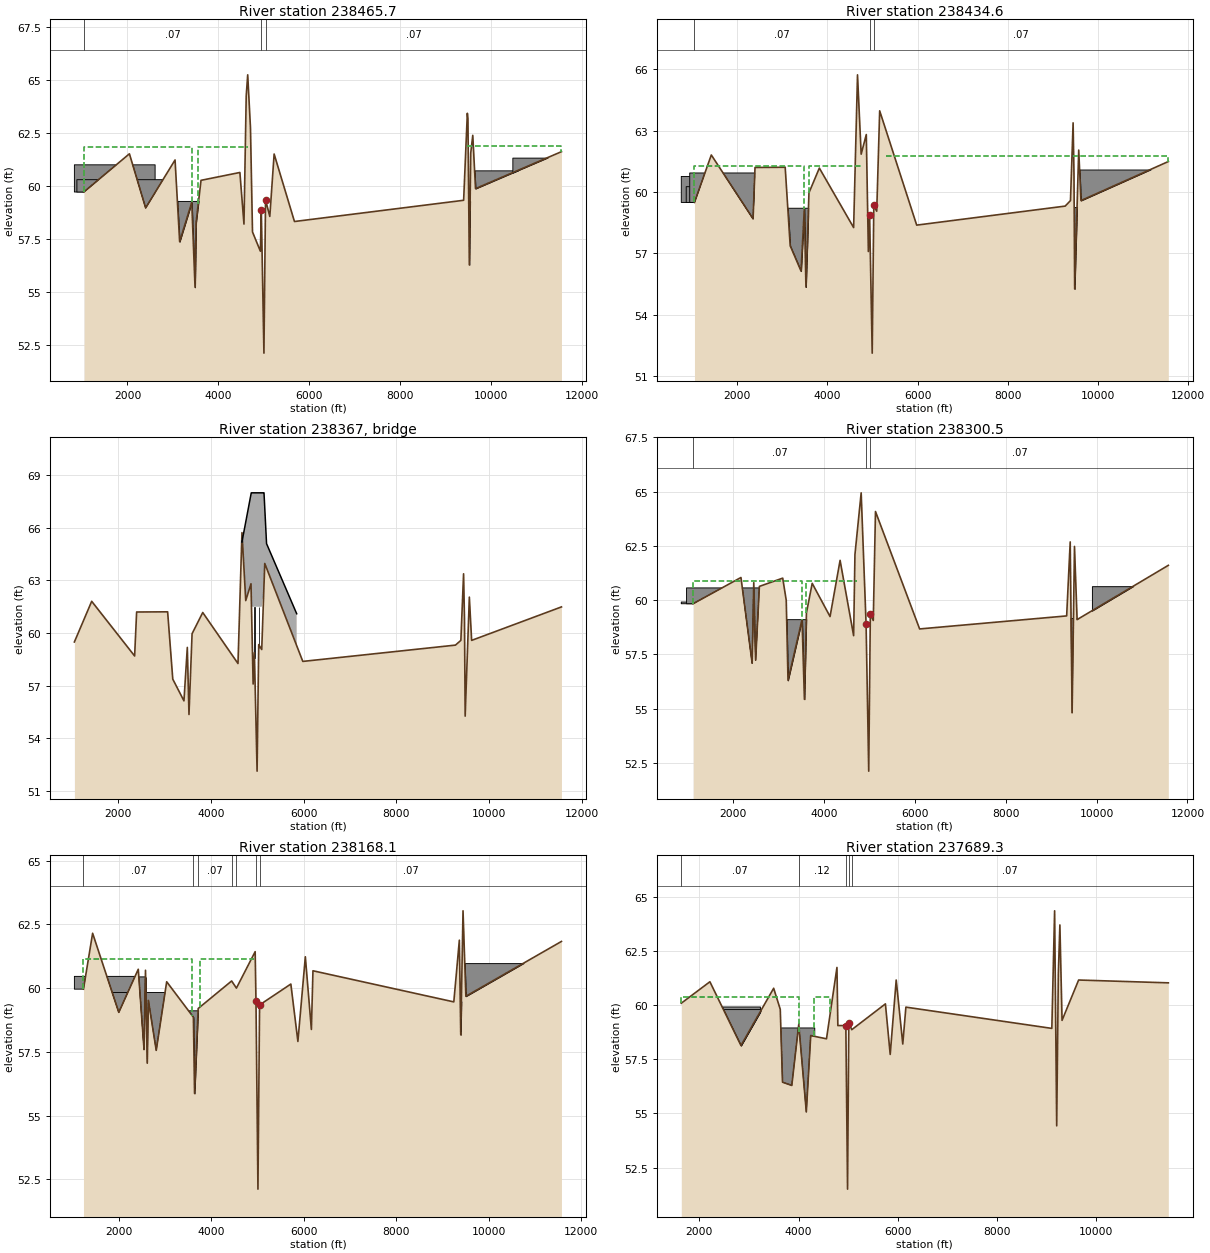
Type RM Length L Ch R = 1 ,238465.7,46.96,31.14,30.3
XS GIS Cut Line= 6
     3103832.408    13779784.711     3102957.519    13776735.275
     3103174.959    13776256.441     3103635.974    13776115.357
     3104371.653    13775579.347     3104355.941    13770196.148
#Sta/Elev= 30
 1040.64   59.71 2042.71   61.51  2399.9   58.96 3046.23   61.22 3147.56   57.37
  3413.6   59.22 3485.72   55.22 3508.87   58.27 3617.28   60.26  4471.8   60.63
 4561.61    58.2 4611.04   64.24 4643.99   65.23  4704.6   62.74 4749.18   57.83
 4922.71   56.92 4942.63   58.88 5000.59   52.12 5035.92   59.34 5129.72   58.56
 5224.94    61.5 5671.91   58.32 9392.07   59.32 9473.55   63.42 9486.49   63.16
 9517.19   56.28 9547.88   61.54 9592.92   62.38 9653.59   59.8711542.92   61.61
#Mann= 3 ,-1 , 0
 1040.64     .07       0 4942.63     .04       0 5035.92     .07       0
#XS Ineff= 4 ,-1
    5222    9460    61.1 9460.7511542.92   61.87 1040.64  3413.6   61.81
 3556.49 4641.64   61.81
Permanent Ineff=
       F       F       F       F
#Block Obstruct= 6 ,-1
  832.76 2607.51   60.99  887.37 2784.98   60.29 3030.72  3604.1   59.29
 9406.14 9651.88   59.29  9591.410652.33   60.73 10463.411606.24   61.33
Bank Sta=4942.63,5035.92
XS Rating Curve= 0
Exp/Cntr=.5,.3

Type RM Length L Ch R = 1 ,238434.6,69.89,134.09,127
XS GIS Cut Line= 6
     3103894.509    13779784.711     3103001.388      13776734.9
     3103212.418     13776269.86     3104276.163    13775775.589
     3104397.958    13775595.028      3104416.71    13770189.396
#Sta/Elev= 30
1056.785   59.49 1429.92   61.81 2355.53   58.69 2398.63    61.2 3067.15   61.21
 3178.02   57.37 3418.97   56.13 3491.47   59.18 3527.34   55.35 3593.98   59.96
 3824.08   61.17 4583.94   58.26 4669.88   65.73 4750.91   61.85 4864.47   62.81
  4910.5   57.09 4937.63   58.88 4995.59   52.12 5030.92   59.34  5095.9   59.06
 5161.13   63.97 5981.45   58.38 9271.97   59.31 9389.45   59.58 9447.65   63.38
 9467.16   60.85 9482.17   55.26 9572.18   62.05 9621.58   59.5811558.02   61.49
#Mann= 3 ,-1 , 0
1056.785     .07       0 4937.63     .04       0 5030.92     .07       0
#XS Ineff= 5 ,-1
 4750.85    4878      60    5122 5296.93      60 5296.9311558.02   61.78
 1056.79 3491.47   61.28 3593.98 4750.85   61.28
Permanent Ineff=
       F       F       F       F       F
#Block Obstruct= 6 ,-1
  764.51 2771.33   60.76  873.72 2689.42   60.26   951.9 2765.13   60.93
 3030.72 3576.79   59.23 9365.19 9651.88   59.26  9559.9 11912.4    61.1
Bank Sta=4937.63,5030.92
XS Rating Curve= 0
Exp/Cntr=.5,.3

Type RM Length L Ch R = 3 ,238367  ,,,
BEGIN DESCRIPTION:
FM 2234 Rd
END DESCRIPTION:
Bridge Culvert--1,0,-1,-1, 0
Deck Dist Width WeirC Skew NumUp NumDn MinLoCord MaxHiCord MaxSubmerge Is_Ogee
30,75,2.6,0, 10, 9, , , .95, 0, 0,0,,
    4669    4720    4870    4875    4875    5140    5140    5145    5200    5850
    65.2    65.9      68      68      68      68      68      68    65.1    61.1
       0       0       0       0    61.5    61.5       0       0       0       0
    4720    4870    4875    4875    5112    5112    5130    5200    5850
    65.9      68      68      68      68      68      68    65.1    61.1
       0       0       0    61.5    61.5       0       0       0       0
Pier Skew, UpSta & Num, DnSta & Num=  ,4940, 2 ,4925, 2 , 0 , 0 , 0 ,,
       3       3
       0      66
       3       3
       0      66
Pier Skew, UpSta & Num, DnSta & Num=  ,5030, 2 ,5015, 2 , 0 , 0 , 0 ,,
       3       3
       0      66
       3       3
       0      66
Abutment Skew #Up #Dn= , 2 , 2
    4883    4921
    61.5    58.7
    4883    4921
    61.5    58.7
Abutment Skew #Up #Dn= , 2 , 2
    5080    5130
      59    61.5
    5050    5100
      59    61.5
BR Coef=-1 , 1 , 1 ,.9, 0 ,,,.8,0,1.2,0,
WSPro=,,,, 1 ,,,, 0 ,,,, 0 ,,,,-1 ,-1 ,-1 , 0 , 0 , 0 , 0 , 0
BC Design=,, 0 ,, 0 ,,,,,,
BC HTab HWMax=65.73

Type RM Length L Ch R = 1 ,238300.5,114.48,132.36,119.2
XS GIS Cut Line= 6
     3103947.739    13779766.968     3103093.395    13776787.177
      3103268.69    13776369.615     3104326.741    13775843.147
     3104517.714    13775563.162     3104466.226    13770184.894
#Sta/Elev= 30
1119.115   59.83 2173.57   61.04 2420.29   57.09 2455.58    60.8  2496.2   57.23
  2579.1   60.63 3092.65   61.01 3170.02   59.99 3209.13    56.3 3517.87    59.1
  3570.2   55.43 3614.79   59.41 3741.48   60.77 4134.44   59.24 4355.39   61.83
  4653.4   58.36 4682.33    62.1 4819.33   64.94 4927.63   58.88 4985.59   52.12
 5020.92   59.34  5085.9   59.06 5134.18   64.08 6105.95   58.67 9341.81   59.27
 9420.03   62.68 9461.87   54.81 9514.13   62.47 9571.71    59.111579.73    61.6
#Mann= 3 ,-1 , 0
1119.115     .07       0 4927.63     .04       0 5020.92     .07       0
#XS Ineff= 5 ,-1
 5392.4911579.73    60.9    5122 5392.49      60  4737.2    4878      60
 1119.12 3517.87   60.87 3614.79  4737.2   60.87
Permanent Ineff=
       F       F       F       F       F
#Block Obstruct= 5 ,-1
  860.07 2662.12   59.91  976.35    3000   60.56 2962.46 3822.53   59.12
 9228.67 9610.92   59.15 9897.6111918.09   60.64
Bank Sta=4927.63,5020.92
XS Rating Curve= 0
Exp/Cntr=.5,.3

Type RM Length L Ch R = 1 ,238168.1,450.81,478.79,81.94
XS GIS Cut Line= 6
     3104027.583    13779749.224     3103233.623    13776820.191
     3103396.388    13776473.278     3104360.407    13775916.031
     3104596.536    13775545.155     3104529.247    13770175.891
#Sta/Elev= 30
 1229.15   59.96 1427.39   62.15 1993.41   59.05 2415.45   60.74 2540.41   57.59
 2571.65    60.7  2610.5   57.06 2634.13   59.52 2804.17   57.56  3030.3   60.25
 3608.56   58.86  3633.8   55.87 3712.01    59.2 4436.18   60.28 4539.63      60
  4945.5   61.43    4963    59.5 5005.59   52.12 5040.92   59.34 5717.73   60.16
 5870.22   57.91 6031.34   61.23 6162.09   58.38 6196.31   60.68 9244.75   59.46
 9364.78   61.88 9394.79   58.17 9444.16   63.03 9505.51   59.6811574.41   61.83
#Mann= 7 ,-1 , 0
 1229.15     .07       0 3608.56     .12       0 3712.01     .07       0
 4436.18     .12       0 4539.63     .07       0    4963     .04       0
 5040.92     .07       0
#XS Ineff= 4 ,-1
 6006.83 6020.48   60.38 6020.4811549.49   60.84 1229.15 3586.94   61.16
 3743.13 4914.68   61.16
Permanent Ineff=
       F       F       F       F
#Block Obstruct= 6 ,-1
 1032.88  2419.5   60.46 1392.49 3194.54   59.83  2408.6 2580.65   60.44
 3030.72 3781.57   59.13 9269.62 9488.05   59.48 9457.88 11732.9   60.98
Bank Sta=4963,5040.92
XS Rating Curve= 0
Exp/Cntr=.3,.1

Type RM Length L Ch R = 1 ,237689.3,896,1080.4,516
XS GIS Cut Line= 6
     3104309.063    13779734.964      3103888.75     13777398.58
     3104258.296    13776061.175     3104431.661    13775947.132
     3104683.077    13775544.867     3104614.774    13770166.889
#Sta/Elev= 30
 1635.16   60.08 2212.36   61.07 2839.15   58.13 3498.53   60.77 3631.67    59.8
 3677.39   56.44 3864.15   56.29 4004.81    59.1 4157.06   55.07  4246.2   58.59
 4564.35   58.44 4775.31   61.73 4793.33   59.05 4954.39   59.05 4989.09   51.51
 5014.45   59.19 5073.69   58.86 5752.63   60.05  5849.3   57.72 5970.37   61.15
 6102.96    58.2 6165.76    59.9 9109.47   58.92 9165.64   64.34 9207.62   54.43
 9240.66   61.43 9272.04   63.69 9315.69   59.29    9650   61.1511459.52   61.02
#Mann= 5 ,-1 , 0
 1635.16     .07       0 4004.81     .12       0 4954.39     .04       0
 5014.45     .12       0 5073.69     .07       0
#XS Ineff= 3 ,-1
 5965.87  9815.7   60.35 1635.16  4017.6   60.35 4308.44 4641.64   60.35
Permanent Ineff=
       F       F       F
#Block Obstruct= 4 ,-1
 1676.96 2062.36   60.05 2244.48 3221.14   59.93 2252.56 3235.49   59.81
 3467.58 4327.65   58.94
Bank Sta=4954.39,5014.45
XS Rating Curve= 0
Exp/Cntr=.3,.1