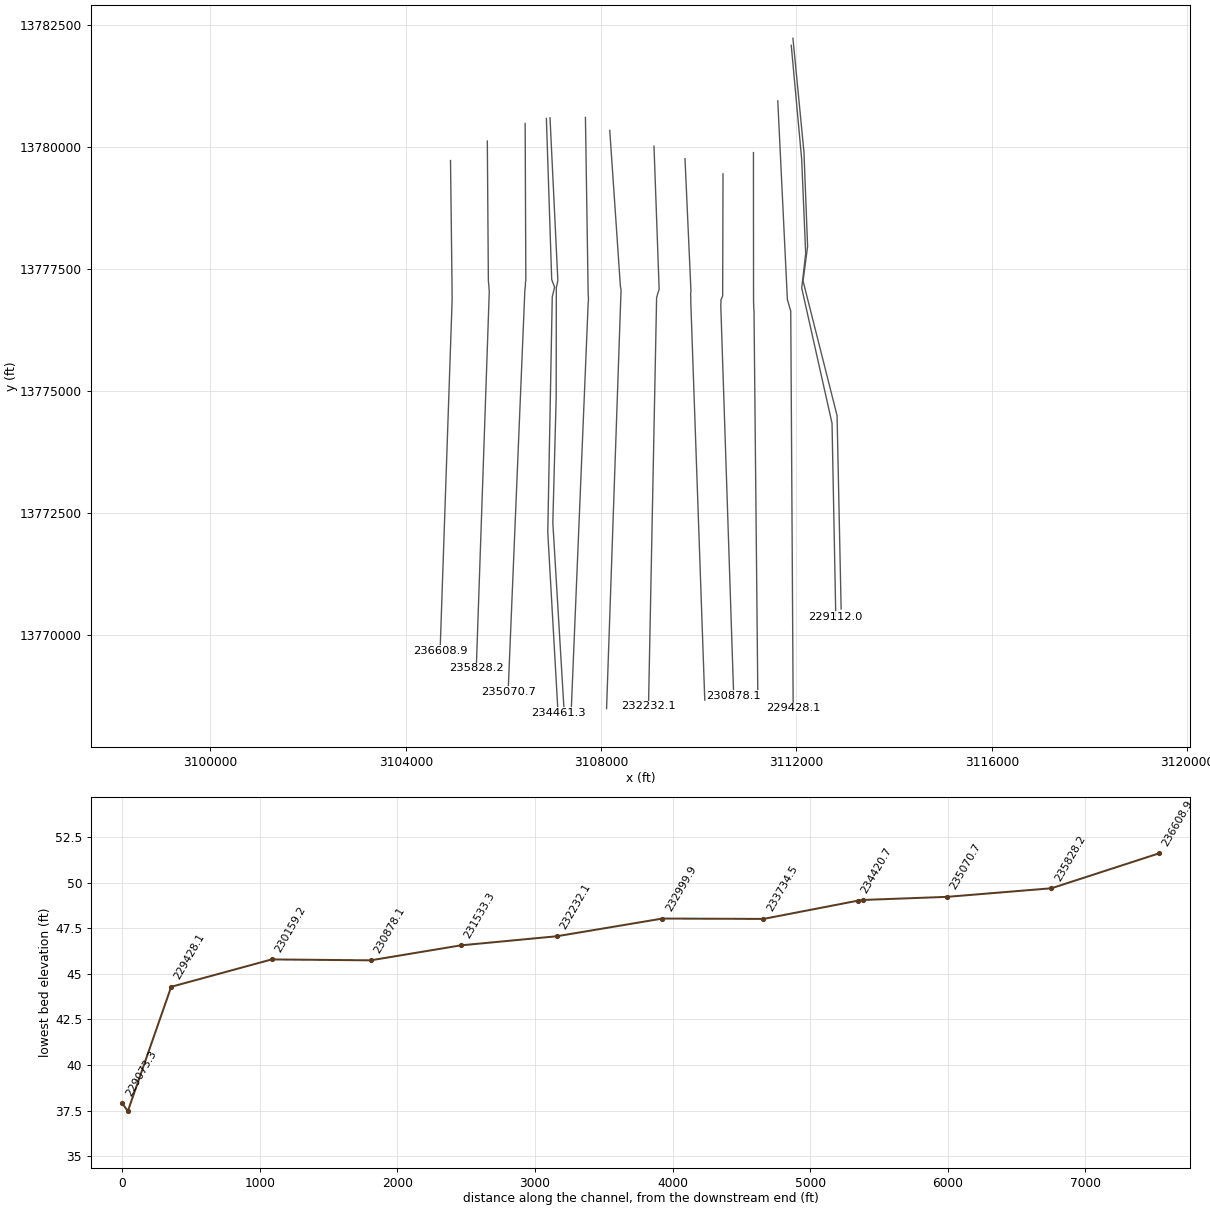
HEC-RAS study A100-00-00.prj: A100-00-00

--- A100-00-00.g01 (geometry) --- (continued)

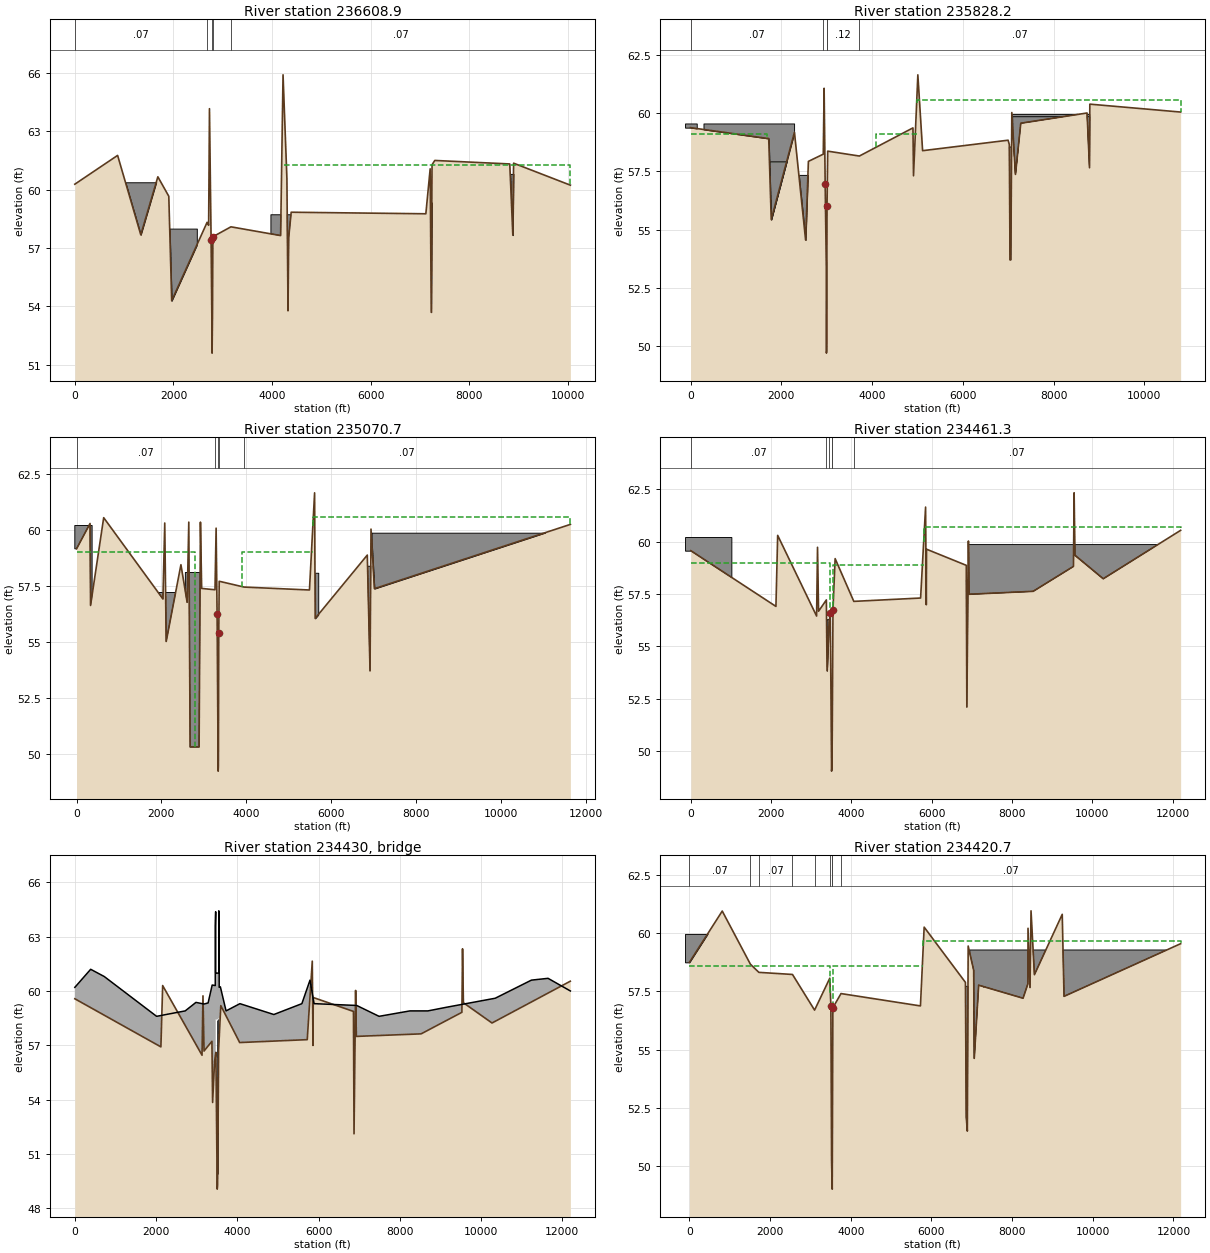
Type RM Length L Ch R = 1 ,236608.9,752.96,780.74,820.62
XS GIS Cut Line= 6
     3104916.719    13779717.562     3104949.202    13777038.951
     3104947.321    13776961.707     3104950.677    13776949.964
     3104949.202    13776851.731     3104703.403    13769675.945
#Sta/Elev= 30
       0   60.28  867.44   61.76 1337.52   57.68 1683.51   60.66 1905.28   59.66
 1963.98   54.29 2681.62   58.32 2712.96   58.17 2729.71   64.16 2762.92   57.39
 2781.33   52.64 2782.97    51.6 2791.63   53.74 2799.14   57.58 3165.03   58.09
 4172.25   57.64 4221.32    65.9 4299.75   60.57 4322.16   53.78    4336   57.53
 4386.19   58.84 7116.52   58.76 7204.26   61.07 7225.63    53.7 7241.93   61.28
 7297.69    61.5 8817.63   61.32 8880.08   57.66 8895.31   61.3610046.75   60.23
#Mann= 5 ,-1 , 0
       0     .07       0 2681.62     .12       0 2781.33    .041       0
 2791.63     .12       0 3165.03     .07       0
#XS Ineff= 1 ,-1
 4245.7310279.86   61.28
Permanent Ineff=
       F
#Block Obstruct= 7 ,-1
  218.43 1651.88   60.38 1795.42 2473.28      58 3975.57 4451.91   58.71
 7181.68 7309.92   59.34 7316.83 7792.46   59.82 8757.25 9032.06   60.81
Bank Sta=2762.92,2799.14
XS Rating Curve= 0
Exp/Cntr=.5,.3

Type RM Length L Ch R = 1 ,235828.2,777.47,757.49,755.61
XS GIS Cut Line= 6
     3105670.083    13780116.088     3105691.842    13777256.127
     3105703.922    13777129.468     3105703.922    13777095.916
     3105710.564     13777046.44     3105444.524    13769321.496
#Sta/Elev= 30
       0   59.38  1722.7   58.91 1778.17   55.43 2289.67   59.18 2535.64   54.55
 2597.11   57.93 2924.72   58.24 2943.64   61.07 2966.77   56.95 2991.14   53.46
 2994.58   49.69 2999.16    49.8 3007.89   56.02 3022.64   58.37 3720.47   58.16
 4901.53   59.37 4913.55   57.31 5009.25   61.65 5114.04   58.39 6998.16   58.84
 7025.04   58.65 7040.32    53.7 7058.87    53.7 7080.08   60.03 7160.37   57.37
 7277.54   59.57 8738.29   60.01 8792.39   57.66 8799.24   60.3910800.55   60.05
#Mann= 5 ,-1 , 0
       0     .07       0 2924.72     .12       0 2999.16    .041       0
 3007.89     .12       0 3720.47     .07       0
#XS Ineff= 3 ,-1
       0  1689.1    59.1 4094.92 4982.94    59.1 4982.9410800.55   60.56
Permanent Ineff=
       F       F       F
#Block Obstruct= 7 ,-1
    -121   136.1   59.56  284.69 2281.87   59.56 1703.82 2253.44   57.93
 2290.08 2711.45   57.35 6998.47 7328.24   58.55 7085.37 10841.3   59.95
 7098.7410958.45   59.85
Bank Sta=2966.77,3007.89
XS Rating Curve= 0
Exp/Cntr=.5,.3

Type RM Length L Ch R = 1 ,235070.7,512.82,609.33,655.8
XS GIS Cut Line= 6
     3106444.972    13780476.028     3106458.845    13777267.032
      3106448.78     13777198.25     3106450.457    13777164.698
     3106438.714    13777060.686     3106096.304    13768844.547
#Sta/Elev= 30
       0   59.15  318.16   60.28  330.04   56.62   639.8   60.54 2036.13   56.91
 2078.92    60.3 2113.26   55.01 2460.72   58.44 2606.81   56.76 2645.91   60.34
 2678.16    50.3 2888.79    50.3 2920.51   60.34 2949.23   57.38 3263.72   57.32
 3290.17   60.07 3312.98   56.24 3338.54   49.22 3343.96   49.45 3352.64   55.38
 3363.02    57.7 3951.25   57.44  5490.5   57.31 5611.67   61.65 5625.11   56.04
 6853.94   58.87 6918.66    53.7 6941.28   60.03 7022.35   57.3711641.81   60.24
#Mann= 5 ,-1 , 0
       0     .07       0 3263.72     .12       0 3343.96    .041       0
 3352.64     .12       0 3951.25     .07       0
#XS Ineff= 3 ,-1
       0    2786      59  3894.3 5569.97      59 5569.9711641.81   60.59
Permanent Ineff=
       F       F       F
#Block Obstruct= 6 ,-1
  -40.92  366.46   60.19 1887.02 2381.68    57.2 2564.89 2921.09   58.09
 5569.47 5697.71   58.08 6705.34 7163.36   58.37 6956.1811556.59   59.87
Bank Sta=3312.98,3352.64
XS Rating Curve= 0
Exp/Cntr=.5,.3

Type RM Length L Ch R = 1 ,234461.3,115.36,40.64,122.37
XS GIS Cut Line= 6
     3106879.311    13780580.104     3106988.291       13777282.
     3107047.685    13777124.435     3106999.763    13776926.378
      3106907.99    13772102.542     3107117.706    13768416.193
#Sta/Elev= 30
       0   59.57 2119.11   56.91 2162.43    60.3 3131.67   56.45 3154.73   59.73
 3180.79   56.68 3374.95   57.22 3391.83   53.84 3441.03   56.12 3473.03   56.61
 3504.89   49.05 3513.97   49.26 3521.34   50.82  3539.8   56.76  3593.3   59.19
 4058.41   57.15 5721.53   57.31 5845.44   61.65 5862.94   56.99 5869.11   59.64
 6859.04   58.87 6873.01   52.11 6912.15   60.03 6930.14   57.49 8524.33   57.63
 9528.17   58.82 9544.17   62.33 9565.44   59.3510269.91   58.2312196.67   60.54
#Mann= 6 ,-1 , 0
       0     .07       0 3374.95     .07       0 3441.03     .12       0
 3513.97    .041       0 3521.34     .12       0 4058.41     .07       0
#XS Ineff= 3 ,-1
       0 3468.85      59    3542  5797.5    58.9  5797.512196.67   60.72
Permanent Ineff=
       F       F       F
#Block Obstruct= 6 ,-1
 -143.67 1008.96   60.22 3368.19  3452.9    56.3 4078.62 4111.35   57.03
 6732.82 7010.69   58.18 6911.3312407.28   59.68 6912.0212343.79   59.86
Bank Sta=3473.03,3539.8
XS Rating Curve= 0
Exp/Cntr=.5,.3

Type RM Length L Ch R = 3 ,234430  ,,,
BEGIN DESCRIPTION:
Almeda School Rd.
END DESCRIPTION:
Bridge Culvert--1,0,-1,-1, 0
Deck Dist Width WeirC Skew NumUp NumDn MinLoCord MaxHiCord MaxSubmerge Is_Ogee
5,31,2.6,0, 38, 38, , , .95, 0, 0,0,,
       0     390     724    2013    2717    2982    3181    3281    3381    3457
    3458    3467    3468    3469    3492    3517    3542    3543    3544    3553
    3554    3583    3723    4064    4899    5589    5789    5889    6939    7489
    8249    8455    8692    9146   10349   11239   11649   12199
    60.2    61.2    60.8    58.6    58.9   59.37   59.28   59.34   60.33    60.3
   63.62   64.38   61.01      61   60.98   60.99      61   61.03   64.43    63.5
    60.2   60.23    58.9    59.3    58.7    59.3    60.6    59.3    59.2    58.6
    58.9    58.9    58.9    59.1    59.6    60.6    60.7      60
                                                                                
                           58.44   58.41   58.44   58.52
                                                                                
                                                                
       0     390     724    2013    2717    2982    3181    3281    3381    3483
    3484    3493    3494    3496    3519    3544    3569    3570    3571    3580
    3581    3610    3750    4091    4926    5616    5816    5916    6966    7516
    8276    8482    8719    9173   10376   11266   11676   12226
    60.2    61.2    60.8    58.6    58.9   59.37   59.28   59.34   60.33    60.3
   63.62   64.38   61.01      61   60.98   60.99      61   61.03   64.43    63.5
    60.2   60.23    58.9    59.3    58.7    59.3    60.6    59.3    59.2    58.6
    58.9    58.9    58.9    59.1    59.6    60.6    60.7      60
                                                                                
                           58.44   58.41   58.44   58.52
                                                                                
                                                                
Pier Skew, UpSta & Num, DnSta & Num=  ,3492, 2 ,3519, 2 , 0 , 0 , 0 ,,
    1.33    1.33
       0      59
    1.33    1.33
       0      59
Pier Skew, UpSta & Num, DnSta & Num=  ,3517, 2 ,3544, 2 , 0 , 0 , 0 ,,
    1.33    1.33
       0      59
    1.33    1.33
       0      59
BR Coef=-1 , 1 , 1 ,1.25, 0 ,,,.8,-1,2,0,
WSPro=,,,, 1 ,,,, 0 ,,,, 0 ,,,,-1 ,-1 ,-1 , 0 , 0 , 0 , 0 , 0
BC Design=,, 0 ,, 0 ,,,,,,
BC HTab HWMax=62.33

Type RM Length L Ch R = 1 ,234420.7,640.7,686.24,608.72
XS GIS Cut Line= 6
     3106953.876    13780591.576      3107114.48    13777259.057
     3107082.971    13777114.694     3107080.065    13774867.214
     3107011.235    13772303.296     3107243.178    13768434.118
#Sta/Elev= 30
       0   58.74     814   60.94 1511.97   58.66 1721.66   58.31 2555.15   58.22
 3103.11   56.69 3480.09   58.06 3507.04   56.86 3524.45   50.21 3540.37   49.01
 3556.51   56.79 3758.08    57.4 5727.51   56.87 5819.61   60.25 6842.96   57.88
 6862.78   52.11 6889.78    51.5 6910.87   59.44 7047.69    58.4 7061.67   54.62
 7170.93   57.76 8271.51    57.2 8392.14   57.82  8394.5    60.2  8443.8   57.66
 8469.07   60.95 8553.17   58.21 9242.91    60.8 9287.35   57.2812178.07   59.54
#Mann= 9 ,-1 , 0
       0     .07       0 1511.97     .12       0 1721.66     .07       0
 2555.15     .12       0 3103.11     .07       0 3480.09     .12       0
 3524.45    .041       0 3540.37     .12       0 3758.08     .07       0
#XS Ineff= 3 ,-1
       0 3495.84    58.6 3570.61  5797.5    58.6  5797.512178.07   59.66
Permanent Ineff=
       F       F       F
#Block Obstruct= 3 ,-1
 -107.87  492.33   59.96 6604.58 7288.55   57.71 6949.9612341.29   59.27
Bank Sta=3507.04,3556.51
XS Rating Curve= 0
Exp/Cntr=.5,.3

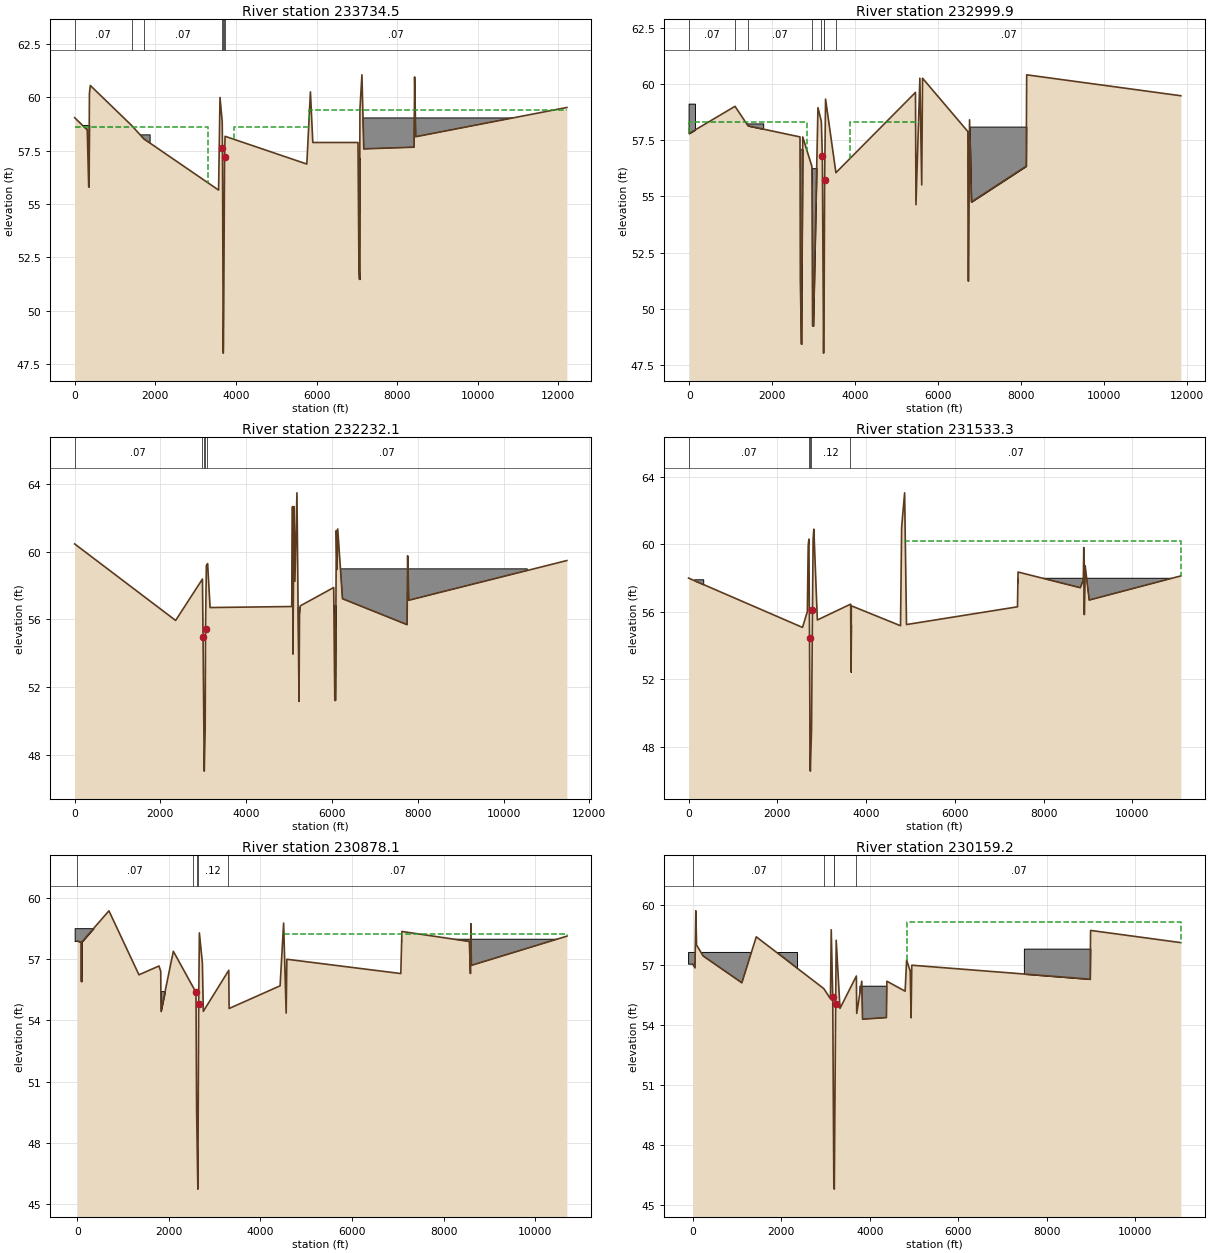
Type RM Length L Ch R = 1 ,233734.5,619.8,734.53,698.53
XS GIS Cut Line= 6
     3107678.896    13780600.552     3107735.504    13776956.675
      3107738.86    13776938.221     3107740.537    13776857.696
     3107735.504    13776807.368     3107385.924    13768398.977
#Sta/Elev= 30
       0   59.04  312.53   58.47  348.72    55.8  356.09   55.87  366.21   60.17
  388.99   60.55 1412.67   58.68 1715.94   58.05 3570.73   55.65  3605.5   59.99
 3660.56   58.85 3667.22    57.6 3686.25   48.01 3689.51   48.25 3698.54   49.99
 3718.37   57.19 3731.44   58.17  5759.4   56.87 5848.87   60.25 5908.12   57.88
 7028.94   57.88 7051.84   52.11 7066.24   51.47 7076.99   59.44 7126.61   61.05
 7172.21   57.58 8420.82   57.66 8433.41   60.95 8461.69   58.1512210.11   59.52
#Mann= 7 ,-1 , 0
       0     .07       0 1412.67     .12       0 1715.94     .07       0
 3660.56     .12       0 3689.51    .081       0 3698.54     .12       0
 3731.44     .07       0
#XS Ineff= 3 ,-1
       0 3299.17    58.6 3942.28 5813.42    58.6 5813.4212210.11   59.39
Permanent Ineff=
       F       F       F
#Block Obstruct= 4 ,-1
  106.87  470.23    58.7 1496.18 1859.54   58.26 6818.32 7160.31   57.16
  7125.612479.42   59.03
Bank Sta=3667.22,3718.37
XS Rating Curve= 0
Exp/Cntr=.5,.3

Type RM Length L Ch R = 1 ,232999.9,822.48,767.81,773.58
XS GIS Cut Line= 4
     3108176.993    13780334.523     3108394.804    13777142.889
     3108408.225     13777072.43     3108111.923     13768497.87
#Sta/Elev= 30
       0    57.8 1099.49      59 1414.15   58.13 2666.53   57.64 2674.55   51.26
 2702.08   48.43 2732.64   57.64 2953.34   56.33 2970.26   49.24 2989.58   49.24
 3099.51   58.94 3181.08   58.33 3205.18    56.8 3235.35   48.03 3249.89   51.05
    3260   55.71 3283.04   59.32 3532.73   56.05 5452.01   59.62 5463.05   54.63
 5557.41   60.25 5602.36   55.51 5621.52   60.25 6714.31   57.88  6727.8   51.23
 6755.66    58.4 6799.67   54.75 8121.92   56.34 8133.29    60.411850.46   59.47
#Mann= 8 ,-1 , 0
       0     .07       0 1099.49     .12       0 1414.15     .07       0
 2953.34     .12       0 3181.08     .12       0 3235.35    .041       0
 3249.89     .12       0 3532.73     .07       0
#XS Ineff= 4 ,-1
       0 2841.62    58.3    3870 5544.22    58.3 5544.2211606.83   59.19
11606.8311850.46    58.3
Permanent Ineff=
       F       F       F       F
#Block Obstruct= 7 ,-1
  -20.22  132.83   59.12  1097.8    1779   58.24 2488.13 2509.48   57.35
 2664.96 2735.09   57.09 2858.02 3096.18   56.25  6485.5 6943.51   56.87
 6756.61 11262.8    58.1
Bank Sta=3205.18,3260
XS Rating Curve= 0
Exp/Cntr=.5,.3

Type RM Length L Ch R = 1 ,232232.1,647.38,698.88,838.53
XS GIS Cut Line= 6
     3109082.625    13780011.892     3109188.312    13777082.495
      3109154.76    13776978.484      3109148.05    13776948.287
     3109136.306    13776913.057     3108970.222    13768546.711
#Sta/Elev= 30
       0   60.45 2354.18   55.94 2980.05   58.38 2994.23   54.94 3021.44   47.06
 3043.49   49.49 3051.34   55.42 3070.78   59.17 3100.44   59.29 3157.75    56.7
 5061.49   56.76 5079.72   62.65 5090.37   53.96 5113.68   62.65  5135.7   58.25
  5183.4   63.46 5231.71   51.17 5242.93   56.28  5261.5    56.8 6040.33   57.88
 6065.89   51.23 6079.82   51.26 6101.68   61.24 6118.86   58.95 6134.03   61.33
 6245.29   57.22 7751.43   55.69 7764.44   59.75 7790.86   57.1311476.66   59.47
#Mann= 5 ,-1 , 0
       0     .07       0 2967.75     .12       0 3020.08    .041       0
 3028.58     .12       0 3090.55     .07       0
#XS Ineff= 1 ,-1
 5187.7111208.19   59.29
Permanent Ineff=
       F
#Block Obstruct= 3 ,-1
 5038.17 5312.98    56.7 5917.56  6137.4   56.84 6154.5310552.02   58.98
Bank Sta=2994.23,3051.34
XS Rating Curve= 0
Exp/Cntr=.3,.1

Type RM Length L Ch R = 1 ,231533.3,699.76,655.12,619.1
XS GIS Cut Line= 6
     3109717.524    13779756.243     3109839.224    13777045.588
     3109832.513    13776980.161     3109835.869    13776919.767
     3109835.869    13776824.144     3110122.313    13768671.261
#Sta/Elev= 30
       0   57.99 2567.32   55.07 2676.28   56.01 2695.46   59.92 2711.22    60.3
 2725.89   54.44 2733.28   49.92 2734.32   47.14 2743.68   46.56 2770.88   49.05
 2791.47   56.09 2806.29    60.3 2822.56   60.89 2901.79   55.51 3652.63   56.45
 3659.66   52.43 3667.75   56.35 4776.21   55.17 4801.68   61.01 4868.78   63.04
  4911.1   55.24 7412.51   56.29  7425.1   58.35 8827.85   57.42 8895.89   57.86
 8906.43    59.8 8918.71   55.83 8937.49   58.73 9028.61   56.6911093.18   58.12
#Mann= 5 ,-1 , 0
       0     .07       0 2703.63     .12       0 2742.46    .041       0
 2750.78     .12       0 3645.22     .07       0
#XS Ineff= 1 ,-1
 4846.4211344.71    60.2
Permanent Ineff=
       F
#Block Obstruct= 3 ,-1
  128.24  329.77   57.92  3554.2 3700.76   55.24 7420.9111204.17   57.98
Bank Sta=2725.89,2791.47
XS Rating Curve= 0
Exp/Cntr=.3,.1

Type RM Length L Ch R = 1 ,230878.1,651.25,718.94,642.01
XS GIS Cut Line= 6
     3110495.964    13779444.867     3110488.458    13776944.931
      3110451.55    13776857.696     3110454.906    13776817.433
     3110449.873    13776752.007     3110713.927    13768764.674
#Sta/Elev= 30
       0   57.88    84.4   57.83   90.41    55.9   97.33   57.83  691.25   59.36
  1347.2   56.23 1785.22   56.66 1822.74    56.4 1828.58   54.44 2098.02   57.38
 2592.68   55.37  2606.4   49.57 2633.68   45.74 2651.54    54.8 2666.69   58.28
  2732.5   56.81 2752.94   54.44 3308.59   56.45 3316.28   54.58 4429.78   55.69
 4506.52   58.76 4562.45   54.36 4577.38   56.99 7066.33   56.29 7090.31   58.35
 8563.16   57.86 8587.32   56.29  8597.2   58.73  8607.3   56.6910692.88   58.12
#Mann= 5 ,-1 , 0
       0     .07       0 2532.82     .12       0 2619.33    .041       0
 2627.56     .12       0 3298.97     .07       0
#XS Ineff= 1 ,-1
 4505.1211017.06   58.23
Permanent Ineff=
       F
#Block Obstruct= 3 ,-1
  -57.39  355.91   58.51 1648.85 2015.27   55.43 7083.6510792.76   57.97
Bank Sta=2592.68,2651.54
XS Rating Curve= 0
Exp/Cntr=.3,.1

Type RM Length L Ch R = 1 ,230159.2,664.36,731.12,746.33
XS GIS Cut Line= 6
     3111118.716    13779880.793     3111120.916     13776840.92
     3111125.948    13776689.935     3111132.659    13776607.732
     3111130.981    13776555.727     3111207.689    13768855.415
#Sta/Elev= 30
       0   57.04   48.06   56.86   66.83   59.71   83.51      58  233.51   57.45
 1107.16   56.11 1433.12   58.41 2958.88   55.82    3109   55.31 3127.17   58.76
 3161.05   55.38 3185.48      46 3196.28   45.79 3226.72   55.05 3239.42   58.24
 3324.58   54.83 3695.29   56.45 3702.56   54.58 3816.98   56.19 3834.29   54.29
 4373.97   54.37 4383.87   56.19 4796.38   55.69 4830.27   57.25 4912.17   56.69
 4931.17   54.36 4947.14   56.99 8977.22   56.29 8987.55   58.7311026.19   58.12
#Mann= 5 ,-1 , 0
       0     .07       0 2958.88     .12       0 3188.66    .041       0
  3196.6     .12       0 3686.39     .07       0
#XS Ineff= 1 ,-1
 4832.7611276.45   59.16
Permanent Ineff=
       F
#Block Obstruct= 3 ,-1
  -96.22 2347.14   57.63 3774.05 4396.95   55.94 7479.7810620.31   57.82
Bank Sta=3161.05,3226.72
XS Rating Curve= 0
Exp/Cntr=.3,.1

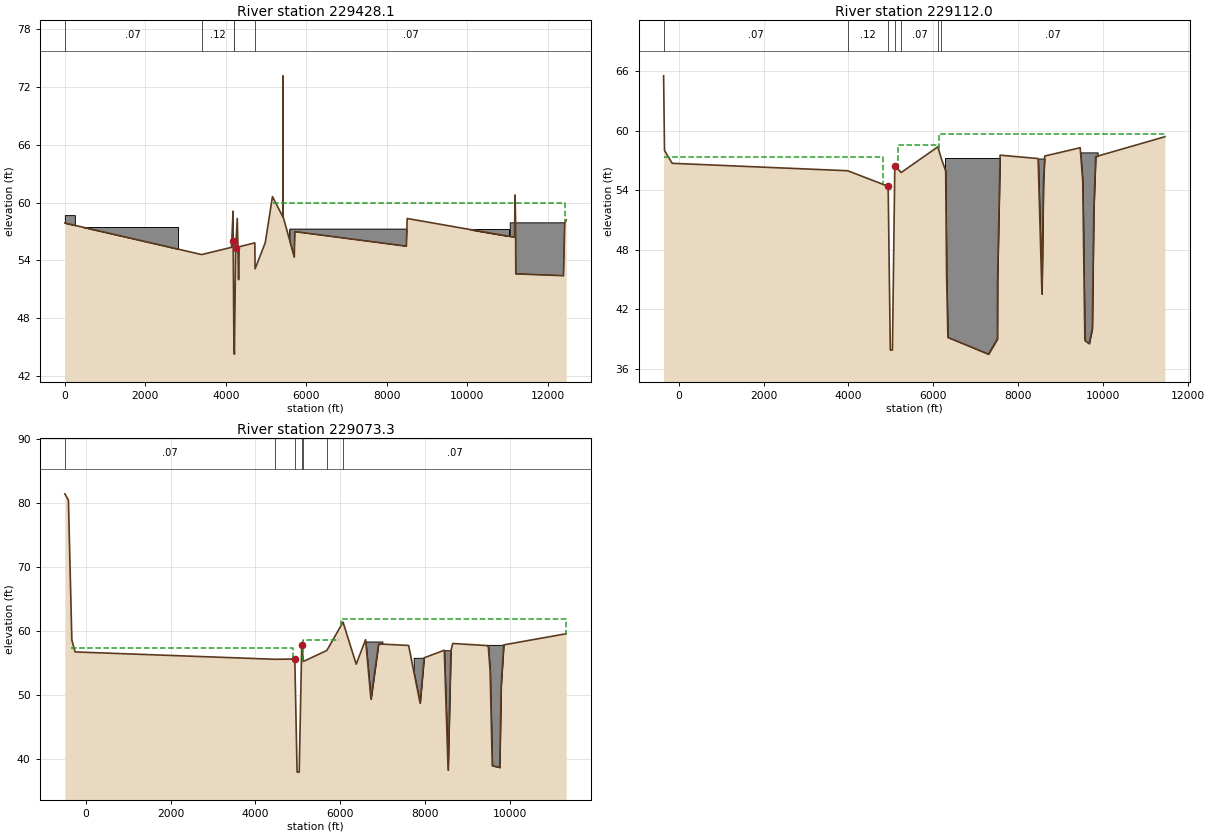
Type RM Length L Ch R = 1 ,229428.1,325.28,315.36,312.96
XS GIS Cut Line= 6
     3111616.917    13780939.471     3111813.767    13776869.439
     3111833.899     13776805.69     3111864.096     13776693.29
     3111882.549    13776637.929      3111932.24     13768499.53
#Sta/Elev= 30
       0   57.88 3399.39   54.61  4140.3   55.36 4179.31    59.1 4182.16      56
 4199.53   45.41 4209.09   44.71  4212.1   44.29 4243.82   55.25 4283.79   58.36
 4316.32   52.01 4331.67   55.42 4719.46   55.83 4726.18   53.13 4978.98   55.84
 5157.86   60.62 5415.16   58.53 5419.46   73.14 5423.83   58.53 5700.24   54.36
 5713.04   56.99 8484.71   55.48 8505.45   58.3511172.18    56.411184.04   60.79
11196.73   58.5311203.82   52.6112388.29   52.4212418.29   57.8712454.96   58.19
#Mann= 5 ,-1 , 0
       0     .07       0 3399.39     .12       0 4199.53    .041       0
 4209.09     .12       0 4719.46     .07       0
#XS Ineff= 1 ,-1
 5160.4112428.29   59.92
Permanent Ineff=
       F
#Block Obstruct= 5 ,-1
   275.6 2808.08   57.48 5589.7410982.15   57.17 5592.84 11040.6   57.25
11065.6512428.29    57.9       0  248.78    58.7
Bank Sta=4182.16,4243.82
XS Rating Curve= 0
Exp/Cntr=.3,.1

Type RM Length L Ch R = 1 ,229112.0,40.66,39.42,39.12
XS GIS Cut Line= 6
 3111892.848534813782077.3811366 3112106.311363213779743.6033455
 3112188.253152313777813.4911553 3112107.167816313777107.2306177
 3112727.8497398 13774338.101939 3112804.652045213770376.8073489
#Sta/Elev= 30
    -353   65.53 -331.68      58 -150.44   56.71 3980.87   55.96 4933.81   54.39
 4984.47   37.88 5034.48   37.88 5090.62   56.46 5240.69   55.78 6103.81   58.37
 6182.71   57.22 6287.91   55.94 6308.95   45.53 6340.51   39.16 7293.45   37.47
 7504.54      39 7509.54   44.84 7569.55   57.53 8464.72   57.19 8554.74   43.53
 8589.74   54.69 8619.75   57.44 9454.91   58.28 9514.92   54.91 9564.93   38.84
 9667.05   38.53 9739.96   40.04 9774.97   51.94 9819.97   57.3811449.68   59.39
#Mann= 7 ,-1 , 0
    -353     .07       0 3980.87     .12       0 4933.81    .041       0
 5090.62     .12       0 5240.69     .07       0 6103.81     .12       0
 6182.71     .07       0
#XS Ineff= 3 ,-1
    -353 4815.81   57.35 5169.38 6103.81   58.57 6119.5911449.68   59.69
Permanent Ineff=
       T       T       T
#Block Obstruct= 4 ,-1
                         6272.13 7569.55   57.25 8464.72 8619.75   57.19
  9444.9 9864.98   57.81
Bank Sta=4933.81,5090.62
XS Rating Curve= 0
Exp/Cntr=.5,.3

Type RM Length L Ch R = 1 ,229073.3,165.38,165.99,167.95
XS GIS Cut Line= 6
      3111927.34     13782219.62     3112153.286     13779887.71
     3112227.535     13777957.23     3112134.723     13777251.86
     3112830.811     13774495.35     3112914.197     13770535.51
#Sta/Elev= 30
 -490.75   81.38 -406.67   80.38 -326.04   58.53 -250.44   56.68  4458.1   55.53
 4926.73   55.57 4980.42   37.91 5030.55    37.9 5090.61   57.83 5129.11   55.19
 5681.39   56.91 6062.69   61.34 6373.28   54.77 6593.67   58.59 6721.03    49.3
 6899.91   57.93 7608.38   57.69 7878.44   48.69 7973.46   55.76 8448.57   56.94
 8538.59   38.22  8603.6   56.84 8648.61      58  9483.8   57.66 9528.81   53.69
 9578.82   38.91 9753.86   38.63 9788.87   51.47 9848.88   57.78 11319.9   59.52
#Mann= 7 ,-1 , 0
 -490.75     .07       0  4458.1     .12       0 4926.73    .041       0
 5090.61     .12       0 5129.11     .07       0 5681.39     .12       0
 6062.69     .07       0
#XS Ineff= 3 ,-1
 -341.16 4880.71   57.35 5129.81 5972.08   58.57  6006.5 11319.9   61.84
Permanent Ineff=
       T       T       F
#Block Obstruct= 4 ,-1
 6593.67 6990.25   58.31 7728.41 7973.46   55.76 8448.57 8618.61   56.94
 9438.79 9848.88   57.78
Bank Sta=4926.73,5090.61
XS Rating Curve= 0
Exp/Cntr=.5,.3