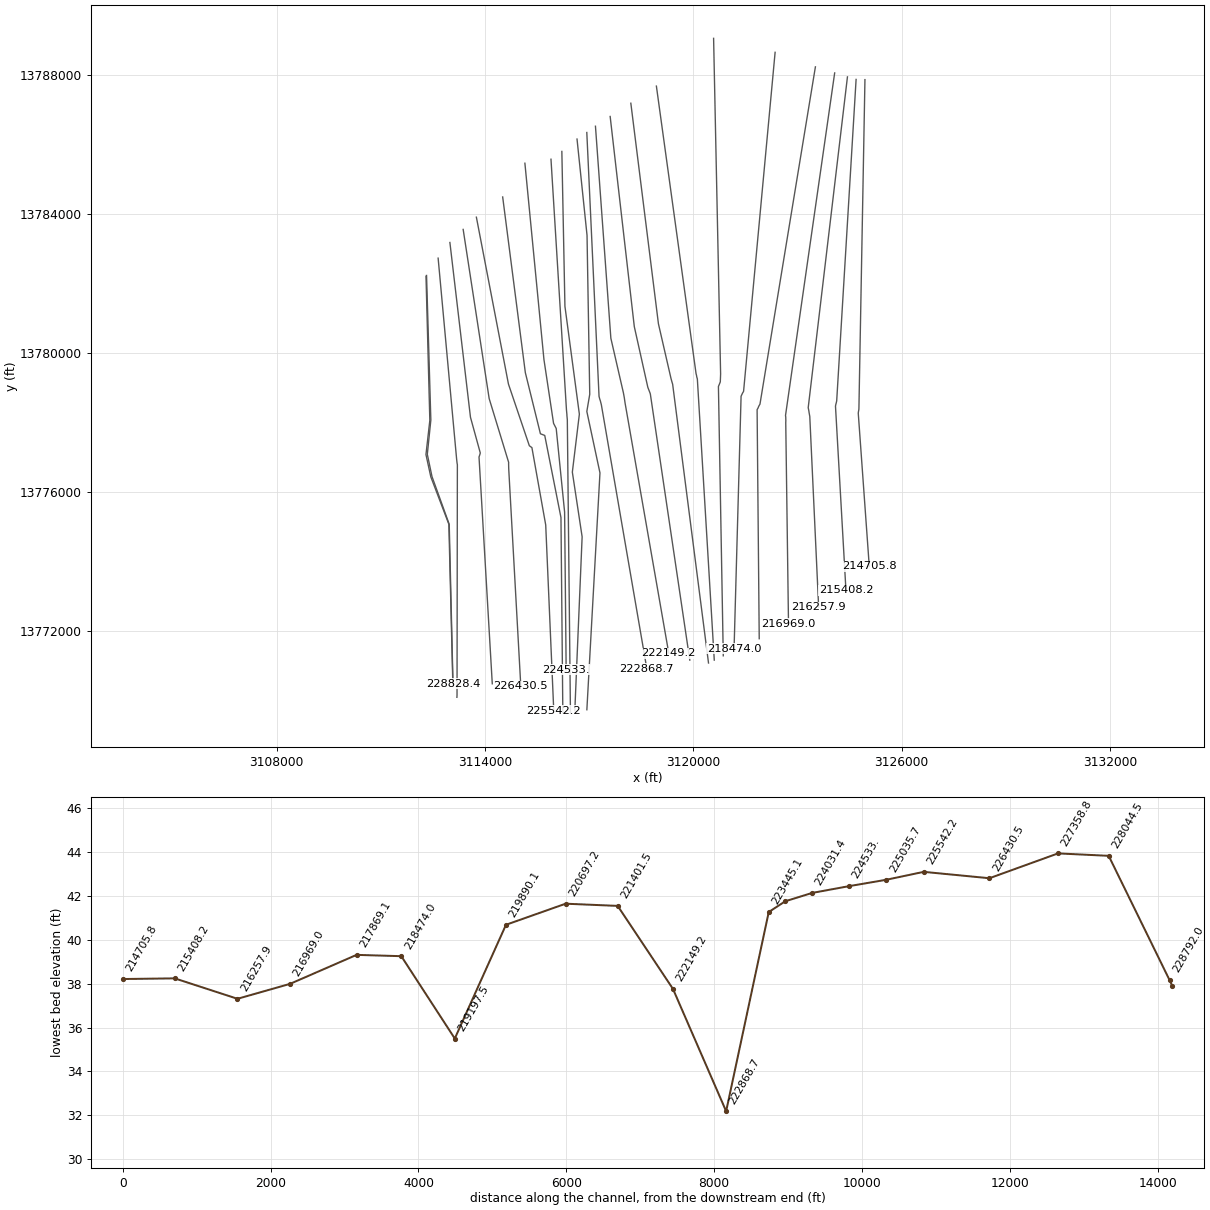
HEC-RAS study A100-00-00.prj: A100-00-00

--- A100-00-00.g01 (geometry) --- (continued)

Type RM Length L Ch R = 3 ,228950  ,,,
BEGIN DESCRIPTION:
Kirby Bridge
END DESCRIPTION:
Bridge Culvert--1,0,-1,-1, 0
Deck Dist Width WeirC Skew NumUp NumDn MinLoCord MaxHiCord MaxSubmerge Is_Ogee
35,115,2.6,0, 60, 60, , , .98, 0, 0,0,,
    -356 -243.12 -173.07 -158.07 -148.06     -48  -17.97  187.26  617.58   940.8
 1127.67 1348.65 1383.75 1479.06 1518.15  1619.4 1799.73 1859.84 1904.92 1934.97
 1975.04 2080.15  2215.3 2255.35 2299.61  2305.4 2335.44 2400.01 2520.64 2605.45
 2640.74 2665.75 2710.78 2736.47 3025.48 3069.52 3106.06 3121.08  3141.1 3476.43
 3496.44 3506.45  3596.5 3641.52 3911.66 4102.45  4152.7 4258.43 4303.93 4359.54
 4456.14 4897.44 4911.23 4912.23 4966.23 5044.32 5099.32 5099.96 5499.46  6006.5
   58.97   58.93   57.73   57.63    58.2   57.47   57.91   57.75   59.05   58.31
   59.03   58.58    57.5   57.56   58.37   58.42   59.38   58.44   58.29   59.01
   59.15    58.6   58.89   57.73   57.85   58.37   58.98   59.28   58.96   59.27
   58.88   57.87   57.82   58.69   59.31    58.2   58.45   59.44   59.75   58.84
   58.49   57.68   57.59   58.71   59.22   58.39   58.57   57.42   57.35   58.45
   58.47   64.47   64.47   67.97   70.39   70.39   68.11   64.61   58.57   61.64
   44.42   44.42   44.42   44.42   44.42   44.42   44.42   44.42   44.42   44.42
   44.42   44.42   44.42   44.42   44.42   44.42   44.42   44.42   44.42   44.42
   44.42   44.42   44.42   44.42   44.42   44.42   44.42   44.42   44.42   44.42
   44.42   44.42   44.42   44.42   44.42   44.42   44.42   44.42   44.42   44.42
   44.42   44.42   44.42   44.42   44.42   44.42   44.42   44.42   44.42   44.42
   44.42    44.3   59.18   59.18   59.61   59.61   59.18    44.3   44.42   44.42
    -353 -240.12 -170.07 -155.07 -145.06     -45  -14.97  190.26  620.58   943.8
 1130.67 1351.65 1386.75 1482.06 1521.15  1622.4 1802.73 1862.84 1907.92 1937.97
 1978.04 2083.15  2218.3 2258.35 2302.61  2308.4 2338.44 2403.01 2523.64 2608.45
 2643.74 2668.75 2713.78 2739.47 3028.48 3072.52 3109.06 3124.08  3144.1 3479.43
 3499.44 3509.45  3599.5 3644.52 3914.66 4105.45  4155.7 4261.43 4306.93 4362.54
    4467  4908.3 4910.81 4911.81 4959.01 5048.015098.901 5102.82  5510.3 5903.44
   58.97   58.93   57.73   57.63    58.2   57.47   57.91   57.75   59.05   58.31
   59.03   58.58    57.5   57.56   58.37   58.42   59.38   58.44   58.29   59.01
   59.15    58.6   58.89   57.73   57.85   58.37   58.98   59.28   58.96   59.27
   58.88   57.87   57.82   58.69   59.31    58.2   58.45   59.44   59.75   58.84
   58.49   57.68   57.59   58.71   59.22   58.39   58.57   57.42   57.35   58.45
   58.47   64.47   64.47   67.97   70.39   70.39   68.11   64.61   58.57   61.64
   44.42   44.42   44.42   44.42   44.42   44.42   44.42   44.42   44.42   44.42
   44.42   44.42   44.42   44.42   44.42   44.42   44.42   44.42   44.42   44.42
   44.42   44.42   44.42   44.42   44.42   44.42   44.42   44.42   44.42   44.42
   44.42   44.42   44.42   44.42   44.42   44.42   44.42   44.42   44.42   44.42
   44.42   44.42   44.42   44.42   44.42   44.42   44.42   44.42   44.42   44.42
   44.42    44.3   59.18   59.18   59.61   59.61   59.18    44.3   44.42   44.42
Pier Skew, UpSta & Num, DnSta & Num=  ,4966.23, 2 ,4968.01, 2 , 0 , 0 , 0 ,,
       3       3
   44.39   59.73
       3       3
   44.39   59.73
Pier Skew, UpSta & Num, DnSta & Num=  ,5035.32, 2 ,5048.01, 2 , 0 , 0 , 0 ,,
       3       3
   44.39   59.73
       3       3
   44.39   59.73
Abutment Skew #Up #Dn= , 7 , 7
 4907.97 4926.73 4980.42 5030.55 5062.04 5090.61 5099.38
   61.76   55.57   37.91    37.9   48.66   57.83   60.72
 4910.03 4929.62 4942.58 4980.28 5030.29 5086.43 5099.63
   61.09   54.57   50.19   37.88   37.88   56.46  60.816
BR Coef=-1 , 0 , 0 ,, 0 ,,,.8,-1,,0,
WSPro=,,,, 1 ,,,, 0 ,,,, 0 ,,,,-1 ,-1 ,-1 , 0 , 0 , 0 , 0 , 0
BC Design=61.1,57.1, 1 ,231.8701, 1 ,3,2,4088,4050,80,3.5
BC HTab HWMax=62.56

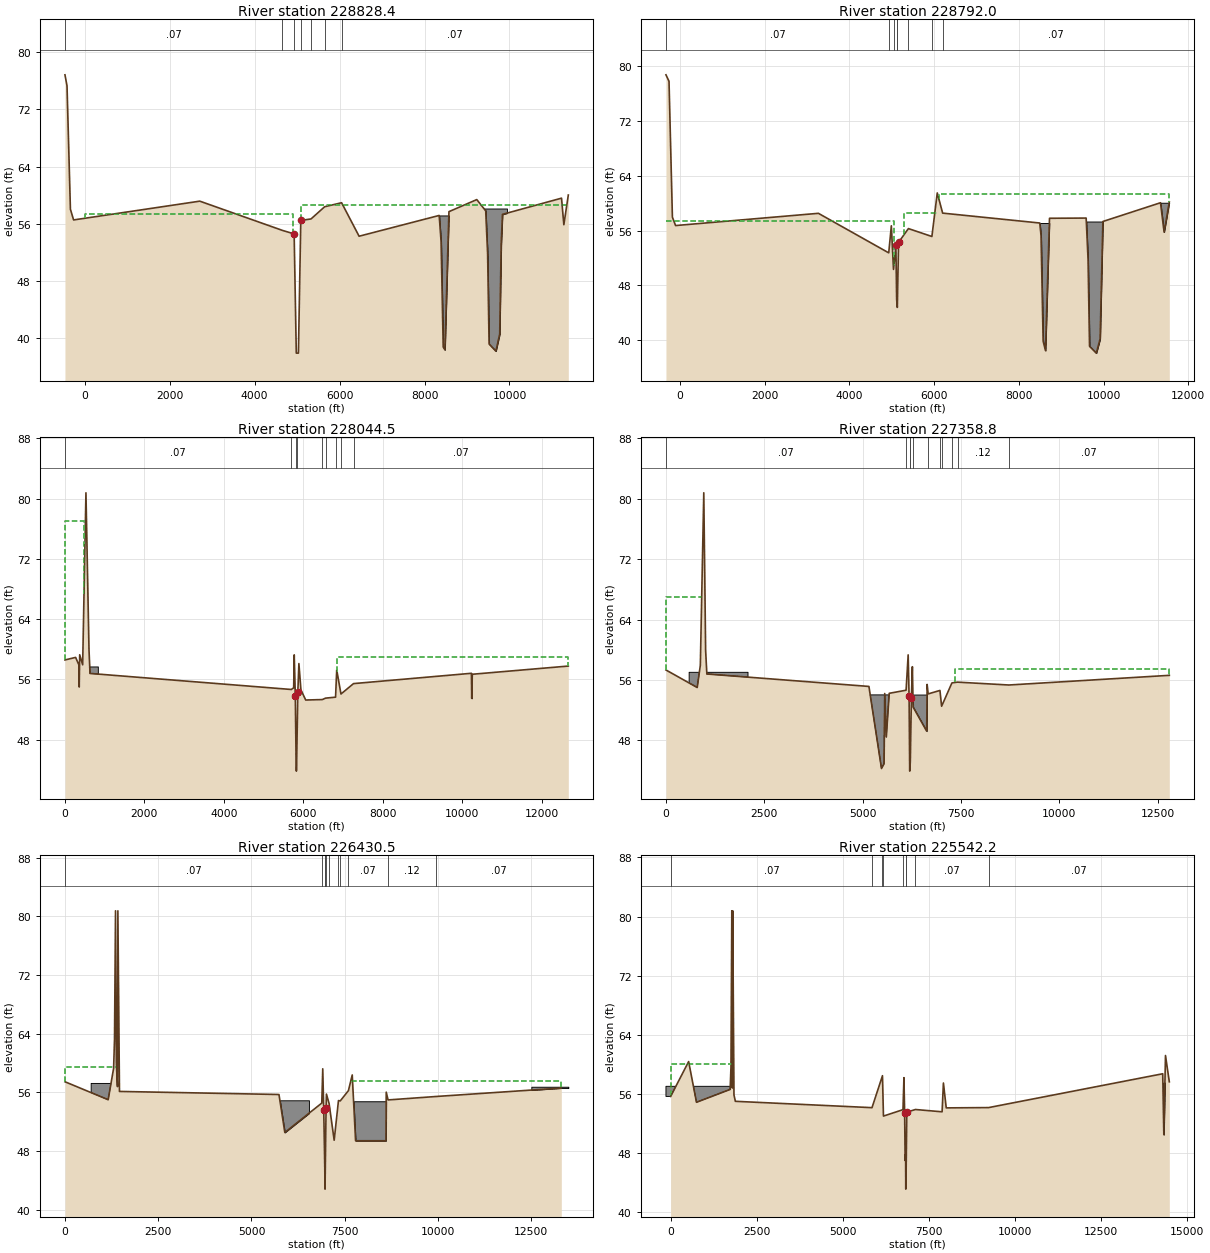
Type RM Length L Ch R = 1 ,228828.4,39.21,39.22,39.1
XS GIS Cut Line= 6
      3112302.86      13782199.6     3112413.158     13778050.04
     3112301.784     13777066.23     3112441.002     13776425.83
     3112960.747      13775061.5     3113075.483       13770471.
#Sta/Elev= 30
    -467   76.85  -418.6   75.31  -338.6   58.03  -263.6   56.53 2707.73   59.16
 4652.18   55.07 4929.62   54.57 4980.28   37.88 5030.29   37.88 5086.43   56.46
 5327.07   56.67 5648.44   58.38 6047.31   58.94 6459.05   54.25 8344.86   57.16
 8389.87   53.47 8439.88   38.73 8479.88   38.34  8574.9   57.69    9230   59.38
 9440.03   57.81 9485.04   51.84 9520.05   39.16 9680.07   38.16 9770.08   40.56
 9805.09   53.13  9835.1   57.3111225.77   59.5811280.32   55.8611385.54   60.02
#Mann= 7 ,-1 , 0
    -467     .07       0 4652.18     .12       0 4929.62    .041       0
 5086.43     .12       0 5327.07     .07       0 5648.44     .12       0
 6047.31     .07       0
#XS Ineff= 2 , 0
       0 4907.66   57.35 5102.78       0   58.57
Permanent Ineff=
       T       T
#Block Obstruct= 2 ,-1
 9310.01 9940.11   58.13 8344.86  8574.9   57.16
Bank Sta=4929.62,5086.43
XS Rating Curve= 0
Exp/Cntr=.5,.3

Type RM Length L Ch R = 1 ,228792.0,779.52,823.62,751.89
XS GIS Cut Line= 6
 3112318.7409993 13782223.349908 3112442.576396913778061.4631007
 3112340.695287413777074.3814054 3112475.767790813776431.3622644
 3112971.784027613775058.0794837 3113080.8171361 13770453.054819
#Sta/Elev= 30
    -331   78.65 -258.86   77.71 -178.85   57.94 -103.85   56.72 3268.14    58.5
 4928.37   52.75 4989.81   56.69 5040.99   50.34 5097.01   53.83 5115.03   46.01
 5130.74   44.81 5160.34   54.28    5393   56.28 5947.17   55.13 6073.93   61.47
 6201.12   58.53 8493.73   57.09 8523.73   55.28 8573.74   39.91 8628.75   38.53
 8723.76   57.78 9588.88   57.81 9633.89   51.78 9668.89   39.16 9828.92   38.16
 9918.93   40.24 9983.94   57.3111344.13   60.0411429.14   55.7711552.31   60.15
#Mann= 8 ,-1 , 0
    -331     .07       0 4928.37     .12       0 5040.99     .04       0
 5115.03    .041       0 5130.74     .12       0    5393     .07       0
 5947.17     .12       0 6201.12     .07       0
#XS Ineff= 4 ,-1
                            5282 6076.65   58.57 6117.4711552.31   61.26
    -331    5048   57.35
Permanent Ineff=
       F       T       T       T
#Block Obstruct= 3 ,-1
 8493.73 8723.76   57.09 9588.88 9983.94   57.3111344.1311552.31   60.04
Bank Sta=5097.01,5160.34
XS Rating Curve= 0
Exp/Cntr=.3,.1

Type RM Length L Ch R = 1 ,228044.5,594.9,685.62,755.2
XS GIS Cut Line= 6
     3112652.242    13782722.098     3113184.372    13776938.221
     3113197.793    13776817.433     3113206.181    13776773.815
     3113196.457    13770137.789     3113192.834    13770076.206
#Sta/Elev= 30
       0   58.58   268.2   58.92  349.84   57.94  358.81      55  370.76   59.27
  445.76   57.94  528.42   80.77  605.42   59.91  630.96   56.79 5697.28   54.66
  5757.9   54.88 5771.78   59.25 5799.01   53.83 5817.03   46.01 5826.07   43.82
 5832.74   44.81 5862.34   54.28 5889.33    58.1  5940.6   54.61 6060.85   53.26
 6478.94   53.32 6560.85   53.51 6812.65   53.64 6841.39   57.25 6948.86   54.06
 7264.76   55.4410232.08   56.8110240.73   53.48 10250.7   56.68   12672   57.77
#Mann= 9 ,-1 , 0
       0     .07       0 5697.28     .12       0 5817.03    .041       0
 5832.74     .12       0 6478.94     .07       0 6560.85     .12       0
 6812.65     .07       0 6948.86     .12       0 7264.76     .07       0
#XS Ineff= 2 ,-1
       0     480      77 6851.8412836.84      59
Permanent Ineff=
       F       F
#Block Obstruct= 2 ,-1
   -4.75   840.1   57.6510068.9711285.09   56.66
Bank Sta=5799.01,5862.34
XS Rating Curve= 0
Exp/Cntr=.3,.1

Type RM Length L Ch R = 1 ,227358.8,739.19,928.33,829.42
XS GIS Cut Line= 6
      3112990.92    13783172.804     3113583.488    13778140.358
     3113865.899    13777112.886     3113853.828     13777066.33
     3113829.688    13776995.978     3114211.364    13770465.831
#Sta/Elev= 30
       0   57.32  794.63      55  874.09   57.94  961.57   80.77 1008.44   59.91
 1039.55   56.79 5160.06   55.14 5479.37   44.28 5545.34   44.91 5561.83    54.2
 5602.15   48.45 5675.95   54.23 6104.82   54.64 6157.55   59.32 6180.88   53.86
  6196.6   43.93 6201.34   43.99  6212.6    45.3 6239.78   53.64 6264.63   57.75
 6283.54   52.41 6628.33   49.22 6640.16   55.41 6665.01   54.15 6965.52   54.61
 7008.11   52.52 7270.19   55.61 7413.05   55.71 8718.51   55.3312796.86   56.61
#Mann= 11 ,-1 , 0
       0     .07       0 6104.82     .12       0 6201.34    .041       0
  6212.6     .12       0 6283.54     .07       0 6665.01     .12       0
 6965.52     .07       0 7008.11     .12       0 7270.19     .07       0
 7413.05     .12       0 8718.51     .07       0
#XS Ineff= 2 ,-1
       0     920      67 7358.3612796.86   57.51
Permanent Ineff=
       F       F
#Block Obstruct= 3 ,-1
  589.43 2085.86   57.01 5087.02 5770.99   54.02 6261.52 6647.88   54.07
Bank Sta=6180.88,6239.78
XS Rating Curve= 0
Exp/Cntr=.3,.1

Type RM Length L Ch R = 1 ,226430.5,698.15,888.29,987.79
XS GIS Cut Line= 6
     3113373.055    13783549.516     3114121.702    13778678.572
     3114682.879    13776841.479     3114681.499    13776799.751
     3114684.431    13776665.599     3115032.922    13770393.914
#Sta/Elev= 30
       0   57.45 1158.58      55 1304.62   59.29 1328.46   63.24  1355.6   80.77
  1378.6   59.91 1408.51   56.79 1418.74   80.77 1461.45   56.13 5737.45   55.71
 5894.88   50.53 6885.13   54.54 6911.21   59.21 6937.64   53.62 6964.63      46
 6972.47    42.8 7000.12   53.85 7009.88   55.77 7081.21   54.48 7217.55   49.47
 7332.54   54.88 7381.37   54.84 7599.43   56.24 7701.81   58.38 7791.62    49.4
 8606.36    49.4 8613.02   56.03 8662.14   54.97 9953.01   55.4413306.69   56.59
#Mann= 11 ,-1 , 0
       0     .07       0 6885.13     .12       0 6964.63    .041       0
 6972.47     .12       0 7009.88     .07       0 7081.21     .12       0
 7332.54     .07       0 7381.37     .12       0 7599.43     .07       0
 8662.14     .12       0 9953.01     .07       0
#XS Ineff= 2 ,-1
       0    1360    59.4 7660.9813306.69   57.57
Permanent Ineff=
       F       F
#Block Obstruct= 4 ,-1
  702.61 1429.71   57.22  5685.5 6540.46   54.92 7673.28 8720.61   54.79
12503.5913494.57   56.77
Bank Sta=6937.64,7000.12
XS Rating Curve= 0
Exp/Cntr=.3,.1

Type RM Length L Ch R = 1 ,225542.2,543.46,506.52,476.16
XS GIS Cut Line= 6
     3113753.696    13783901.559     3114677.277    13779095.254
     3115278.284    13777321.183     3115352.775     13777265.66
     3115750.031    13775039.878      3115982.18    13769681.351
#Sta/Elev= 30
       0   55.64  523.23   60.36  751.48   54.85 1729.15   56.59 1753.01   59.63
 1777.62   80.77 1793.36   56.79 1803.23   80.77 1839.75   55.85 1880.31   54.98
 5849.87   54.12 6154.34   58.45 6182.54   52.98 6749.94   53.85 6777.55   58.18
 6797.96   53.42 6812.87   46.98 6826.47   47.81 6830.71   43.09 6835.49   43.22
 6861.01   53.51 7110.57   53.87 7886.16   53.56  7924.5   57.46 8006.33   54.09
 9238.44   54.1314295.36   58.7114327.86   50.4714375.78   61.1814487.05   57.62
#Mann= 9 ,-1 , 0
       0     .07       0 5849.87     .12       0 6154.34     .07       0
 6182.54     .07       0 6749.94     .12       0 6826.47    .041       0
 6835.49     .12       0 7110.57     .07       0 9238.44     .07       0
#XS Ineff= 2 ,-1
       0    1795      60 7924.5714487.05   56.93
Permanent Ineff=
       F       F
#Block Obstruct= 2 ,-1
 -135.74  1831.2   57.0114236.2614499.01    57.5
Bank Sta=6797.96,6861.01
XS Rating Curve= 0
Exp/Cntr=.5,.3

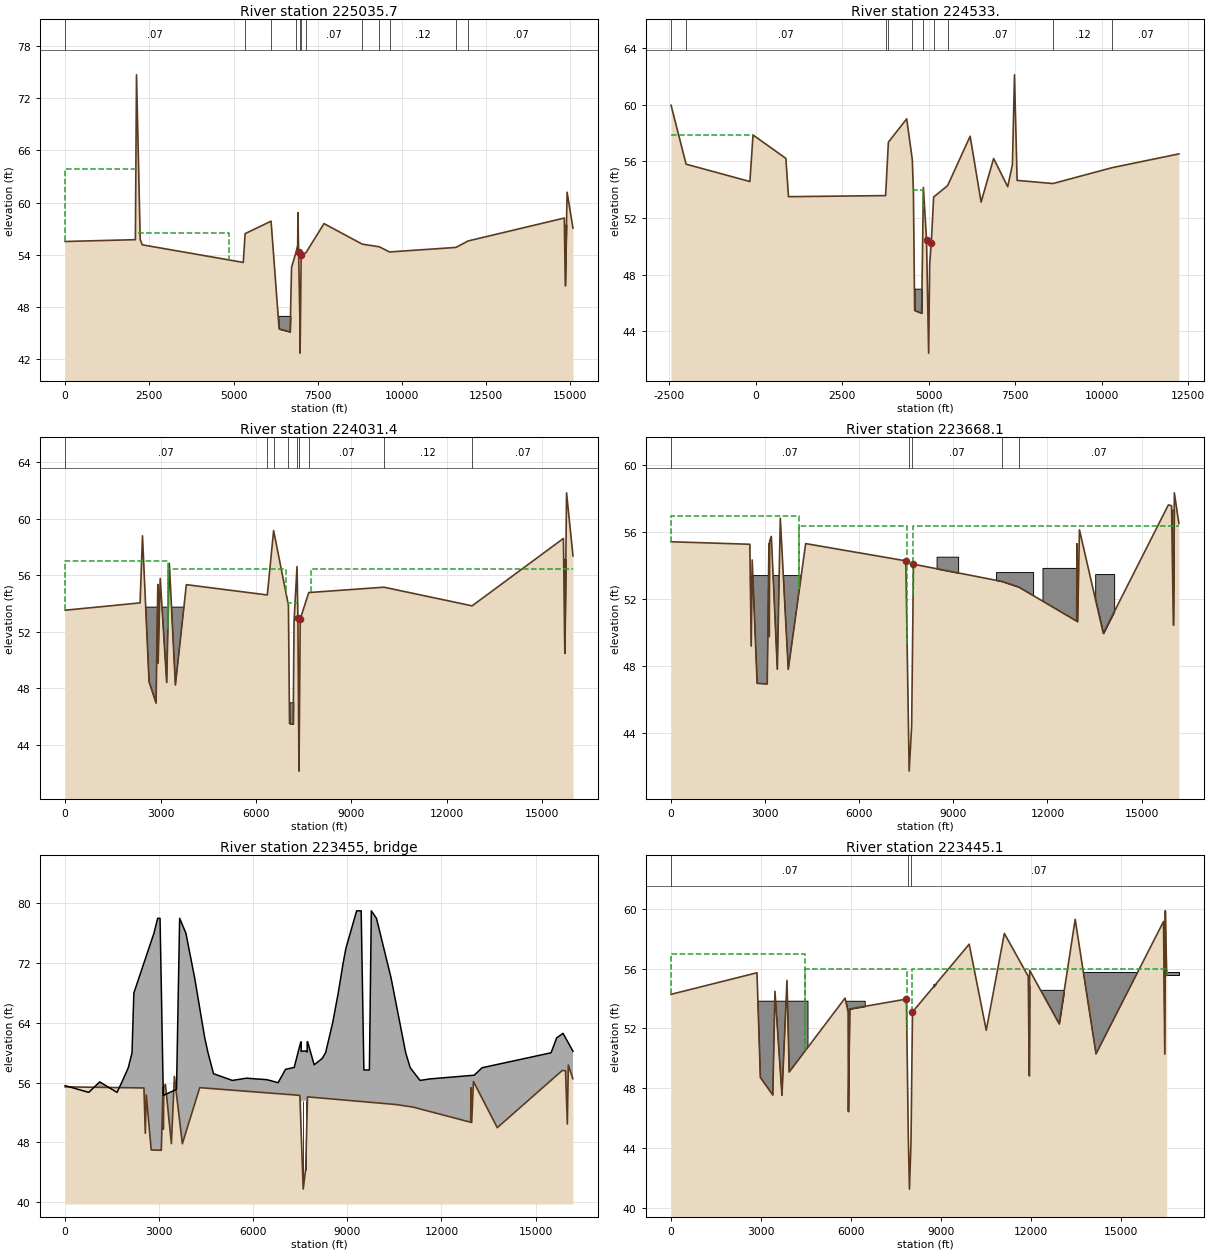
Type RM Length L Ch R = 1 ,225035.7,576.54,502.16,120.21
XS GIS Cut Line= 6
     3114510.755    13784483.448     3115163.406    13779425.127
     3115597.627    13777665.356     3115722.123    13777616.731
     3116189.246    13775252.354     3116243.002    13769627.013
#Sta/Elev= 30
       0   55.53  2084.9   55.74 2118.29   74.64 2228.91   55.74  2291.5   55.15
 5289.39   53.13 5344.81   56.43 6115.36   57.86  6354.7    45.5 6681.34   45.17
 6723.47   52.56 6853.13   54.25 6905.15   55.08 6913.48   58.84 6933.45   54.32
 6973.72   46.02 6977.02   42.73  6997.1   49.25  7008.4   54.03 7148.34   54.23
 7687.99   57.58 8821.42   55.23 9331.67   54.92 9633.92   54.3311605.53   54.85
11967.08   55.5914824.54   58.2214854.15   50.4714907.61   61.1815082.33   57.06
#Mann= 12 ,-1 , 0
       0     .07       0 5344.81     .12       0 6115.36    .035       0
 6853.13     .12       0 6973.72    .041       0  6997.1     .12       0
 7148.34     .07       0 8821.42     .12       0 9331.67     .07       0
 9633.92     .12       011605.53     .12       011967.08     .07       0
#XS Ineff= 4 ,-1
       0    2150    63.8    2150 4875.82    56.5 7664.2415082.33    56.5
 6180.28 6853.13      54
Permanent Ineff=
       F       F       F       T
#Block Obstruct= 2 ,-1
14781.4914952.58   57.46    6300    6700      47
Bank Sta=6933.45,7008.4
XS Rating Curve= 0
Exp/Cntr=.5,.3

Type RM Length L Ch R = 1 ,224533. ,576.55,502.16,120.22
BEGIN DESCRIPTION:
Added XS
END DESCRIPTION:
XS GIS Cut Line= 6
      3115150.65     13785455.95     3115699.087     13779802.46
     3115976.081     13777964.67     3116052.174     13777817.33
      3116294.03     13775411.66       3116338.8     13770867.36
#Sta/Elev= 30
-2442.03   59.97-2007.41  55.803  -164.6  54.577   -74.2  57.869     875  56.212
  950.33  53.505 3756.18  53.581 3836.73   57.36 4365.98   59.01 4528.09   56.12
 4559.27   53.89 4595.36   45.46 4797.13   45.26 4848.32   54.16 4939.33  50.418
    5000   42.44 5030.36  48.759 5076.25  50.242 5144.39  53.479 5548.02  54.287
 6198.83  57.781 6515.42  53.123 6877.81  56.207 7284.28  54.211 7419.96  55.765
 7480.26  62.123 7555.64  54.657 8590.67  54.43410301.43  55.55712229.42   56.53
#Mann= 10 ,-1 , 0
-2442.03     .07       0-2007.41     .07       0 3756.18     .12       0
 3836.73     .12       0 4528.09    .035       0 4848.32    .041       0
 5144.39     .12       0 5548.02     .07       0 8590.67     .12       0
10301.43     .07       0
#XS Ineff= 2 ,-1
-2442.03   -74.2   57.87 4559.28  4839.7      54
Permanent Ineff=
       F       T
#Block Obstruct= 1 ,-1
    4500    4800      47
Bank Sta=4939.33,5076.25
XS Rating Curve= 0
Exp/Cntr=.3,.1

Type RM Length L Ch R = 1 ,224031.4,231.14,363.27,243.31
XS GIS Cut Line= 6
     3115901.762    13785570.888     3116347.808    13778349.756
     3116360.437    13778216.727     3116360.437    13778193.153
     3116372.224    13778068.544     3116462.235    13769613.565
#Sta/Elev= 30
       0   53.52 2356.18   54.04 2431.53   58.79 2638.74   48.46 2858.64   46.95
 2914.07   55.34 2923.08   49.78 2989.28   55.76 3193.11   48.41  3275.9   56.84
 3466.69   48.23 3811.33   55.33 6357.94    54.6 6556.47   59.16 7022.38   53.87
 7057.06    45.5 7171.64   45.47 7198.52    52.7  7292.3   56.61 7320.67      53
 7349.08   43.79 7354.65   42.13 7393.44   52.89 7660.89   54.7710026.02   55.15
12799.39   53.8315671.91    58.615715.58   50.4715770.51   61.8315972.81   57.37
#Mann= 10 ,-1 , 0
       0     .07       0 6357.94     .12       0 6556.47     .12       0
 7022.38    .035       0  7292.3     .12       0 7349.08    .041       0
 7354.65     .12       0 7660.89     .07       010026.02     .12       0
12799.39     .07       0
#XS Ineff= 4 ,-1
       0    3230      57    3230  6955.2   56.41 7718.2215972.81   56.41
 7022.38 7298.52      54
Permanent Ineff=
       F       F       F       T
#Block Obstruct= 4 ,-1
 2393.89 3859.54   53.7414533.1614756.91   56.0615584.7315780.15   57.15
    7000    7200      47
Bank Sta=7320.67,7393.44
XS Rating Curve= 0
Exp/Cntr=.5,.3

Type RM Length L Ch R = 1 ,223668.1,563.76,222.98,668.49
XS GIS Cut Line= 6
     3116214.724    13785795.124     3116303.285    13781337.234
     3116719.097    13778229.074     3116516.856    13776560.629
      3116798.73    13774698.168     3116588.123    13769693.163
#Sta/Elev= 30
       0   55.44 2511.25   55.29 2555.43   49.22 2585.88   54.35  2743.9   46.99
 3065.54   46.95 3120.45   55.34 3129.85   49.78 3145.55   55.49  3196.5   55.76
  3387.7   47.83 3482.03   56.84 3736.15   47.82 4290.57   55.33 7483.58    54.3
 7590.29   41.75 7669.49   44.44  7727.1    54.110554.05   53.07 11091.9   52.73
12931.12    50.712938.31   55.3212962.28   50.6613019.31   56.1513778.99   49.97
15854.06   57.6415955.42   57.5916013.07   50.4716044.29   58.3616188.44   56.53
#Mann= 5 ,-1 , 0
       0     .07       0 7590.29    .041       0 7669.49     .07       0
10554.05     .12       0 11091.9     .07       0
#XS Ineff= 3 ,-1
       0    4090      57    4090 7526.65    56.4 7716.0616188.44    56.4
Permanent Ineff=
       F       F       F
#Block Obstruct= 8 ,-1
 2143.51  4177.1   53.42 7007.63 7282.44   53.59 8464.12 9151.15   54.55
10360.3111541.98   53.6311856.6613085.32   53.8513520.6114125.19   53.51
15484.4915750.63   55.6715911.4516076.34   57.36
Bank Sta=7483.58,7727.1
XS Rating Curve= 0
Exp/Cntr=.5,.3

Type RM Length L Ch R = 3 ,223455  ,,,
BEGIN DESCRIPTION:
SH288
END DESCRIPTION:
Bridge Culvert--1,0,-1,-1, 0
Deck Dist Width WeirC Skew NumUp NumDn MinLoCord MaxHiCord MaxSubmerge Is_Ogee
5,212,2.6,0, 61, 61, , , .95, 0, 0,0,,
       0     750    1100    1653    1800    2012    2131    2190    2830    2950
    3025    3129    3550    3650    3850    4130    4290    4450    4555    4730
    5330    5780    6434    6790    7025    7303    7513    7526    7527    7582
    7662    7715    7716    7717    7730    7731    7940    8193    8304    8529
    8707    8863    8953    9294    9439    9525    9701    9762    9926   10044
   10393   10859   11003   11315   11628   13045   13295   15494   15673   15877
   16193
    55.6    54.7    56.1    54.7      56      58      60      68      76      78
      78    54.3    55.1      78      76      70      66      62      60    57.2
    56.3    56.6    56.4      56   57.78   58.04   61.46   61.46   60.17   60.23
   60.24    60.1   60.16   61.46   61.48   61.48   58.39   59.23      60      64
      68      72      74      79      79    57.7    57.7      79      78      76
      70      60      58    56.3    56.5      57      58      60      62    62.6
    60.2
                                                                                
                                                                                
                                                                   53.44   53.59
   53.58   53.51
                                                                                
                                                                                
        
       0    1081    1431    1984    2131    2343    2462    2521    3161    3281
    3356    3460    3881    3981    4181    4461    4621    4781    4886    5061
    5661    6111    6765    7121    7356    7631    7841    7854    7855    7910
    7990    8043    8044    8045    8058    8059    8268    8521    8632    8857
    9035    9191    9281    9622    9767    9853   10029   10090   10254   10372
   10721   11187   11331   11643   11956   13373   13623   15822   16001   16205
   16521
    55.6    54.7    56.1    54.7      56      58      60      68      76      78
      78    54.3    55.1      78      76      70      66      62      60    57.2
    56.3    56.6    56.4      56   57.78   58.04   61.46   61.46   60.17   60.23
   60.24    60.1   60.16   61.46   61.48   61.48   58.39   59.23      60      64
      68      72      74      79      79    57.7    57.7      79      78      76
      70      60      58    56.3    56.5      57      58      60      62    62.6
    60.2
                                                                                
                                                                                
                                                                   53.44   53.59
   53.58   53.51
                                                                                
                                                                                
        
Pier Skew, UpSta & Num, DnSta & Num=  ,7585, 2 ,7913, 2 , 0 , 0 , 0 ,,
     1.5     1.5
       0      54
     1.5     1.5
       0      54
Pier Skew, UpSta & Num, DnSta & Num=  ,7665, 2 ,7993, 2 , 0 , 0 , 0 ,,
     1.5     1.5
       0      54
     1.5     1.5
       0      54
BR Coef=-1 , 1 , 1 ,1.25, 0 ,,,.8,-1,2,0,
WSPro=,,,, 1 ,,,, 0 ,,,, 0 ,,,,-1 ,-1 ,-1 , 0 , 0 , 0 , 0 , 0
BC Design=,, 0 ,, 0 ,,,,,,
BC HTab HWMax=58.36

Type RM Length L Ch R = 1 ,223445.1,255.74,576.43,626.14
XS GIS Cut Line= 6
     3116651.565    13786151.205     3116939.963    13783379.191
     3117017.924    13778801.996      3116934.05    13778307.669
     3117312.254    13776538.224     3116935.004     13769717.94
#Sta/Elev= 30
       0   54.28 2862.61   55.72 2975.67   48.72 3390.09   47.55 3460.81   54.48
 3695.13   47.53 3861.42   55.21  3935.8   49.09 5798.05   54.03 5898.71   53.08
 5907.38   46.45 5947.23    53.3 7840.55   53.96  7906.6   44.48  7942.4   41.26
 7994.03   44.44    8043    53.1  9932.4   57.6310500.75   51.8811103.57   58.35
11900.83   55.4811932.26   48.8411947.31   55.8812929.25   52.31 13463.7   59.29
14157.57    50.316407.41   59.1516448.36   50.2916467.05   59.8616513.13   55.55
#Mann= 3 ,-1 , 0
       0     .07       0  7906.6    .041       0 7994.03     .07       0
#XS Ineff= 3 ,-1
       0    4470      57    4470 7854.97      56 8043.3816513.13      56
Permanent Ineff=
       F       F       F
#Block Obstruct= 7 ,-1
    1843 2846.42   53.75 2803.05 4561.83   53.82 5733.79 6450.51   53.85
 8738.93 9206.11   54.9711816.7911981.68   54.8711979.5213085.32   54.58
13346.39 16918.1   55.74
Bank Sta=7840.55,8043
XS Rating Curve= 0
Exp/Cntr=.5,.3

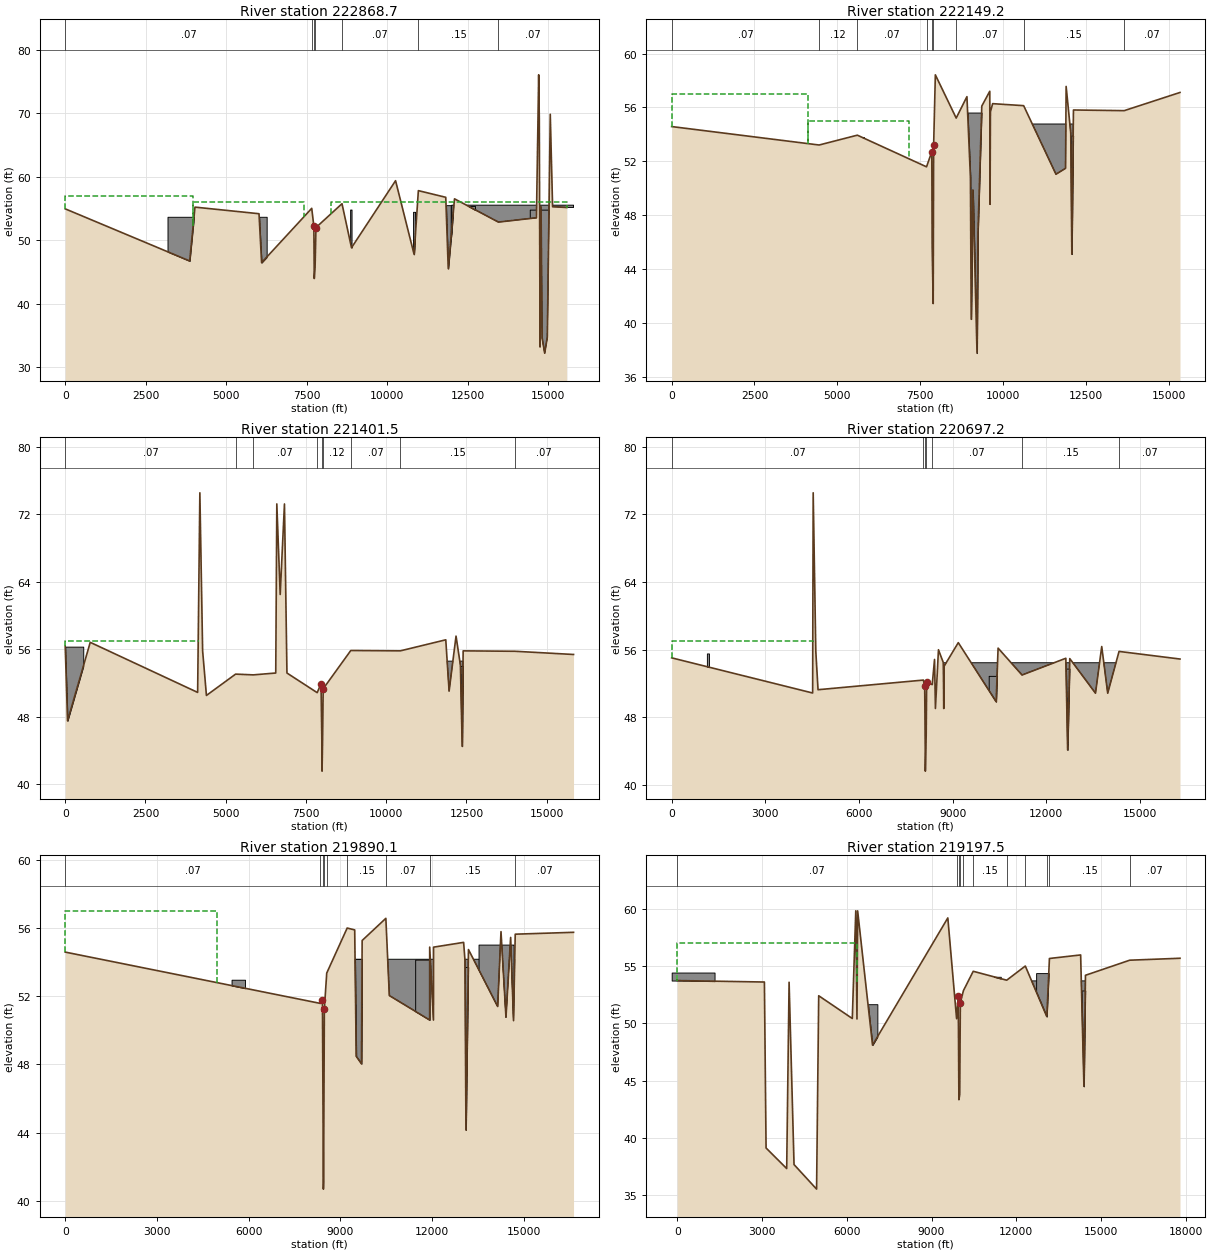
Type RM Length L Ch R = 1 ,222868.7,487.56,719.54,728.34
XS GIS Cut Line= 6
      3116933.32    13786339.993      3117285.74    13778742.104
     3117305.105    13778666.329     3117322.786    13778615.812
     3117352.254    13778500.465     3118662.394    13770896.576
#Sta/Elev= 30
       0   54.94 3863.77   46.72 4028.89   55.21 6015.99   54.17 6096.42   46.45
 7652.87   55.02 7718.51    52.2 7731.16   43.95 7756.78    45.7 7784.45   51.99
 8592.43   55.75 8887.24   48.8110255.49   59.3810830.61   47.7610962.94   57.81
11812.91   56.7611890.67   45.5112084.81   56.5213447.87   52.8514628.57   53.53
 14697.8   76.0714717.34   69.0914740.41   33.1814770.91   55.2614805.93   34.58
14884.91   32.1914966.11   34.7115057.55   69.8415129.69   55.28 15572.9   55.15
#Mann= 7 ,-1 , 0
       0     .07       0 7652.87     .12       0 7731.16    .041       0
 7756.78     .12       0 8592.43     .07       010962.94     .15       0
13447.87     .07       0
#XS Ineff= 3 ,-1
       0    3970      57    3970 7398.84      56 8238.84 15572.9      56
Permanent Ineff=
       F       F       F
#Block Obstruct= 10 ,-1
 3175.57 4543.51   53.69  5862.6 6253.44   53.69  8844.5 8888.51   54.83
 10798.410860.01   54.4711065.65 11554.2   55.9211749.6211993.89   55.52
11966.7412035.89   55.5212000.1915779.73   55.5212195.6812723.55   55.36
14436.6415047.33   54.74
Bank Sta=7718.51,7784.45
XS Rating Curve= 0
Exp/Cntr=.5,.3

Type RM Length L Ch R = 1 ,222149.2,733.91,747.68,686.89
XS GIS Cut Line= 6
     3117182.368     13786521.12     3117625.922    13780415.892
     3117987.085    13778844.822     3118012.343    13778707.584
     3118035.918    13778546.772     3119293.169    13771347.713
#Sta/Elev= 30
       0   54.58 4451.71   53.21 5604.74   53.94 7693.54   51.59 7852.71   52.71
 7863.13   45.74 7894.82   41.44 7908.07   53.19  7959.6   58.42 8589.03   55.21
  8913.2    56.8 9018.49   50.79 9042.22   40.28 9093.73   49.88 9217.74   37.76
  9245.6    46.7 9361.61    56.1 9602.72    57.2 9611.35   48.81 9622.36   55.67
 9689.44   56.2810625.35   56.1311600.96   51.0411890.73   51.4811907.48   57.56
12047.22   54.11 12079.6   45.1112128.82   55.8113660.58   55.7615345.02   57.11
#Mann= 9 ,-1 , 0
       0     .07       0 4451.71     .12       0 5604.74     .07       0
 7693.54     .12       0 7863.13    .041       0 7894.82     .12       0
 8589.03     .07       010625.35     .15       013660.58     .07       0
#XS Ineff= 3 ,-1
       0    4110      57    4110 7167.35      55 8640.4715345.02      55
Permanent Ineff=
       F       F       F
#Block Obstruct= 4 ,-1
 5471.76 5813.74   53.78 8867.18 9355.73   55.62 9524.8815641.42   54.77
11945.0412238.17   53.91
Bank Sta=7852.71,7908.07
XS Rating Curve= 0
Exp/Cntr=.5,.3

Type RM Length L Ch R = 1 ,221401.5,698.71,704.31,606.73
XS GIS Cut Line= 6
     3117605.854    13786801.621     3118301.088    13780749.878
     3118690.113    13779003.951     3118755.786    13778833.877
     3118764.205    13778801.883     3119899.075    13771147.156
#Sta/Elev= 30
       0   56.37   73.25   47.51  780.04   56.82 4125.28   50.88 4194.47   74.56
 4280.59   55.81 4399.26   50.52 5307.71   53.05  5858.8   52.96  6558.3   53.18
 6591.68   73.24 6696.81    62.5 6829.65   73.24 6907.14   53.18 7849.88   50.85
 7968.98   51.93  7997.2   44.44 8000.75   41.54 8018.59   45.47 8036.25   51.31
 8895.75   55.85 10439.4   55.8111854.74   57.1211958.08   51.0412174.31   57.56
12310.51   54.1112366.29   44.4912395.75   55.8114010.87   55.7615834.21   55.38
#Mann= 9 ,-1 , 0
       0     .07       0 5307.71     .12       0  5858.8     .07       0
 7849.88     .12       0  7997.2    .041       0 8018.59     .12       0
 8895.75     .07       0 10439.4     .15       014010.87     .07       0
#XS Ineff= 1 ,-1
       0    4160      57
Permanent Ineff=
       F
#Block Obstruct= 4 ,-1
 -122.14  561.83   56.31  678.77  841.66   55.17 8870.0714755.17   54.59
12238.1712433.59   54.02
Bank Sta=7968.98,8036.25
XS Rating Curve= 0
Exp/Cntr=.3,.1

Type RM Length L Ch R = 1 ,220697.2,861.67,807.02,470.15
XS GIS Cut Line= 6
     3118201.204    13787183.363     3118996.045    13780830.428
     3119358.622     13779254.01     3119386.406    13779152.976
     3119404.929    13779093.198     3120438.008    13771064.243
#Sta/Elev= 30
       0   55.04 4515.53   50.88 4532.97   74.56 4616.77   55.81 4688.53   51.27
 8061.63   52.41 8104.85   51.73 8122.16   44.16 8125.62   41.64 8152.56   45.81
 8168.09   52.21 8346.18   51.87 8420.14   54.85 8448.74   49.05 8545.99      56
 8701.96   54.47 8715.69   49.05 8723.41   54.03 9180.77   56.8410393.35   49.85
10455.54   56.1911222.96   53.0112625.74   54.9912683.21   44.1512751.62   54.95
13575.64   50.8613775.67   56.3813966.91   50.8614330.19    55.816282.59    54.9
#Mann= 7 ,-1 , 0
       0     .07       0 8061.63     .12       0 8122.16    .041       0
 8152.56     .12       0 8346.18     .07       011222.96     .15       0
14330.19     .07       0
#XS Ineff= 1 ,-1
       0    4520      57
Permanent Ineff=
       F
#Block Obstruct= 4 ,-1
  1127.9 1193.99   55.56 8583.7715509.18   54.46 10154.610478.58   52.91
12613.9112746.45   53.77
Bank Sta=8104.85,8168.09
XS Rating Curve= 0
Exp/Cntr=.3,.1

Type RM Length L Ch R = 1 ,219890.1,992.06,692.67,447.28
XS GIS Cut Line= 6
      3118937.03      13787675.8     3120079.331      13779396.3
     3120093.645    13779342.415     3120099.538    13779302.001
     3120116.377    13779244.749     3120603.834    13771147.156
#Sta/Elev= 30
       0   54.58  8348.8   51.57 8413.68   51.79 8427.05   47.34 8444.88   40.68
 8452.07   41.11 8476.43   51.24 8554.14   53.35 9222.96   55.99 9469.06   55.88
 9519.13   48.47  9691.3   48.03 9712.67   55.2610487.95   56.5610602.21   52.03
11919.32    50.611922.39   54.8712045.38    50.612048.46   54.8713031.61   55.15
 13075.7   54.1113108.26   44.1513190.09   54.7314145.01   51.3914254.26   55.78
14417.11   50.7614569.55   55.4414663.96   50.5614719.81   55.6316626.77   55.74
#Mann= 9 ,-1 , 0
       0     .07       0  8348.8     .12       0 8427.05    .041       0
 8452.07     .12       0 8554.14     .07       0 9222.96     .15       0
10487.95     .07       011919.32     .15       014719.81     .07       0
#XS Ineff= 1 ,-1
       0    4980      57
Permanent Ineff=
       F
#Block Obstruct= 8 ,-1
 5441.22 5880.92   52.96 8863.4216057.45   54.16 9370.99 9755.73   54.18
 11447.111938.57   54.1412163.8212409.56   54.0113025.9513218.32   53.71
13535.8414682.59   54.9913633.6717242.32   50.34
Bank Sta=8413.68,8476.43
XS Rating Curve= 0
Exp/Cntr=.3,.1

Type RM Length L Ch R = 1 ,219197.5,726.04,723.76,723.43
XS GIS Cut Line= 6
 3120584.423381613789051.6366337 3120786.4111666  13779385.83838
 3120777.307838413779158.8700019 3120742.787894313779072.1490468
 3120723.423103613779027.5261045 3120862.936932213771271.5248843
#Sta/Elev= 30
       0   53.75  3085.4   53.62  3144.4    39.1  3874.4    37.3  3959.4    53.6
  4134.4   37.65  4932.4    35.5  5007.4   52.42 6196.49   50.43 6319.51   59.85
 6362.05   50.39 6385.41   59.85 6911.96    48.1 9577.08   59.23    9888   50.41
 9946.26   52.44 9969.22   43.32 9999.36   43.7910020.09   51.7810128.32   52.86
10476.54   54.5611661.39   53.78 12319.8   55.0213080.02    50.613173.71   55.68
14277.76   55.9914394.76   44.4914448.94   54.2116014.94   55.5317794.38    55.7
#Mann= 11 ,-1 , 0
       0     .07       0    9888     .12       0 9969.22    .041       0
 9999.36     .12       010128.32     .07       010476.54     .15       0
11661.39     .07       0 12319.8     .15       013080.02     .07       0
13173.71     .15       016014.94     .07       0
#XS Ineff= 1 ,-1
       0    6370      57
Permanent Ineff=
       F
#Block Obstruct= 8 ,-1
 -196.39 1320.92   54.45 6717.56 7083.97   51.68 8236.63 8805.46   52.25
10763.9616988.59   53.7211206.1111450.38   54.0812702.2913160.31    54.4
14290.0814473.28   52.8815494.8815813.42   54.62
Bank Sta=9946.26,10020.09
XS Rating Curve= 0
Exp/Cntr=.3,.1

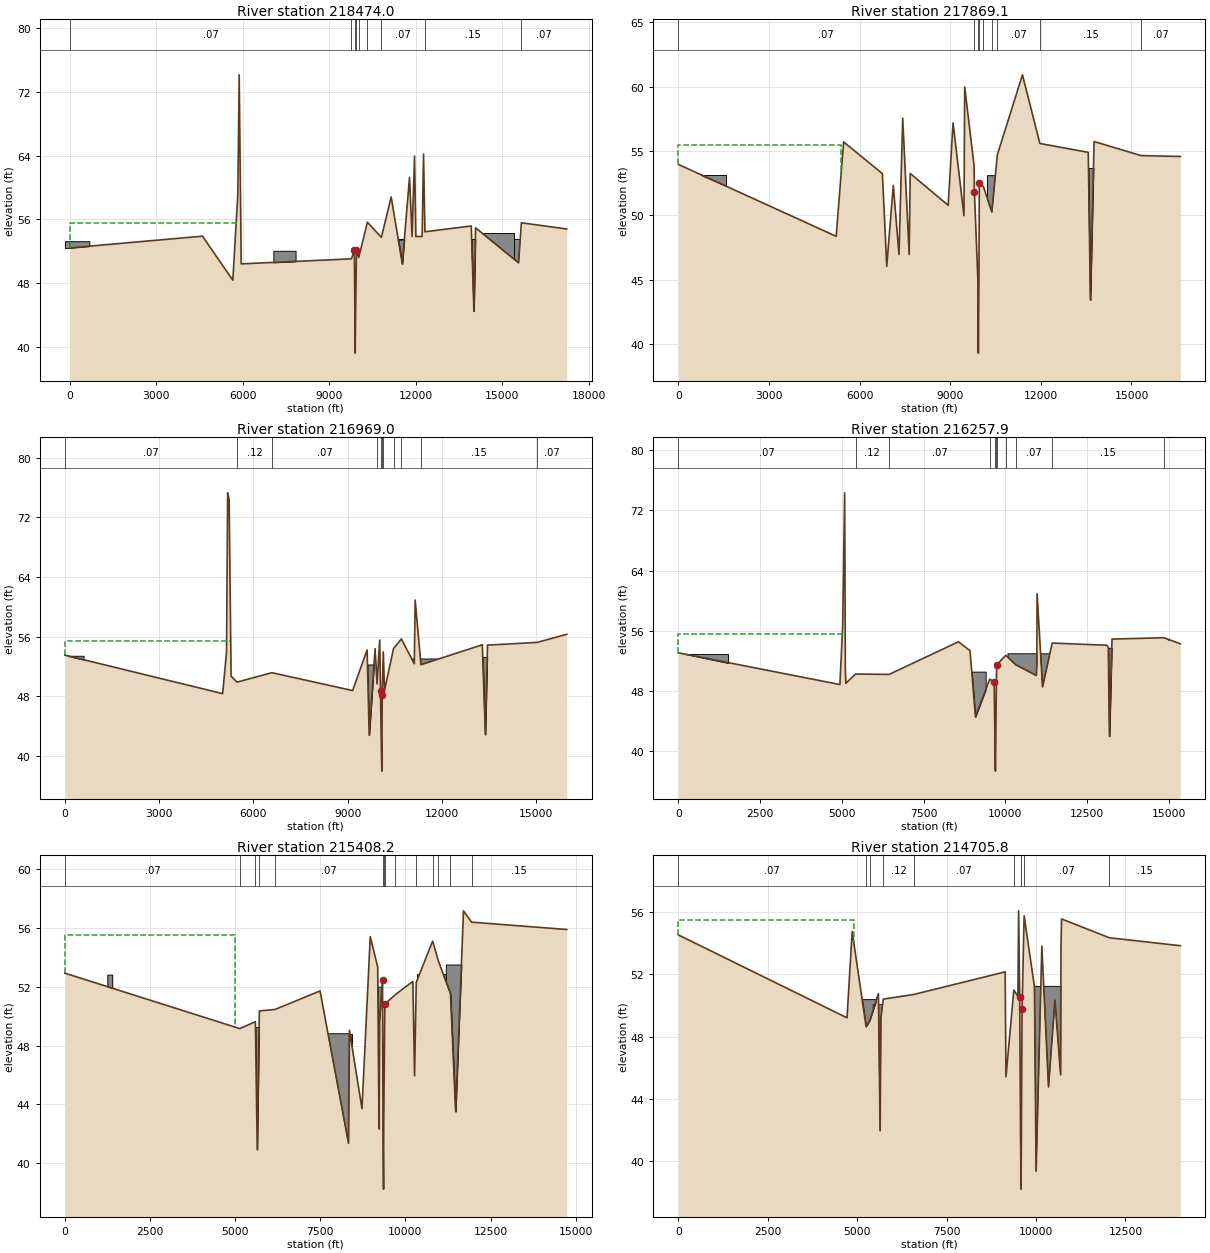
Type RM Length L Ch R = 1 ,218474.0,688.04,604.85,606.72
XS GIS Cut Line= 6
     3122355.789    13788649.354     3121447.501    13778886.078
     3121434.029    13778862.503     3121418.032    13778836.403
     3121375.935    13778746.314     3121173.861    13771478.807
#Sta/Elev= 30
       0   52.43  4606.2    53.9 5657.23   48.38 5830.92   59.16 5877.65   74.11
 5948.34   50.43 9768.33   51.06 9870.02   52.11 9893.12   42.51 9898.81   39.25
 9911.86   43.81 9943.78   52.1310022.38   51.2310321.44   55.6510806.71   53.75
11147.12   58.8211533.15   50.43 11782.3   61.2711871.48   53.8611955.82   63.93
12002.17   53.8612219.79   53.8612267.81   64.1712317.27   54.4513922.43   55.18
 14015.8   44.4914073.03   54.9515562.53   50.5615660.52   55.5817232.98    54.8
#Mann= 9 ,-1 , 0
       0     .07       0 9768.33     .12       0 9893.12    .041       0
 9911.86     .12       010022.38     .07       010321.44     .15       0
10806.71     .07       012317.27     .15       015660.52     .07       0
#XS Ineff= 1 ,-1
       0    5860    55.5
Permanent Ineff=
       F
#Block Obstruct= 7 ,-1
 -164.89  682.64   53.27  7062.6 7832.06   52.0710338.3616410.28   53.49
11201.3711610.92   53.4712511.9513781.57   54.4213877.8614152.67   53.53
14170.6515419.79   54.27
Bank Sta=9870.02,9943.78
XS Rating Curve= 0
Exp/Cntr=.3,.1

Type RM Length L Ch R = 1 ,217869.1,722.78,900.17,1017.36
XS GIS Cut Line= 6
      3123516.13      13788230.5     3121919.835    13778518.988
     3121881.105     13778450.79     3121868.476    13778414.586
     3121837.324    13778359.017     3121898.366    13771763.972
#Sta/Elev= 30
       0   53.96 5222.36   48.38 5469.91   55.71 6753.45   53.25  6896.7   46.05
 7113.26   52.33 7302.42   46.97 7425.91   57.55 7639.02   46.97 7674.75   53.26
 8930.87   50.79 9092.53   57.19 9453.95   49.98 9477.72   59.98 9788.04   53.87
 9799.48   51.81 9914.26   45.04 9929.16   39.31 9949.14   45.01 9963.01   52.53
10098.48   52.2310377.38   50.2710559.98   54.7211390.65   60.9211967.17   55.59
13569.29    54.913640.84   43.4413761.46   55.7415316.48   54.6516617.82   54.58
#Mann= 9 ,-1 , 0
       0     .07       0 9788.04     .12       0 9914.26    .041       0
 9949.14     .12       010098.48     .07       010377.38     .15       0
10559.98     .07       011967.17     .15       015316.48     .07       0
#XS Ineff= 1 ,-1
       0    5380    55.5
Permanent Ineff=
       F
#Block Obstruct= 3 ,-1
 -232.73 1560.79   53.1510234.7815911.92   53.0913465.6513740.46   53.69
Bank Sta=9799.48,9963.01
XS Rating Curve= 0
Exp/Cntr=.3,.1

Type RM Length L Ch R = 1 ,216969.0,553.93,711.09,850.7
XS GIS Cut Line= 6
     3124070.829    13788055.033     3122655.278    13778192.311
     3122662.014     13778144.32      3122664.54    13778041.602
     3122662.014    13777979.297     3122741.517    13772185.547
#Sta/Elev= 30
       0   53.54 5020.99   48.38 5144.14   53.92  5180.3    75.3  5227.5   74.34
 5290.21   50.72  5479.2   49.92 6588.49   51.19 9156.68   48.79 9618.44   54.24
 9684.74    42.8 9873.21   54.41 9934.57   49.6810019.13   55.56 10044.6   48.74
10065.48   42.8410087.06   37.9910097.85   48.2310133.53   53.9910173.46   48.84
10459.78   54.4310708.21   55.7111120.09   52.3911147.78   60.92 11332.1   52.26
13285.22   54.9313382.69   42.8913449.63   54.8815034.86   55.2515971.71   56.34
#Mann= 11 ,-1 , 0
       0     .07       0  5479.2     .12       0 6588.49     .07       0
 9934.57     .12       010065.48    .041       010087.06     .12       0
10133.53     .07       010459.78     .15       010708.21     .07       0
 11332.1     .15       015034.86     .07       0
#XS Ineff= 1 ,-1
       0    5240    55.5
Permanent Ineff=
       F
#Block Obstruct= 4 ,-1
   94.55  594.12   53.46 9576.95 9871.72   52.2910493.3615791.34   53.02
13243.1613455.03   53.31
Bank Sta=10044.6,10097.85
XS Rating Curve= 0
Exp/Cntr=.3,.1

Type RM Length L Ch R = 1 ,216257.9,662.77,849.66,814.57
XS GIS Cut Line= 6
     3124438.742    13787941.829     3123308.632     13778416.27
     3123328.839    13778316.078     3123333.048    13778280.716
     3123354.097    13778164.527     3123609.427     13772670.68
#Sta/Elev= 30
       0   53.05 4937.01   48.83 5023.54   56.72 5082.07   74.34 5104.03   50.72
 5119.58      49  5415.6   50.23 6442.59   50.18 8561.99   54.52 8916.64   53.34
  9081.8   44.54 9518.63   49.55 9656.44    49.2  9689.2   37.58 9694.59   37.31
 9714.53   45.83  9730.2   51.4410011.23   52.7210313.32   51.4710946.06   50.03
10960.75   51.6310967.53   60.9211135.35   48.5211428.76   54.3513103.11   54.06
13145.27   53.7513181.36   41.9413258.72   54.8814846.18   55.0615348.06   54.25
#Mann= 11 ,-1 , 0
       0     .07       0  5415.6     .12       0 6442.59     .07       0
 9518.63     .12       0  9689.2    .041       0 9714.53     .12       0
  9730.2     .07       010011.23     .15       010313.32     .07       0
11428.76     .15       014846.18     .07       0
#XS Ineff= 1 ,-1
       0    5070    55.5
Permanent Ineff=
       F
#Block Obstruct= 6 ,-1
  -70.68 1514.91   52.89 8964.89 9394.81   50.5510078.5314007.46   52.92
12492.2112746.26   53.19 13068.713303.21   53.7314034.1314998.86   54.93
Bank Sta=9656.44,9730.2
XS Rating Curve= 0
Exp/Cntr=.3,.1

Type RM Length L Ch R = 1 ,215408.2,548.47,702.41,663.83
XS GIS Cut Line= 6
     3124687.791    13787868.247     3124128.691    13778609.076
     3124113.536    13778544.246     3124105.959    13778518.146
     3124094.171    13778460.051     3124395.388    13773158.413
#Sta/Elev= 30
       0   52.93  5136.8   49.16 5594.85   49.63 5649.37   40.93 5711.11   50.36
 6171.98   50.46 7494.26   51.72 8331.05   41.35 8356.75   49.05 8725.68   43.72
 8968.93   55.42    9187   53.34 9226.72   42.35 9234.83   49.67 9329.25   52.47
 9345.25   41.65 9359.06   38.24 9364.67   42.67 9396.55   50.83 9700.79   51.46
 10219.6   52.3710270.19   45.9510319.52    52.310800.11   55.1110971.06   53.75
11324.19   51.5411477.27   43.5111706.91   57.1711944.78    56.414739.28    55.9
#Mann= 14 ,-1 , 0
       0     .07       0  5136.8     .12       0 5594.85     .07       0
 5711.11     .12       0 6171.98     .07       0 9345.25     .12       0
 9364.67    .041       0 9396.55     .12       0 9700.79     .07       0
10319.52     .15       010800.11     .07       010971.06     .15       0
11324.19     .07       011944.78     .15       0
#XS Ineff= 1 ,-1
       0    5000    55.5
Permanent Ineff=
       F
#Block Obstruct= 6 ,-1
 1246.34 1390.47   52.83 5545.04 5740.46   49.27 7474.81 8427.48   48.81
 9187.01 9295.76   52.0110355.8213844.48   52.8311187.7911725.19   53.52
Bank Sta=9329.25,9396.55
XS Rating Curve= 0
Exp/Cntr=.3,.1

Type RM Length L Ch R = 1 ,214705.8,640.07,904.08,808.98
XS GIS Cut Line= 6
       3124942.5    13787862.587     3124768.574     13778377.54
     3124760.996    13778327.023     3124755.102    13778299.239
     3124750.051    13778257.141     3125067.477    13773843.634
#Sta/Elev= 30
       0   54.53 4713.45   49.21 4857.59   54.75 5245.78   48.65 5345.54   49.03
 5591.29   50.76 5639.06   41.96 5661.17   49.21 5727.76   50.41 6580.82   50.71
 9135.05   52.16 9158.19   45.42 9377.99   50.99 9492.16   50.59 9511.92   56.08
 9541.95   50.57 9566.72   41.34 9580.04   38.21 9608.54   49.78 9666.27   55.76
 9954.65    51.210001.01   39.3710161.08   53.8210347.61   44.7810528.33   50.34
10686.67   45.5510696.22   53.8810712.62   55.5612049.73   54.3514033.44   53.84
#Mann= 10 ,-1 , 0
       0     .07       0 5245.78     .12       0 5345.54     .07       0
 5727.76     .12       0 6580.82     .07       0 9377.99     .12       0
 9566.72    .041       0 9580.04     .12       0 9666.27     .07       0
12049.73     .15       0
#XS Ineff= 1 ,-1
       0    4900    55.5
Permanent Ineff=
       F
#Block Obstruct= 5 ,-1
 4841.87 5515.36   50.41 5447.33 5716.03   50.05 8647.33 8989.31   50.38
  9868.7 10845.8   51.23 13349.1 14466.1   52.74
Bank Sta=9541.95,9608.54
XS Rating Curve= 0
Exp/Cntr=.3,.1