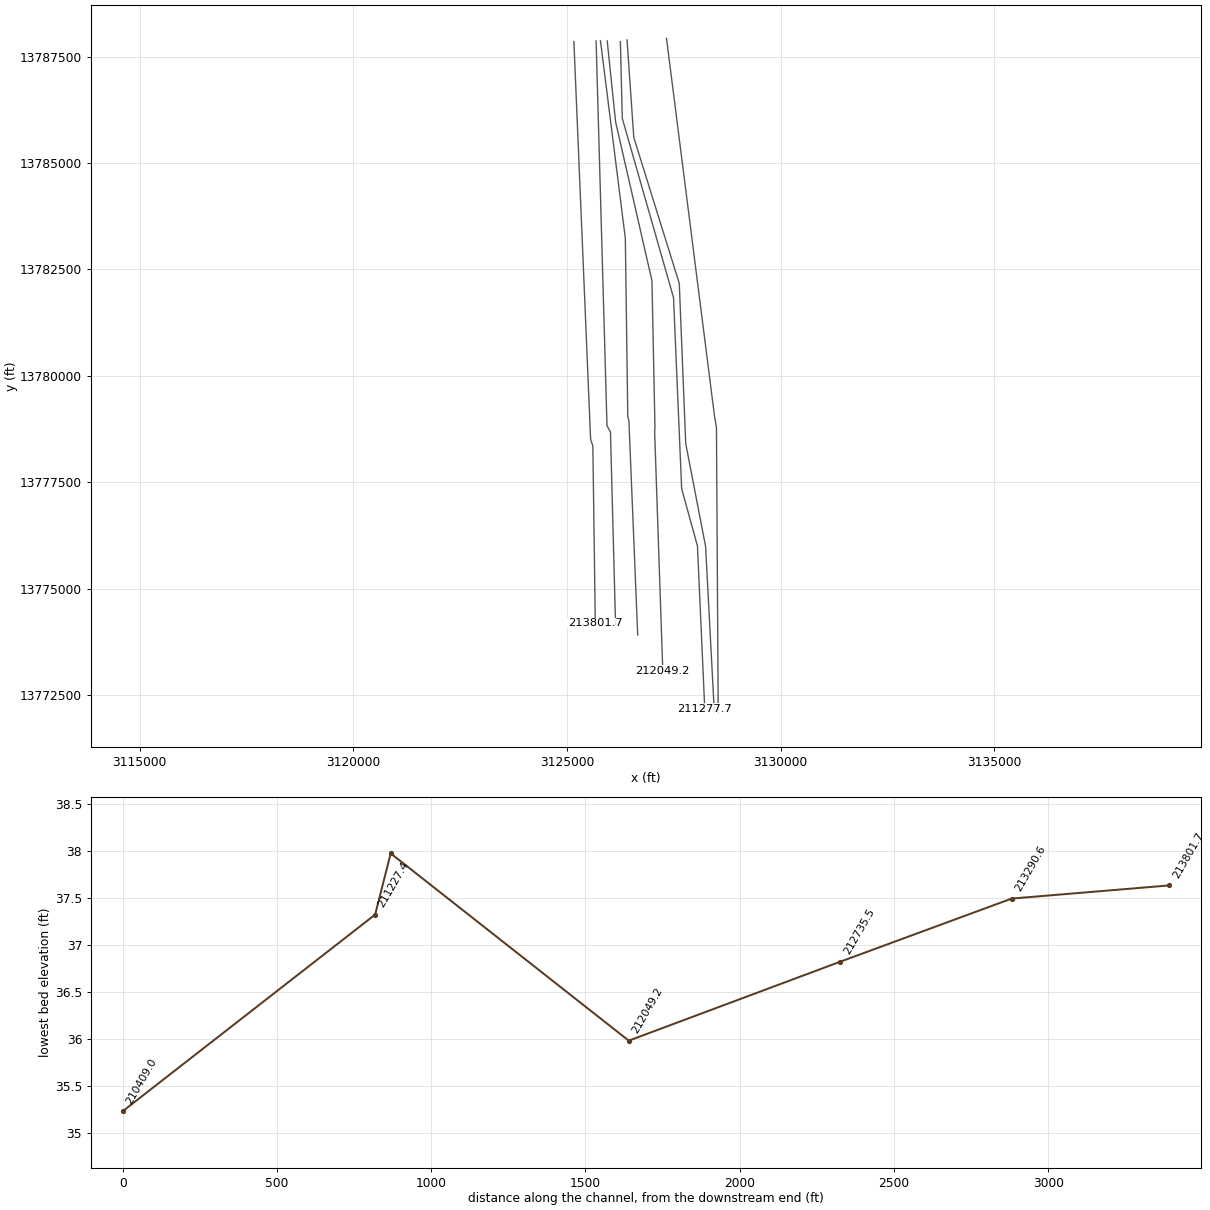
HEC-RAS study A100-00-00.prj: A100-00-00

--- A100-00-00.g01 (geometry) --- (continued)

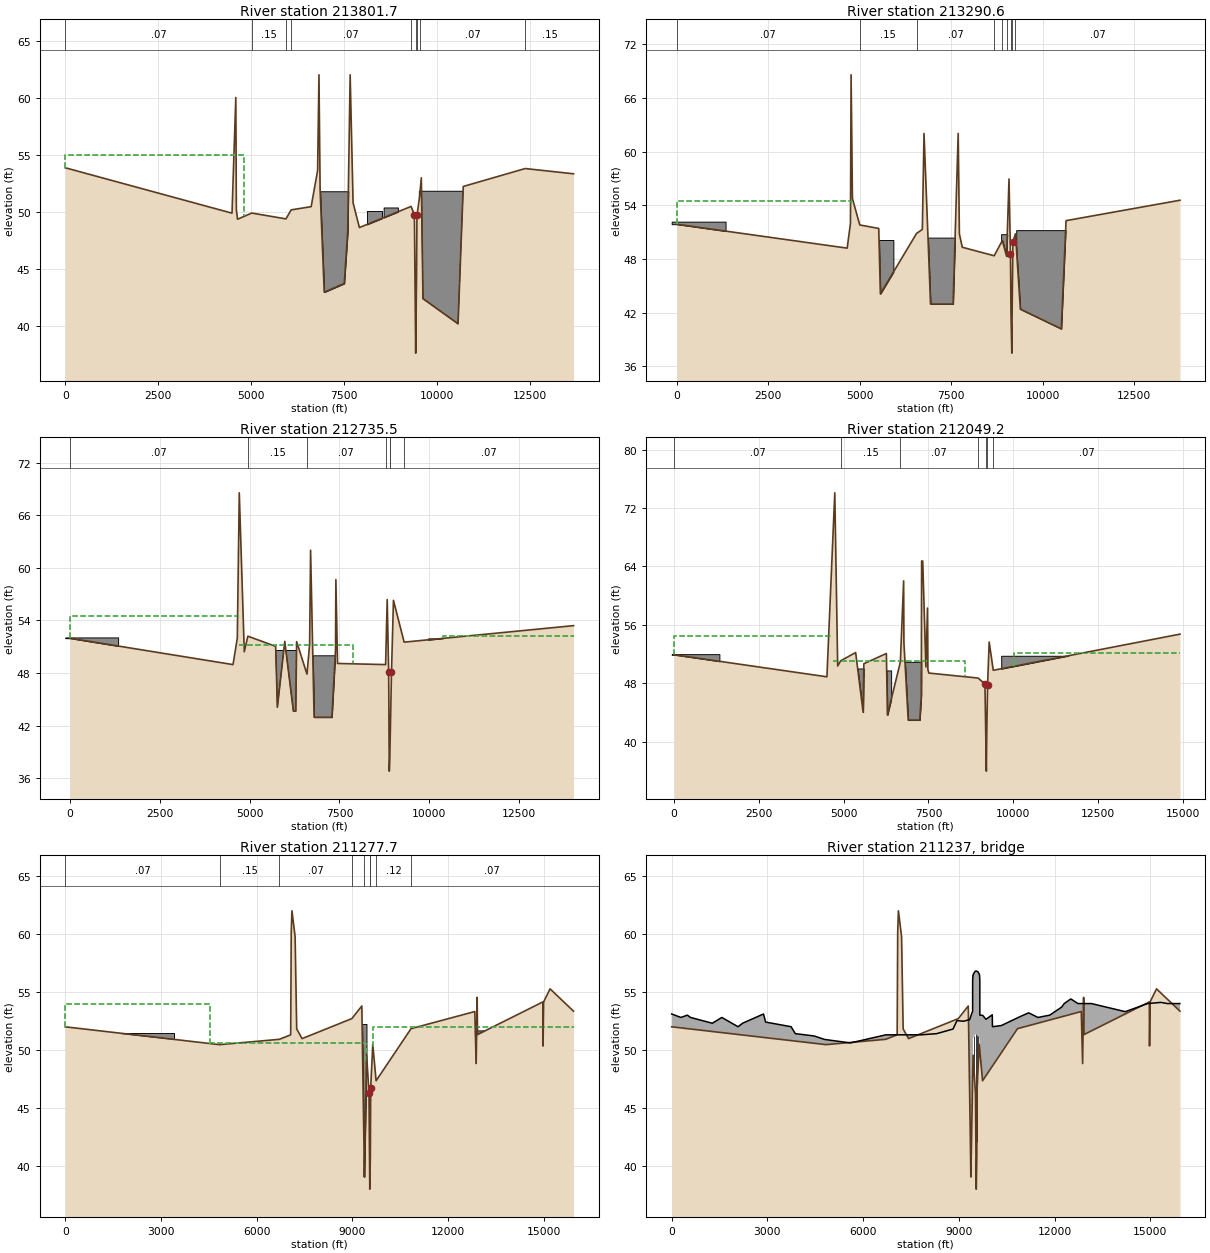
Type RM Length L Ch R = 1 ,213801.7,425.57,511.15,438.05
XS GIS Cut Line= 6
     3125164.044    13787854.107     3125554.955    13778518.988
      3125570.11    13778464.261     3125586.107     13778416.27
     3125607.998    13778352.281     3125665.194    13774187.774
#Sta/Elev= 30
       0   53.87 4490.33   49.89 4592.48   60.02 4606.74   50.21 4638.67   49.36
 5022.97    49.9 5941.37   49.39 6083.75   50.18  6620.6   50.46 6794.45   53.63
 6830.78   62.01 6861.71    51.9 6972.65   42.97 7511.37   43.73 7604.68   48.24
 7670.16   62.01 7749.22    50.8 7919.11   48.63 9309.78   50.48 9399.77   49.75
  9434.5   37.63 9457.41   44.48 9468.54   49.69 9539.58   51.33  9585.9   52.99
 9630.23    42.4 10574.4    40.210714.86   52.2312382.62    53.8 13683.2   53.34
#Mann= 9 ,-1 , 0
       0     .07       0 5022.97     .15       0 5941.37     .12       0
 6083.75     .07       0 9309.78     .12       0  9434.5    .041       0
 9457.41     .12       0 9539.58     .07       012382.62     .15       0
#XS Ineff= 1 ,-1
       0    4810      55
Permanent Ineff=
       F
#Block Obstruct= 4 ,-1
 6732.82 7673.28   51.81 8122.14 8528.24   50.08 8570.99 8955.73   50.39
 9532.8210815.27   51.81
Bank Sta=9399.77,9468.54
XS Rating Curve= 0
Exp/Cntr=.3,.1

Type RM Length L Ch R = 1 ,213290.6,521.6,555.05,461.91
XS GIS Cut Line= 6
     3125683.986    13787868.247     3125938.884     13778822.09
     3125962.459    13778785.886     3125979.298    13778749.682
     3126019.712    13778682.326     3126139.745    13774144.304
#Sta/Elev= 30
       0   51.88 4658.48   49.21 4748.07   51.98 4765.39   68.56 4801.86   54.75
 5002.21    51.8 5520.62   51.41 5565.42   44.11 6554.84   50.86 6711.83    51.3
 6757.56   62.01 6935.97   42.97 7552.32   42.97 7691.41   62.01 7724.03    50.8
 7803.41   49.31 8674.74   48.36 8897.34   50.06 9013.73    48.3 9079.56   56.93
 9119.29   48.55 9133.54   42.07 9156.26   37.49 9164.71    42.1 9186.69   49.94
 9256.22   50.81  9389.3    42.410508.27    40.210638.42   52.2813751.04   54.56
#Mann= 9 ,-1 , 0
       0     .07       0 5002.21     .15       0 6554.84     .07       0
 8674.74     .12       0 8897.34     .07       0 9013.73     .12       0
 9133.54    .041       0 9164.71     .12       0 9256.22     .07       0
#XS Ineff= 1 ,-1
       0    4750    54.5
Permanent Ineff=
       F
#Block Obstruct= 6 ,-1
 -136.38 1335.79   52.17  5514.5 5920.61   50.12 6775.57 7694.66   50.39
 8864.29  9054.5   50.77 9276.34 10708.4   51.2210652.2513786.88   52.18
Bank Sta=9119.29,9186.69
XS Rating Curve= 0
Exp/Cntr=.5,.3

Type RM Length L Ch R = 1 ,212735.5,621.52,686.3,589.77
XS GIS Cut Line= 6
     3125785.869    13787873.907     3126367.752    13783230.791
     3126425.532    13779034.261     3126448.264     13778951.75
     3126452.474     13778925.65     3126657.766     13773908.84
#Sta/Elev= 30
       0   51.98 4541.45   48.97 4660.78   51.98 4715.43   68.56 4854.97   50.43
 4953.75   52.21 5727.18   51.05 5775.42   44.11 5980.66   51.62 6220.24   43.66
 6286.96   43.66 6310.21   51.59  6598.1   47.88 6671.76    51.3 6698.46   62.01
 6796.03   42.97 7290.39   42.97 7391.64   50.65 7401.54   58.66 7447.44    49.1
  8784.5   48.97 8828.35   56.38 8869.37   48.08 8885.78   36.82 8900.93   38.24
    8906   39.37 8947.97   48.12 9002.42    56.3 9299.46   51.53 14009.4   53.41
#Mann= 7 ,-1 , 0
       0     .07       0 4953.75     .15       0  6598.1     .07       0
  8784.5     .12       0 8900.93    .041       0    8906     .12       0
 9299.46     .07       0
#XS Ineff= 3 ,-1
       0    4710    54.5    4710 7868.38    51.2 10369.2 14009.4    52.2
Permanent Ineff=
       F       F       F
#Block Obstruct= 6 ,-1
 -124.36 1346.85   52.07 5667.18 6326.72   50.58 6693.13 7425.95   50.03
 9965.61 10406.7   51.9610384.6410502.26   51.9510495.4514221.31   51.95
Bank Sta=8869.37,8947.97
XS Rating Curve= 0
Exp/Cntr=.5,.3

Type RM Length L Ch R = 1 ,212049.2,531.28,771.55,599
XS GIS Cut Line= 6
     3125944.355    13787868.247     3126140.036    13785968.503
     3126990.996    13782233.684     3127061.204    13778795.147
     3127053.627    13778691.587     3127244.616    13773064.791
#Sta/Elev= 30
       0   51.91 4506.86   48.89 4738.92   74.07 4824.12   50.37 4913.07   51.08
 5353.78   52.21 5574.18   44.04 5595.15   50.68 6259.67   52.08 6289.99   43.66
 6671.75   50.91 6768.13   62.01 6776.46   53.53 6902.99   42.97 7243.91   42.97
 7288.27   46.34 7298.62   64.74 7330.39   64.74 7424.64   50.24 7471.27    58.3
 7482.16   49.89 7512.34    49.4 8960.26   48.72 9164.33   47.91 9205.57   35.98
 9218.76    41.2 9242.06   47.75 9289.39   53.65 9410.25   49.7814913.46   54.73
#Mann= 7 ,-1 , 0
       0     .07       0 4913.07     .15       0 6671.75     .07       0
 8960.26     .12       0 9205.57    .041       0 9218.76     .12       0
 9410.25     .07       0
#XS Ineff= 3 ,-1
       0    4690    54.5    4690  8590.3    51.110033.6314913.46   52.11
Permanent Ineff=
       F       F       F
#Block Obstruct= 5 ,-1
  -68.82 1338.07   51.99 5398.47  5691.6   50.03 6180.15    6400   49.76
 6766.41 7352.67   50.94 9643.51 15020.7   51.77
Bank Sta=9164.33,9242.06
XS Rating Curve= 0
Exp/Cntr=.5,.3

Type RM Length L Ch R = 1 ,211277.7,188.03,50.32,182.38
XS GIS Cut Line= 6
     3126252.089    13787853.052       3126296.9    13786049.401
       3127495.6    13781837.148     3127686.048    13777344.825
      3128055.74    13776000.489      3128226.32    13772173.649
#Sta/Elev= 30
       0   51.99 4837.62   50.45 6710.74   50.91 7065.56    51.3 7082.75   60.13
 7104.62   62.01 7204.07   59.78 7253.88   51.81 7422.33   50.97 8981.84    52.7
 9294.75   53.79 9360.26   42.07 9374.44   39.02  9445.5   49.54 9520.05   46.24
  9543.9   37.97 9561.72   40.74 9571.91   46.69 9638.23   50.47 9741.94   47.33
10836.68   51.83 12834.9   53.3112877.48   48.8212908.69   54.5312920.44   51.32
14967.61   54.1414974.04   50.3414991.23   54.1415193.43   55.27 15928.7   53.34
#Mann= 9 ,-1 , 0
       0     .07       0 4837.62     .15       0 6710.74     .07       0
 8981.84     .12       0 9360.26     .07       0  9543.9    .041       0
 9561.72     .07       0 9741.94     .12       010836.68     .07       0
#XS Ineff= 3 ,-1
       0    4540      54 9645.62 15928.7      52    4540    9441    50.6
Permanent Ineff=
       F       F       F
#Block Obstruct= 3 ,-1
  216.19 3417.06   51.44  9303.8 9440.76   52.2311068.3615310.98   51.64
Bank Sta=9520.05,9571.91
XS Rating Curve= 0
Exp/Cntr=.5,.3

Type RM Length L Ch R = 3 ,211237  ,,,
BEGIN DESCRIPTION:
Cullen Blvd.
END DESCRIPTION:
Bridge Culvert--1,0,-1,-1, 0
Deck Dist Width WeirC Skew NumUp NumDn MinLoCord MaxHiCord MaxSubmerge Is_Ogee
5,40,2.6,0, 57, 57, , , .95, 0, 0,0,,
       0     289     490     590    1273    1572    2079    2222    2878    2945
    3742    3875    4468    4791    5600    5922    6714    7823    8303    8816
    8940    9139    9337    9416    9430    9431    9440    9441    9482    9523
    9564    9605    9645    9646    9656    9657    9747    9848   10046   10052
   10329   10940   11187   11476   11848   12223   12300   12508   12730   12881
   13153   14215   14915   15337   15527   15625   15925
    53.1    52.8      53    52.8    52.3    52.8      52    52.3    53.1    52.4
      52    51.4    51.2    50.9    50.6    50.8    51.3    51.3    51.4    51.8
   52.53   52.47   52.61   53.25    53.3   55.98   56.43   56.43   56.69   56.81
    56.8   56.71    56.5    56.5   56.02      53   52.98   52.64   53.03      52
    52.1    52.9    53.2    52.8      53    53.7      54    54.4      54      54
      54    53.3      54    54.1      54      54      54
                                                                                
                                                                                
                                                           50.98   51.24   51.35
   51.31   51.23   51.01
                                                                                
                                                        
       0     312     513     613    1296    1595    2102    2245    2901    2968
    3765    3898    4491    4814    5623    5945    6737    7846    8326    8839
    8963    9162    9360    9439    9453    9454    9463    9464    9505    9546
    9587    9628    9668    9669    9679    9680    9770    9871   10069   10075
   10352   10963   11210   11499   11871   12246   12323   12531   12753   12904
   13176   14238   14938   15360   15550   15648   15948
    53.1    52.8      53    52.8    52.3    52.8      52    52.3    53.1    52.4
      52    51.4    51.2    50.9    50.6    50.8    51.3    51.3    51.4    51.8
   52.53   52.47   52.61   53.25    53.3   55.98   56.43   56.43   56.69   56.81
    56.8   56.71    56.5    56.5   56.02      53   52.98   52.64   53.03      52
    52.1    52.9    53.2    52.8      53    53.7      54    54.4      54      54
      54    53.3      54    54.1      54      54      54
                                                                                
                                                                                
                                                           50.98   51.24   51.35
   51.31   51.23   51.01
                                                                                
                                                        
Pier Skew, UpSta & Num, DnSta & Num=  ,9482, 2 ,9505, 2 , 0 , 0 , 0 ,,
    1.33    1.33
       0      52
    1.33    1.33
       0      52
Pier Skew, UpSta & Num, DnSta & Num=  ,9523, 2 ,9546, 2 , 0 , 0 , 0 ,,
    1.33    1.33
       0      52
    1.33    1.33
       0      52
Pier Skew, UpSta & Num, DnSta & Num=  ,9564, 2 ,9587, 2 , 0 , 0 , 0 ,,
    1.33    1.33
       0      52
    1.33    1.33
       0      52
Pier Skew, UpSta & Num, DnSta & Num=  ,9605, 2 ,9628, 2 , 0 , 0 , 0 ,,
    1.33    1.33
       0      52
    1.33    1.33
       0      52
Abutment Skew #Up #Dn= , 2 , 2
    9440    9476
      50      45
 9464.01    9500
      50      45
BR Coef=-1 , 1 , 1 ,1.25, 0 ,,,.8,-1,2,0,
WSPro=,,,, 1 ,,,, 0 ,,,, 0 ,,,,-1 ,-1 ,-1 , 0 , 0 , 0 , 0 , 0
BC Design=,, 0 ,, 0 ,,,,,,
BC HTab HWMax=62.01

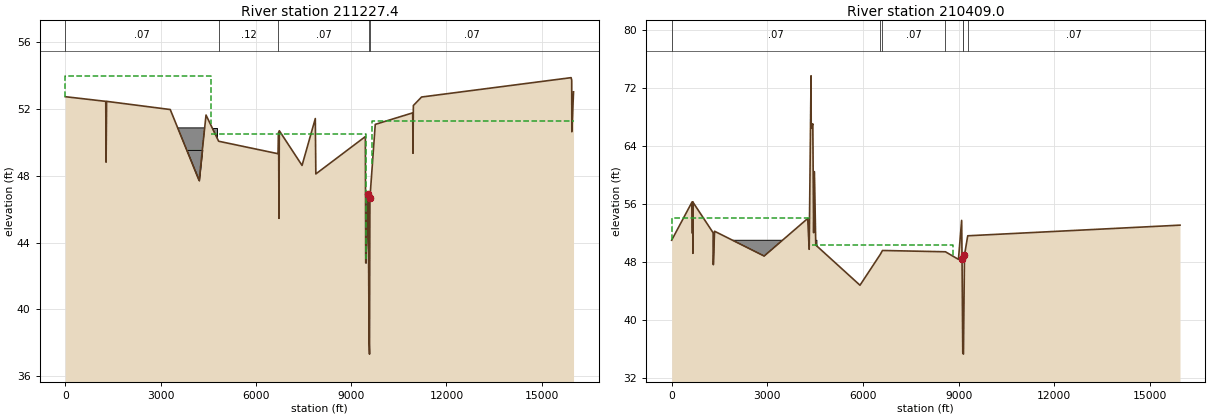
Type RM Length L Ch R = 1 ,211227.4,494.98,818.38,642.46
XS GIS Cut Line= 6
     3126408.122    13787892.986     3126565.768    13785601.289
     3127630.034    13782173.232     3127781.307    13778407.192
     3128246.188    13775989.286     3128447.838    13772146.726
#Sta/Elev= 30
       0   52.75 1276.43   52.47 1286.76   48.83 1303.23   52.47 3306.41   51.98
 4215.35   47.72 4432.81   51.65  4829.5   50.08 6704.46   49.33 6717.71   50.61
 6728.73   45.46 6739.34   50.71 7455.62   48.63 7873.03   51.44 7889.37   48.12
 9448.43   50.36 9459.25   42.79 9537.58   46.91 9566.94   37.97 9579.05   37.32
 9592.56   46.69 9759.75   51.0910938.34   51.7810947.59   49.36 10959.3   52.22
11217.87   52.7315924.63   53.8915943.55   53.7415948.06   50.65 16001.1   53.04
#Mann= 5 ,-1 , 0
       0     .07       0  4829.5     .12       0 6704.46     .07       0
 9566.94    .041       0 9592.56     .07       0
#XS Ineff= 3 ,-1
       0    4575      54  9669.3 16001.1   51.32    4575 9464.01    50.5
Permanent Ineff=
       F       F       F
#Block Obstruct= 4 ,-1
  623.91 4776.99   50.88 3501.71  4525.6   49.56  9449.3 9537.74   46.82
 9841.8416407.32   51.06
Bank Sta=9537.58,9592.56
XS Rating Curve= 0
Exp/Cntr=.5,.3

Type RM Length L Ch R = 1 ,210409.0,424.64,741.33,661.4
XS GIS Cut Line= 6
     3127331.103    13787930.509     3128461.368    13779002.267
     3128477.365    13778930.701     3128483.258    13778875.133
     3128500.097    13778789.254     3128541.494    13772066.744
#Sta/Elev= 30
       0   50.97  639.03   56.25  650.86   51.92  660.16   56.25     665   49.16
  665.89   56.23 1299.69      52 1306.48   47.59  1344.6   52.21 2899.51   48.78
 4265.48   53.97 4312.04   49.71 4370.39   73.68  4375.3   66.46 4425.27   67.05
 4451.29   52.01 4475.67   60.44 4518.05    50.3 5904.89   44.75 6538.93   48.99
 6610.45   49.55 8584.79   49.37 8992.19   48.32 9092.53   53.71 9104.61   48.32
 9127.79    35.4 9149.38   35.23 9181.24    48.9 9283.03   51.58 15938.9   53.05
#Mann= 7 ,-1 , 0
       0     .07       0 6538.93     .12       0 6610.45     .07       0
 8584.79     .12       0 9127.79    .041       0 9149.38     .12       0
 9283.03     .07       0
#XS Ineff= 3 ,-1
       0    4400      54    4400 8827.44    50.3 9515.68 15938.9   51.16
Permanent Ineff=
       F       F       F
#Block Obstruct= 2 ,-1
 -220.28 4554.56   50.96 9388.4315940.69   50.94
Bank Sta=9104.61,9181.24
XS Rating Curve= 0
Exp/Cntr=.5,.3