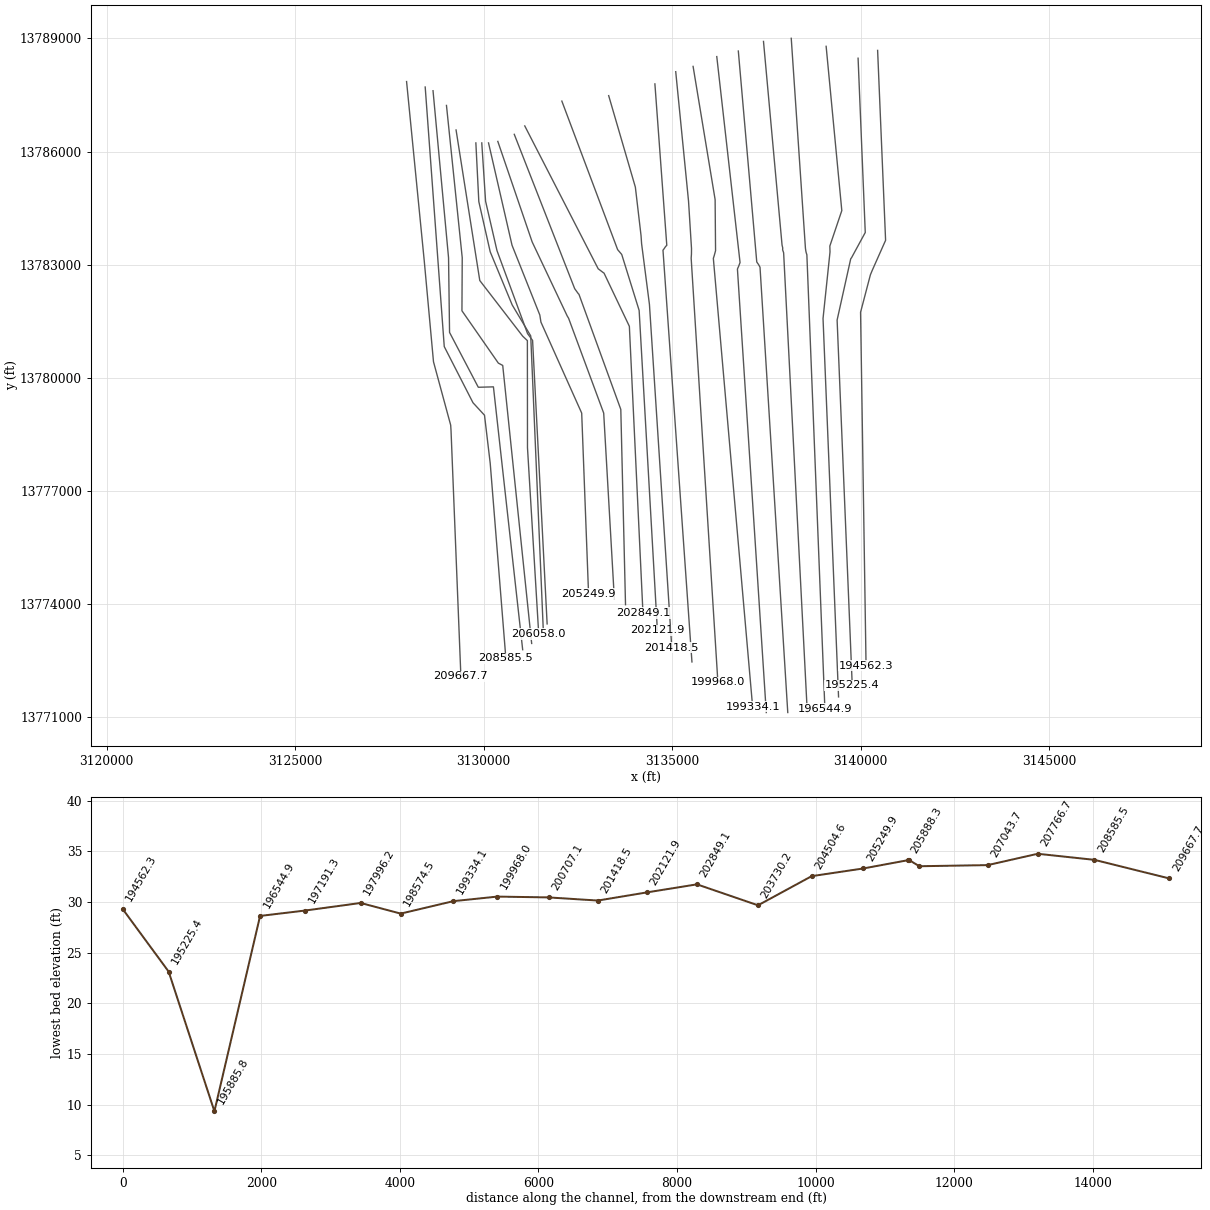
HEC-RAS study A100-00-00.prj: A100-00-00

--- A100-00-00.g01 (geometry) --- (continued)

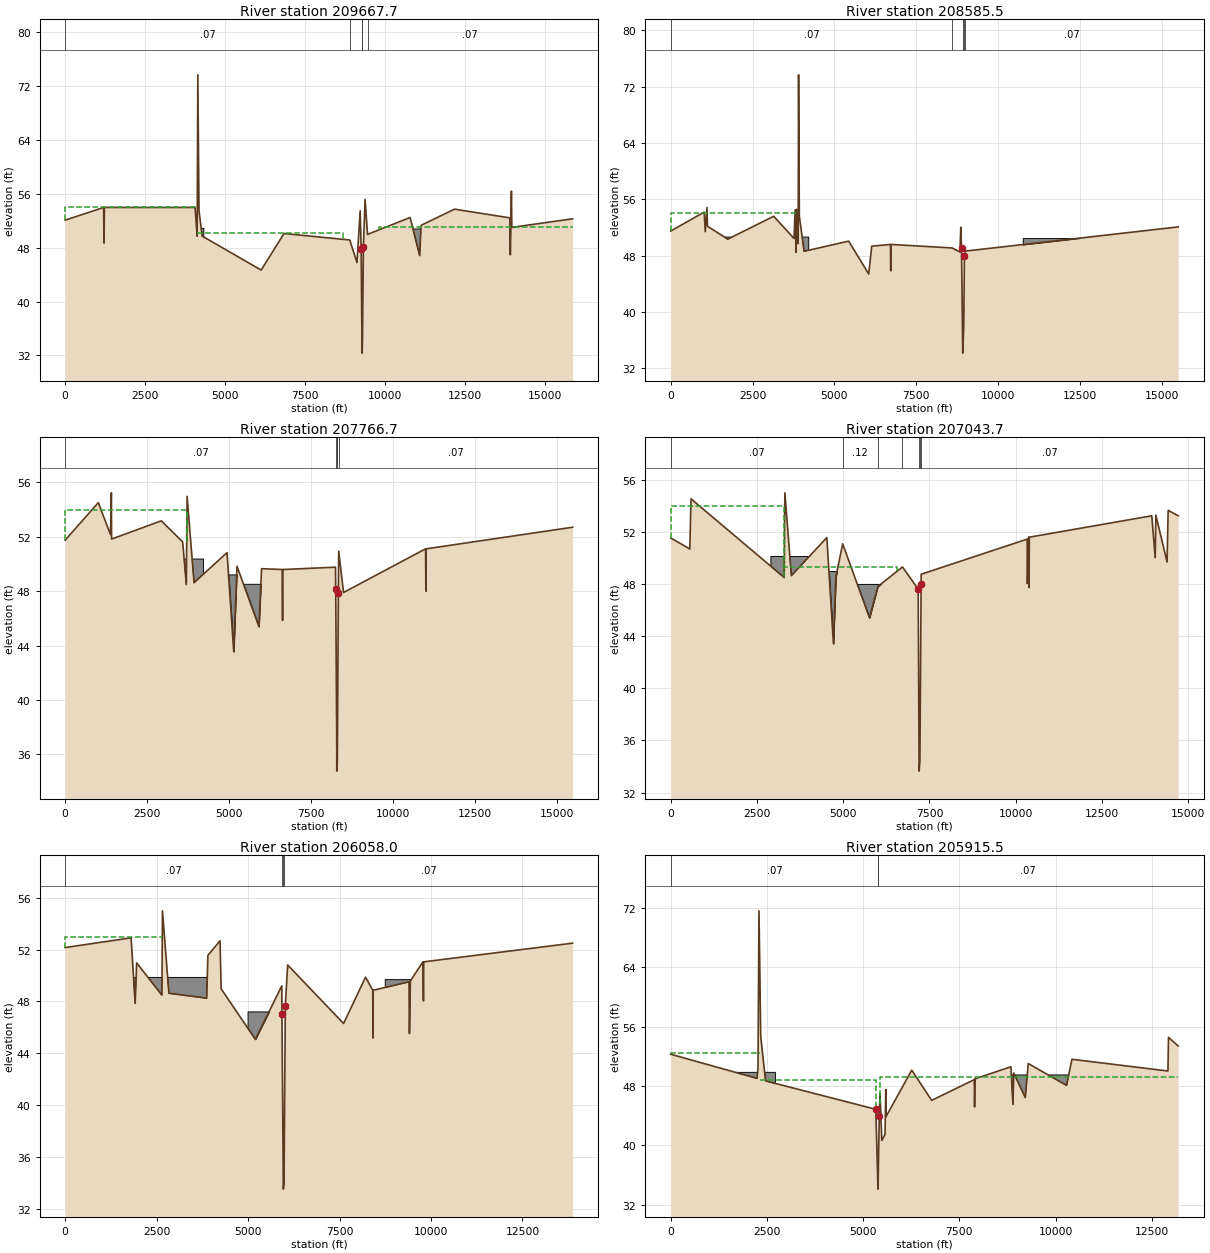
Type RM Length L Ch R = 1 ,209667.7,366.63,1082.23,1017.23
XS GIS Cut Line= 6
     3127953.725    13787856.926     3128422.171    13783105.461
     3128667.994    13780422.227     3129123.982    13778741.262
     3129133.244    13778597.289      3129394.78    13772079.644
#Sta/Elev= 30
       0   52.09  1202.7   53.97 1215.51   48.69 1228.44   53.97 4063.39   53.97
 4129.54   49.71 4151.24   73.68 4186.85    53.5 4287.34   49.72 6132.62   44.67
 6847.85    50.1 8905.55   49.14 9130.71   45.78 9230.64   53.48 9262.55   47.78
  9278.3   37.95 9293.18   32.33 9303.17   34.71    9332   48.17 9384.08   55.16
 9461.13   49.9710792.97   52.4811092.39   46.8111136.32   51.3212182.33   53.72
13913.44   52.4313928.93   46.9513962.79    56.413975.81   51.0115878.95   52.29
#Mann= 5 ,-1 , 0
       0     .07       0 8905.55     .12       0  9278.3    .041       0
 9303.17     .12       0 9461.13     .07       0
#XS Ineff= 3 ,-1
       0    4140      54    4140 8708.49    50.2 9822.7215878.95      51
Permanent Ineff=
       F       F       F
#Block Obstruct= 2 ,-1
  823.56 4339.65   50.8710750.9516044.09   50.78
Bank Sta=9262.55,9332
XS Rating Curve= 0
Exp/Cntr=.5,.3

Type RM Length L Ch R = 1 ,208585.5,336.32,818.74,339.52
XS GIS Cut Line= 6
     3128447.934     13787711.86     3128953.548    13780824.858
     3129716.057    13779335.033     3130021.501    13779003.951
     3130173.053    13777726.902      3130587.66    13772560.262
#Sta/Elev= 30
       0    51.5 1022.76   54.19  1055.7   51.41 1107.84   54.84 1122.99   52.19
 1743.25   50.35 3145.74    53.6 3767.79   50.45 3803.78   54.52 3829.49   48.49
 3845.09   54.59 3893.94   49.71 3906.43   73.68  3930.4   53.62 4075.42   48.63
 5438.57   50.07 6050.58    45.4 6141.15   49.35 6714.93    49.6 6722.91   45.85
 6730.79    49.6 8603.44    49.1 8838.03   48.52 8862.94   52.06 8885.19   49.04
 8923.12   34.17 8953.43   37.95 8974.04   47.93 8996.34   48.6515505.78   52.09
#Mann= 5 ,-1 , 0
       0     .07       0 8603.44     .12       0 8923.12    .041       0
 8953.43     .12       0 8996.34     .07       0
#XS Ineff= 1 ,-1
       0    3900      54
Permanent Ineff=
       F
#Block Obstruct= 2 ,-1
   29.88 4217.12   50.6510756.8715052.41    50.5
Bank Sta=8885.19,8974.04
XS Rating Curve= 0
Exp/Cntr=.3,.1

Type RM Length L Ch R = 1 ,207766.7,705.1,723.05,310.86
XS GIS Cut Line= 6
      3128655.59    13787613.538     3129067.409     13783181.82
     3129094.319    13781200.246     3129856.827    13779745.615
     3130258.089    13779756.655      3131034.16    13772783.511
#Sta/Elev= 30
       0   51.76 1012.21   54.52 1382.17   52.17 1410.55   55.24 1417.51   51.84
 2934.74   53.18 3587.54   51.63 3699.19   48.49 3722.27   54.98 3934.94   48.63
 4941.28   50.84 5145.98   43.56 5245.99   49.84  5914.7    45.4 5996.06   49.66
 6627.88    49.6 6636.65   45.85 6643.59    49.6 8253.05   49.77 8259.25   48.18
 8289.67   37.43 8292.19   34.77 8308.99   35.55 8340.42   47.85 8350.83   50.95
 8498.53   47.9111002.31   51.1211012.26   48.0311019.33   51.1215492.76   52.71
#Mann= 5 ,-1 , 0
       0     .07       0 8253.05     .12       0 8289.67    .041       0
 8308.99     .12       0 8350.83     .07       0
#XS Ineff= 1 ,-1
       0    3710      54
Permanent Ineff=
       F
#Block Obstruct= 4 ,-1
 3412.81 4221.47   50.37 4909.92 5276.34   49.24 5315.13 6025.03   48.55
 10887.415526.98   50.32
Bank Sta=8259.25,8340.42
XS Rating Curve= 0
Exp/Cntr=.5,.3

Type RM Length L Ch R = 1 ,207043.7,739.21,985.67,506.59
XS GIS Cut Line= 6
     3129012.182    13787222.984     3129430.513     13783181.82
     3129422.784     13781775.06     3130388.592    13780386.433
     3130504.781    13780324.971     3131272.613    13772948.804
#Sta/Elev= 30
       0   51.52  553.59   50.68   588.4   54.52 3289.67   48.49 3309.48   54.98
 3497.15   48.63 4525.73   51.55 4716.75   43.42 4787.03   48.53 4985.19   51.07
 5761.84    45.4  6001.7   47.79 6718.22    49.3 7173.91    47.6 7200.43   33.73
 7200.67   33.65 7223.55    34.4 7259.03      48 7260.14   48.7410332.59   51.43
10339.28   48.0310375.36   51.5810386.61   47.7210396.12   51.5813944.81   53.22
14044.77   50.0214062.58   53.2714388.02   49.6914419.95   53.6414710.64   53.22
#Mann= 7 ,-1 , 0
       0     .07       0 4985.19     .12       0  6001.7     .07       0
 6718.22     .12       0 7200.43    .041       0 7223.55     .12       0
 7260.14     .07       0
#XS Ineff= 3 ,-1
       0    3280      54 8350.6414710.64    49.6    3280  6553.3   49.32
Permanent Ineff=
       F       F       F
#Block Obstruct= 4 ,-1
 2903.45 4541.49    50.1 4396.95 4958.78   48.98 5042.09 6134.24      48
 9342.3814963.41   50.13
Bank Sta=7173.91,7259.03
XS Rating Curve= 0
Exp/Cntr=.5,.3

Type RM Length L Ch R = 1 ,206058.0,517.72,142.45,229.46
XS GIS Cut Line= 6
     3129266.891    13786572.061     3129895.945    13782578.002
      3131035.21    13781100.407     3131158.886     13780983.24
     3131161.731    13778141.509      3131459.95    13773199.766
#Sta/Elev= 30
       0   52.15 1802.62    52.9  1913.1   47.85 1954.47   50.97 2643.01   48.49
 2659.47   54.98 2835.63   48.63 3868.14   48.25 3901.55   51.55 4233.07   52.67
 4264.39   48.97 5198.67   45.08 5921.82    49.2 5925.86   47.01 5963.68   33.54
 5982.64   33.97 6017.43   47.62 6081.56   50.81  7610.4    46.3 8210.88   49.87
 8407.81   48.86 8414.23   45.18 8420.18   48.86 9402.88   49.51 9410.45   45.53
 9436.94   49.58 9779.24   51.05 9793.08   48.05 9801.79   51.0513871.92   52.49
#Mann= 4 ,-1 , 0
       0     .07       0 5921.82     .12       0 5963.68    .041       0
 5982.64     .07       0
#XS Ineff= 3 ,-1
       0    2660      53    2660 5889.88   48.88 6168.2913871.92   49.27
Permanent Ineff=
       F       F       F
#Block Obstruct= 3 ,-1
 1457.67 4210.41   49.85 4985.21  5797.5   47.23 8748.88 11819.8   49.68
Bank Sta=5925.86,6017.43
XS Rating Curve= 0
Exp/Cntr=.5,.3

Type RM Length L Ch R = 1 ,205915.5,164.47,27.26,138.54
XS GIS Cut Line= 6
     3129792.174    13786228.646     3129870.594    13784671.457
     3130173.069    13783338.323     3130755.615    13781930.505
     3131247.821    13781107.811     3131578.381    13773362.634
#Sta/Elev= 30
       0   52.28 2242.57   49.03 2268.23   50.32 2294.22   71.57 2339.59   54.64
 2465.39   48.69 5329.28   44.87 5387.26   34.13 5393.79   36.01  5420.1   44.03
 5439.66   46.96  5486.1   40.68  5569.1   41.48 5589.35   47.54 5594.84   43.87
 6263.82   50.14 6781.74   46.07  7889.9   48.86 7896.63   45.18 7908.11   48.97
 8841.61   50.59 8893.98   45.53 8915.02   49.75 9214.48   46.45 9292.52   51.03
10287.84   48.0810426.67    51.612922.34   50.02   12936   54.5513188.64   53.39
#Mann= 3 ,-1 , 0
       0     .07       0 5387.26    .041       0 5393.79     .07       0
#XS Ineff= 3 ,-1
       0    2320    52.5 5430.8213188.64    49.2    2320 5329.66    48.8
Permanent Ineff=
       F       F       F
#Block Obstruct= 2 ,-1
  943.07  2720.6   49.84 8677.1511805.58   49.49
Bank Sta=5329.28,5420.1
XS Rating Curve= 0
Exp/Cntr=.5,.3

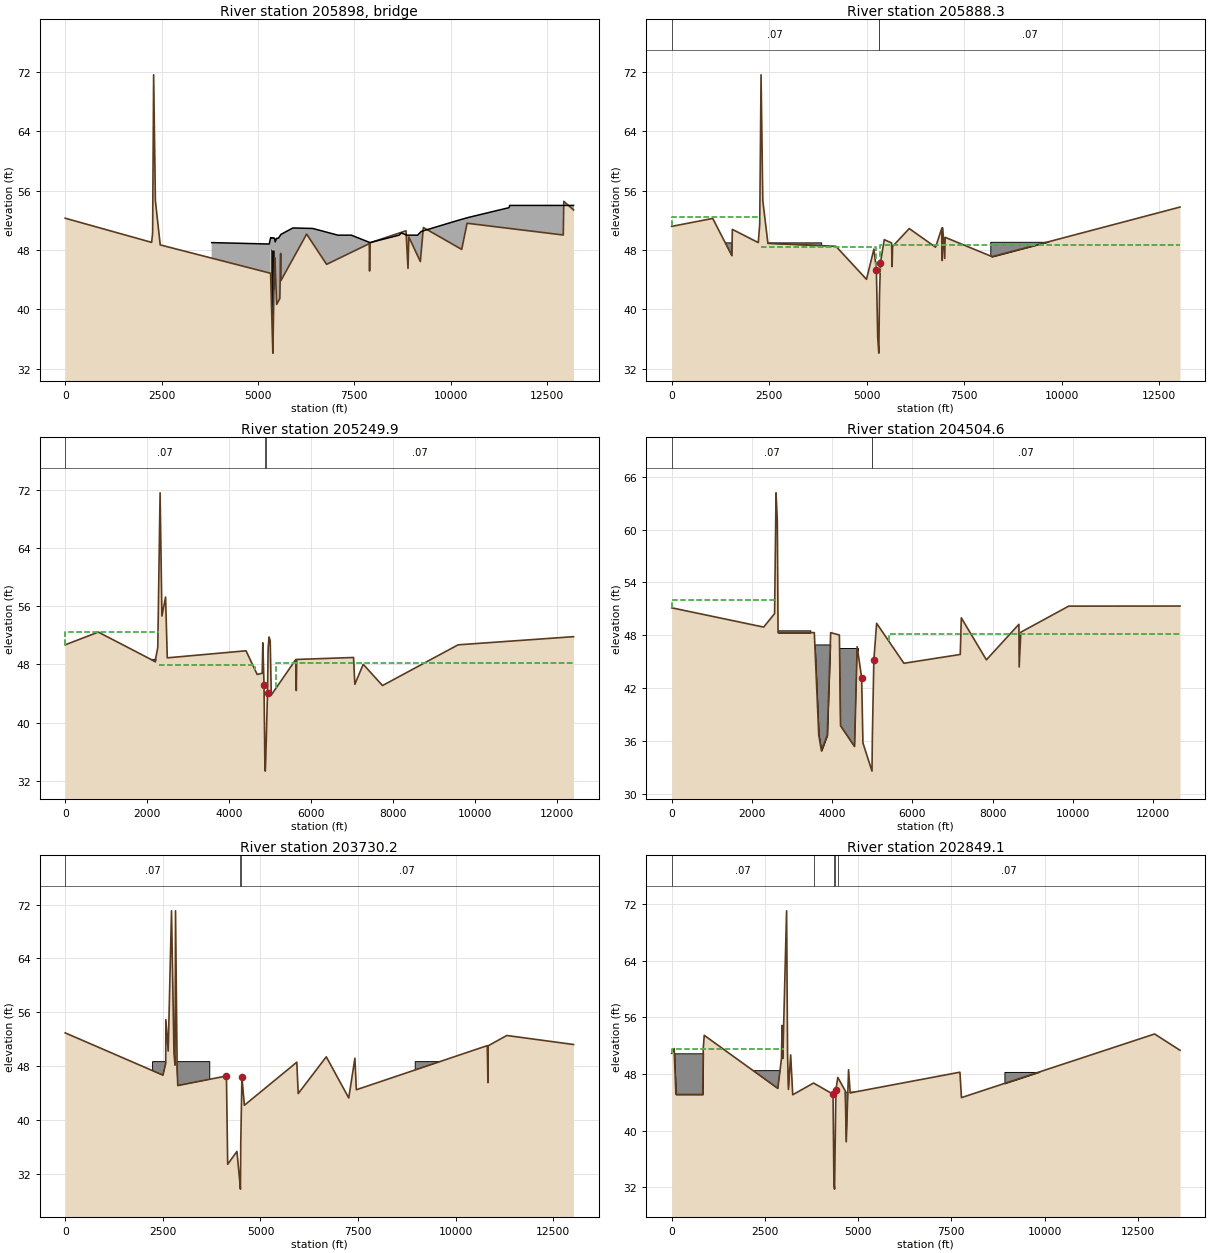
Type RM Length L Ch R = 3 ,205898  ,,,
BEGIN DESCRIPTION:
Stone Rd.
END DESCRIPTION:
Bridge Culvert--1,0,-1,-1, 0
Deck Dist Width WeirC Skew NumUp NumDn MinLoCord MaxHiCord MaxSubmerge Is_Ogee
5,18,2.6,0, 33, 33, , , .95, 0, 0,0,,
    3800    5293    5329    5330    5344    5359    5373    5387    5402    5416
    5430    5431    5449    5481    5531    5582    5595    5908    6424    7074
    7280    7423    7908    8660    8726    8861    9142    9237   10197   10473
   11514   11534   13188
      49   48.81   49.66   49.66   49.64   49.59   49.65   49.63   49.59   49.63
   49.55   49.55   49.09   49.56   49.59   49.98    50.1   50.97    50.9      50
      50      50      49      50    50.3      50      50    50.5      52    52.4
    53.7      54      54
                           47.97   48.08   48.02   47.99   48.07   47.99   48.07
   48.05
                                                                                
                        
    3800    5207    5243    5244    5258    5273    5287    5301    5316    5330
    5344    5345    5363    5395    5445    5496    5509    5822    6372    7022
    7228    7371    7856    8608    8674    8809    9090    9185   10145   10421
   11462   11482   13136
      49   48.81   49.66   49.66   49.64   49.59   49.65   49.63   49.59   49.63
   49.55   49.55   49.09   49.56   49.59   49.98    50.1   50.97    50.9      50
      50      50      49      50    50.3      50      50    50.5      52    52.4
    53.7      54      54
                           47.97   48.08   48.02   47.99   48.07   47.99   48.07
   48.05
                                                                                
                        
Pier Skew, UpSta & Num, DnSta & Num=  ,5344, 2 ,5258, 2 , 0 , 0 , 0 ,,
       1       1
       0      49
       1       1
       0      49
Pier Skew, UpSta & Num, DnSta & Num=  ,5359, 2 ,5273, 2 , 0 , 0 , 0 ,,
       1       1
       0      49
       1       1
       0      49
Pier Skew, UpSta & Num, DnSta & Num=  ,5373, 2 ,5287, 2 , 0 , 0 , 0 ,,
       1       1
       0      49
       1       1
       0      49
Pier Skew, UpSta & Num, DnSta & Num=  ,5387, 2 ,5301, 2 , 0 , 0 , 0 ,,
       1       1
       0      49
       1       1
       0      49
Pier Skew, UpSta & Num, DnSta & Num=  ,5402, 2 ,5316, 2 , 0 , 0 , 0 ,,
       1       1
       0      49
       1       1
       0      49
Pier Skew, UpSta & Num, DnSta & Num=  ,5416, 2 ,5330, 2 , 0 , 0 , 0 ,,
       1       1
       0      49
       1       1
       0      49
BR Coef=-1 , 1 , 1 ,1.05, 0 ,,,.8,-1,1.2,0,
WSPro=,,,, 1 ,,,, 0 ,,,, 0 ,,,,-1 ,-1 ,-1 , 0 , 0 , 0 , 0 , 0
BC Design=,, 0 ,, 0 ,,,,,,
BC HTab HWMax=71.57

Type RM Length L Ch R = 1 ,205888.3,435.18,638.36,1310.06
XS GIS Cut Line= 6
     3129949.013    13786228.646     3130049.838     13784682.66
     3130352.314    13783371.932     3131163.035    13781170.704
     3131297.119    13780988.301     3131683.059    13773467.311
#Sta/Elev= 30
       0   51.18 1052.36   52.25 1543.56   47.24  1555.2   50.78 2219.94      49
 2257.17    51.5 2291.21   71.57 2335.85   54.64 2467.33   48.89 4211.32    48.5
 4993.72   44.06 5184.89   48.13  5247.4   45.31 5281.89   36.25 5309.99   34.13
 5326.66   41.82 5352.42   46.32 5449.56    49.4 5636.45   48.95 5651.05   45.78
 5662.18   48.48 6090.24   50.89 6763.94   48.38 6927.29   50.97 6935.14   46.59
 6948.02   50.97 6999.65   46.87 7009.16   49.71 8214.41   47.1113030.26   53.78
#Mann= 3 ,-1 , 0
       0     .07       0 5309.99    .041       0 5326.66     .07       0
#XS Ineff= 3 ,-1
       0    2280    52.5    2280 5243.51   48.37 5344.6213030.26   48.61
Permanent Ineff=
       F       F       F
#Block Obstruct= 2 ,-1
 1078.77 3845.36   48.96 8167.69 9913.05   49.11
Bank Sta=5247.4,5352.42
XS Rating Curve= 0
Exp/Cntr=.5,.3

Type RM Length L Ch R = 1 ,205249.9,546.17,745.3,558.75
XS GIS Cut Line= 6
     3130128.258    13786228.646     3130751.509    13783514.117
     3131489.021    13781661.988     3131518.489    13781474.233
     3132599.889    13779060.465     3132781.757    13774273.408
#Sta/Elev= 30
       0   50.68  807.74   52.43 2193.25   48.38 2258.88   50.32 2315.55   71.57
 2360.16   54.64 2449.37   57.25 2490.96   48.89  4412.6   49.86 4684.67   46.61
 4806.97   46.77 4822.54   50.95 4851.74   45.17 4873.57   33.67 4882.41   33.32
 4893.68   34.88 4936.93    44.1 4952.21   50.17 4974.47   51.76  5002.6   51.23
 5028.83   43.78  5627.1   48.67 5638.74    44.4 5649.65   48.67 7036.77   48.94
 7067.95   45.25 7272.46      48 7743.17   45.08  9588.1   50.6812404.73    51.8
#Mann= 3 ,-1 , 0
       0     .07       0 4882.41    .041       0 4893.68     .07       0
#XS Ineff= 3 ,-1
       0    2300    52.5 5146.4712404.73   48.14    2300 4631.68   47.91
Permanent Ineff=
       F       F       F
#Block Obstruct= 1 ,-1
 1341.65 3931.73   48.75
Bank Sta=4851.74,4936.93
XS Rating Curve= 0
Exp/Cntr=.5,.3

Type RM Length L Ch R = 1 ,204504.6,580.96,774.44,559.1
XS GIS Cut Line= 6
     3130374.585    13786268.208     3131285.213    13783603.381
     3132216.466    13781635.888     3132251.828    13781577.793
     3133183.608    13779060.465     3133465.868    13774141.531
#Sta/Elev= 30
       0   51.11 2293.27   48.92 2565.79   50.45 2602.05   64.17 2634.18   60.92
 2652.58   48.28 3556.09   48.29 3667.18   36.66 3733.96   34.87 3878.57   36.64
  3964.3   48.29 4181.33   48.02 4209.63   37.72 4559.88   35.35 4624.03   46.69
 4735.96   43.18 4768.35   35.76 4994.27   32.56 5002.78   36.32  5040.2   45.17
 5109.66   49.35 5789.67   44.81 7194.17   45.81 7220.85   49.97 7845.65    45.2
 8656.81   49.24 8663.48   44.39 8705.07   48.34 9898.28    51.312672.73   51.31
#Mann= 3 ,-1 , 0
       0     .07       0 4994.27    .041       0 5002.78     .07       0
#XS Ineff= 3 ,-1
       0    2590      52 5415.5612672.73   48.09    2590 4113.06   47.86
Permanent Ineff=
       F       F       F
#Block Obstruct= 3 ,-1
 1574.44 3457.87   48.55 3334.35 3996.95   46.95 4125.19 4638.17   46.49
Bank Sta=4735.96,5040.2
XS Rating Curve= 0
Exp/Cntr=.5,.3

Type RM Length L Ch R = 1 ,203730.2,664.31,881.11,1984.42
XS GIS Cut Line= 6
     3130811.198    13786456.376     3132414.324    13782360.807
     3132508.623    13782230.304     3132527.145    13782212.624
     3133637.612    13779157.751     3133762.591    13773976.685
#Sta/Elev= 30
       0   52.92 2503.55   46.63 2574.45   48.41 2577.73   54.88 2637.41   50.21
 2722.52   71.07 2785.85   49.88 2812.36   48.13 2825.05   71.07 2866.72    47.5
 2883.13   45.08 4129.19   46.51 4161.35   33.37 4398.15   35.29  4484.8   29.92
 4487.27   29.68    4496   36.44 4525.62   46.34  4588.3   42.15 5931.77   48.56
 5967.41   43.89 6686.66   49.36 7261.69   43.24 7419.46   49.15 7456.37   44.46
10809.07   51.0210826.41   45.5310832.95      5111309.21   52.5313018.56   51.19
#Mann= 3 ,-1 , 0
       0     .07       0  4484.8    .041       0    4496     .07       0
#XS Ineff= 2 , 0
       0 2700.18    51.5               0
Permanent Ineff=
       F       F
#Block Obstruct= 2 ,-1
 2238.52 3702.46   48.64 8964.3811829.76   48.64
Bank Sta=4129.19,4525.62
XS Rating Curve= 0
Exp/Cntr=.3,.1

Type RM Length L Ch R = 1 ,202849.1,824.01,727.21,444.4
XS GIS Cut Line= 6
     3131089.475    13786679.605     3133037.367    13782889.552
     3133172.921    13782786.834     3133192.286    13782775.046
     3133864.614    13781362.913     3134225.252    13773758.307
#Sta/Elev= 30
       0   50.94   66.31   51.61   113.4   45.13  832.32   45.13  846.74   51.61
  872.98   53.48 2846.93   45.98 2944.39   50.21 2959.81   54.88 2980.26   50.21
 3081.62   71.07 3108.28   50.72 3131.43   45.84 3191.45   50.72 3246.09   45.08
 3804.79   46.74 4327.33   45.16 4351.15    32.2  4361.7   32.16 4367.78   31.75
 4404.24   45.78  4454.9   47.53 4654.66   45.64 4681.65   38.44 4743.36   48.62
 4786.54   45.35 7729.61   48.27 7771.33   44.68 12950.1   53.67 13631.4   51.37
#Mann= 5 ,-1 , 0
       0     .07       0 3804.79     .12       0  4361.7    .041       0
 4367.78     .12       0  4454.9     .07       0
#XS Ineff= 2 , 0
       0 3013.74    51.5               0
Permanent Ineff=
       F       F
#Block Obstruct= 4 ,-1
 -213.74  919.08   50.94 1991.82 3206.42   48.49 4552.67 4894.66   45.45
 8923.3811847.29   48.31
Bank Sta=4327.33,4404.24
XS Rating Curve= 0
Exp/Cntr=.3,.1

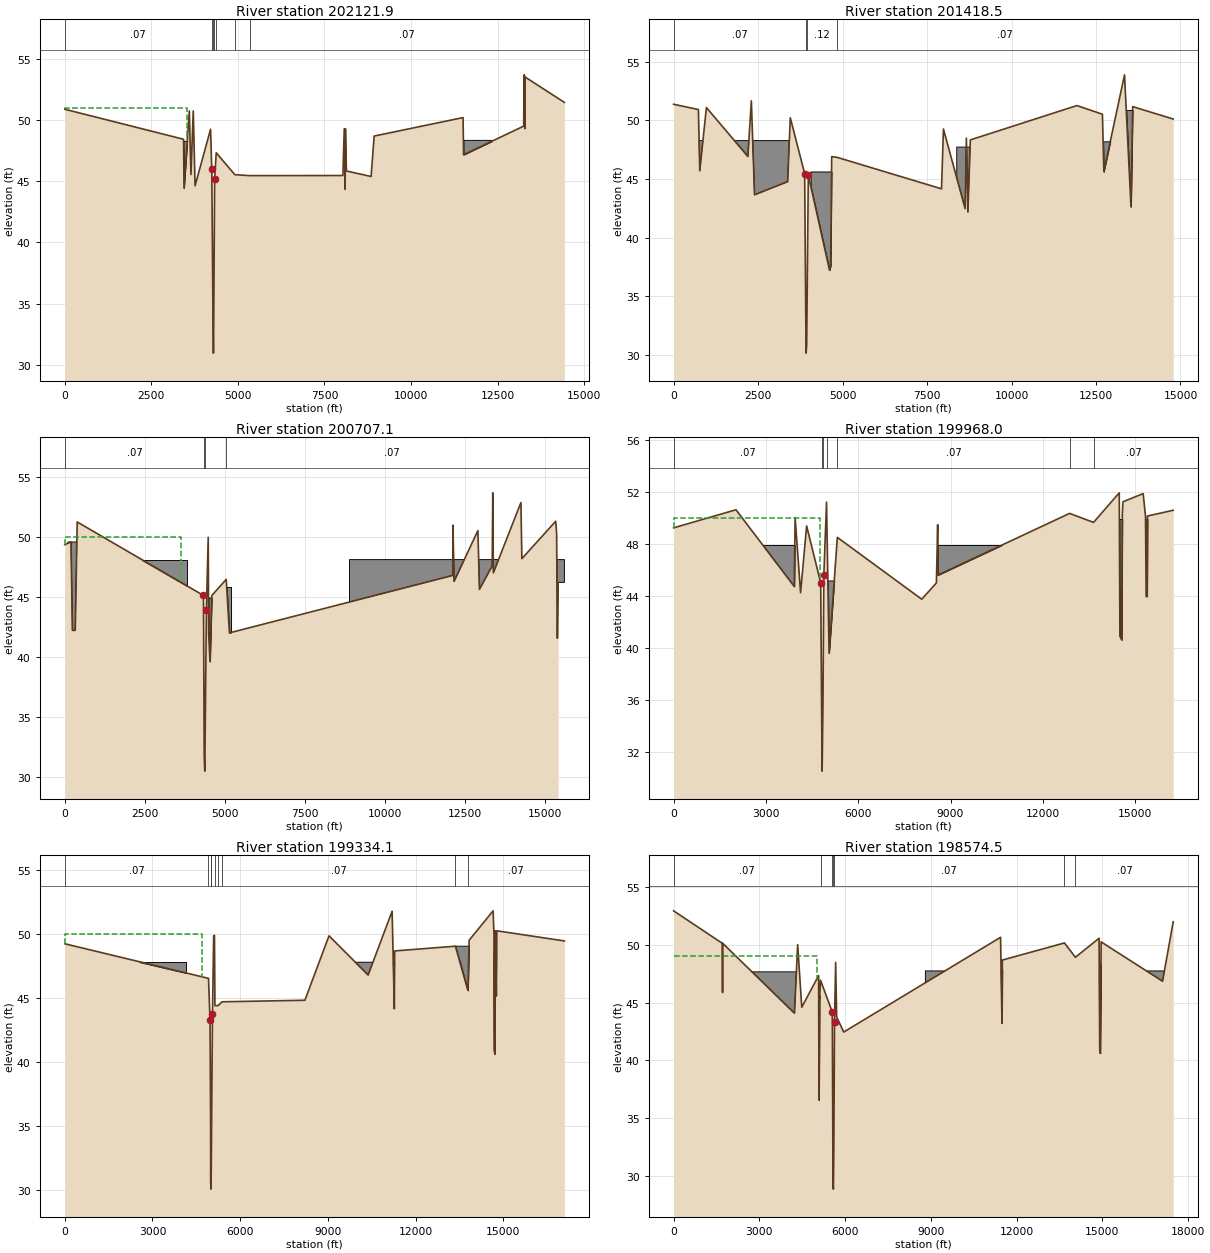
Type RM Length L Ch R = 1 ,202121.9,982.29,703.37,317.89
XS GIS Cut Line= 6
     3132073.587    13787337.784     3133553.483    13783397.248
     3133653.675    13783279.375      3133664.62    13783261.694
     3134124.045    13781784.489      3134607.57    13773299.526
#Sta/Elev= 30
       0   50.86 3431.54   48.41 3443.53   44.42 3597.25   50.72 3644.87   45.53
  3710.8   50.72 3763.26   44.61 4211.41   49.23 4245.45   45.95 4283.15   33.15
 4292.46   30.95 4296.93   31.26 4329.11   45.15 4374.06   47.31 4912.43   45.52
 5339.89   45.44 8033.21   45.45 8072.62   49.26    8098   44.33 8106.33   49.26
 8134.94   45.82 8847.08   45.37  8936.1   48.6711504.23   50.1811518.62   47.15
13254.34   49.4813271.32   53.6713289.38   49.2813295.78   53.4914430.58   51.42
#Mann= 7 ,-1 , 0
       0     .07       0 4245.45     .12       0 4283.15    .041       0
 4296.93     .12       0 4374.06     .07       0 4912.43     .12       0
 5339.89     .07       0
#XS Ineff= 2 , 0
       0 3541.98      51               0
Permanent Ineff=
       F       F
#Block Obstruct= 3 ,-1
  349.37 3563.36   48.28 4823.66 5515.36   45.41 9396.8612327.07   48.36
Bank Sta=4245.45,4329.11
XS Rating Curve= 0
Exp/Cntr=.3,.1

Type RM Length L Ch R = 1 ,201418.5,725.64,711.45,474.87
XS GIS Cut Line= 6
     3133315.778    13787483.069     3134023.775    13785055.649
     3134174.842    13783766.022     3134189.155    13783555.534
     3134397.215    13781943.647     3134989.887    13772840.745
#Sta/Elev= 30
       0   51.37  734.23   50.92  774.13    45.7  970.81   51.09 2198.14   46.92
 2300.86   51.66  2395.4   43.65 3374.71   44.77 3453.25   50.22 3878.57   45.46
 3919.49   30.15 3938.67    30.8 3986.27   45.33 4613.44   37.23 4647.63    37.6
 4678.67   46.91  4844.1   46.84  7928.7   44.16 7985.53   49.26 8628.12   42.47
  8664.4   48.48 8708.66   42.19  8781.3   48.33 11935.1   51.2612690.69   50.52
12731.96   45.6213344.37   53.8813535.61   42.6313585.72   51.1714785.49   50.11
#Mann= 4 ,-1 , 0
       0     .07       0 3919.49    .041       0 3938.67     .12       0
  4844.1     .07       0
#XS Ineff= 2 , 0
       0  3468.7      50               0
Permanent Ineff=
       F       F
#Block Obstruct= 5 ,-1
  387.66 3501.13   48.27 4054.96 4738.93   45.64    8379 9055.06   47.72
  9694.613248.13   48.2113312.9813728.24   50.88
Bank Sta=3878.57,3986.27
XS Rating Curve= 0
Exp/Cntr=.3,.1

Type RM Length L Ch R = 1 ,200707.1,691.8,739.09,857.4
XS GIS Cut Line= 6
     3134542.196    13787794.664     3134857.664    13783509.227
     3134830.721    13783486.494     3134774.311    13783403.983
      3134756.63    13783383.776     3135525.131    13772458.428
#Sta/Elev= 30
       0   49.34     195   49.58  238.92    42.2     327    42.2   388.4   51.24
 4332.37   45.11 4355.06   31.66 4373.53   30.46 4383.31   32.98 4423.26    43.9
 4480.78   49.96 4494.61    41.9 4536.23    39.6 4592.54    45.1 5042.22   46.45
  5143.4   41.99 12118.1   46.7812124.88   50.9812161.72   46.2912904.02   50.52
12953.39   45.6213350.32   47.5813368.51   53.67 13387.3      4714248.41   52.86
14277.54   48.1815334.58    51.315362.96    50.3 15387.1   41.5515411.88    46.2
#Mann= 4 ,-1 , 0
       0     .07       0 4355.06    .041       0 4383.31     .12       0
 5042.22     .07       0
#XS Ineff= 2 , 0
       0 3639.69      50               0
Permanent Ineff=
       F       F
#Block Obstruct= 5 ,-1
   97.71  415.27   49.57     480 3807.66    48.1 4471.35 4602.25   44.94
 5033.74 5193.73   45.82 8894.9815605.72    48.1
Bank Sta=4332.37,4423.26
XS Rating Curve= 0
Exp/Cntr=.3,.1

Type RM Length L Ch R = 1 ,199968.0,703.52,633.88,650.38
XS GIS Cut Line= 6
     3135094.613    13788118.046     3135434.549    13784682.209
     3135513.543    13783423.348     3135511.859    13783277.691
     3135504.282    13783170.763     3136213.303    13771923.184
#Sta/Elev= 30
       0   49.22  2026.8   50.61 3920.88   44.72 3949.33   50.01 4126.52   44.24
 4323.14   49.37 4780.25      45 4826.28   30.54  4853.8    35.5 4882.43   45.59
 4970.08   51.19 5052.76    39.6 5321.31   48.49 8063.97   43.74 8540.19   44.99
 8581.95   49.46 8593.83    45.612868.19   50.3313647.01   49.6414483.12   51.91
14503.76    40.914562.45   40.6214582.18   50.2514602.75   51.2215259.55   51.85
15336.17   50.13 15357.1   43.9615387.68   43.9615400.27   50.1316236.78   50.57
#Mann= 7 ,-1 , 0
       0     .07       0 4826.28    .041       0  4853.8     .07       0
 4970.08     .12       0 5321.31     .07       012868.19     .15       0
13647.01     .07       0
#XS Ineff= 2 , 0
       0    4750      50               0
Permanent Ineff=
       F       F
#Block Obstruct= 5 ,-1
  597.07 4012.74    47.9 4946.56 5221.37   45.18 8580.21 14017.1    47.9
14345.0414674.81    49.915141.9815444.27    49.9
Bank Sta=4780.25,4882.43
XS Rating Curve= 0
Exp/Cntr=.3,.1

Type RM Length L Ch R = 1 ,199334.1,487.21,759.61,601.99
XS GIS Cut Line= 6
     3135555.371    13788258.801     3136139.937    13784723.702
     3136151.583    13783369.353     3136115.538    13783236.435
     3136092.805    13783165.711     3137134.595    13771271.525
#Sta/Elev= 30
       0   49.24    4916   46.54 4968.46   43.29 4988.82    34.9 4990.34   30.66
 5001.07   30.09 5011.61   31.99 5051.98   43.72    5093   49.86 5120.51    49.9
 5135.32   44.41 5242.66   44.41 5380.79   44.71 8213.22   44.83 9038.54   49.86
10376.16    46.811197.46   51.7811271.88   44.1711284.79   48.6813360.22   49.05
13790.32    45.613830.45   49.5114650.97   51.8114680.25   50.03 14692.2    40.9
14716.36   40.6214729.34   50.2514761.96   45.1714779.47   50.2517089.29   49.46
#Mann= 9 ,-1 , 0
       0     .07       0    4916     .12       0 4988.82     .07       0
 5011.61    .041       0 5135.32     .07       0 5242.66     .12       0
 5380.79     .07       013360.22     .15       013790.32     .07       0
#XS Ineff= 2 , 0
       0    4700      50               0
Permanent Ineff=
       F       F
#Block Obstruct= 5 ,-1
  986.55 4145.49   47.84 9737.3517268.06    47.813331.0613863.48   49.09
 14537.414839.69   48.72
Bank Sta=4968.46,5051.98
XS Rating Curve= 0
Exp/Cntr=.3,.1

Type RM Length L Ch R = 1 ,198574.5,484.6,578.31,601.01
XS GIS Cut Line= 6
     3136183.653     13788519.17     3136801.221    13783055.466
     3136762.155    13782950.172     3136747.842    13782921.546
     3136731.845     13782880.29     3137497.339    13771116.063
#Sta/Elev= 30
       0   52.94 1703.32   50.13 1712.15   45.87  1717.6   50.13 4227.72   44.08
 4339.68   50.01 4483.43    44.6  5072.6   47.34 5086.17   36.57 5103.93    45.2
 5139.22   46.94 5551.37   44.18 5575.26   29.46 5588.36   28.86 5604.69   32.05
 5628.36   43.31 5668.67   48.48 5703.77   43.76  5950.5   42.4511436.78   50.65
11486.31   43.2211498.49   48.6813671.23   50.1614054.74   48.9214882.76   50.57
14905.53    40.914923.92   40.6214955.86   50.2517103.17   46.8517476.16   51.99
#Mann= 7 ,-1 , 0
       0     .07       0 5139.22     .12       0 5551.37     .07       0
 5588.36    .041       0 5604.69     .07       013671.23     .15       0
14054.74     .07       0
#XS Ineff= 2 , 0
       0    5000      49               0
Permanent Ineff=
       F       F
#Block Obstruct= 5 ,-1
 1239.53 4387.84   47.66 4974.05 5166.41   45.65 8806.81 17406.7   47.74
11267.1811541.98   47.8514839.6915059.54    48.4
Bank Sta=5551.37,5628.36
XS Rating Curve= 0
Exp/Cntr=.3,.1

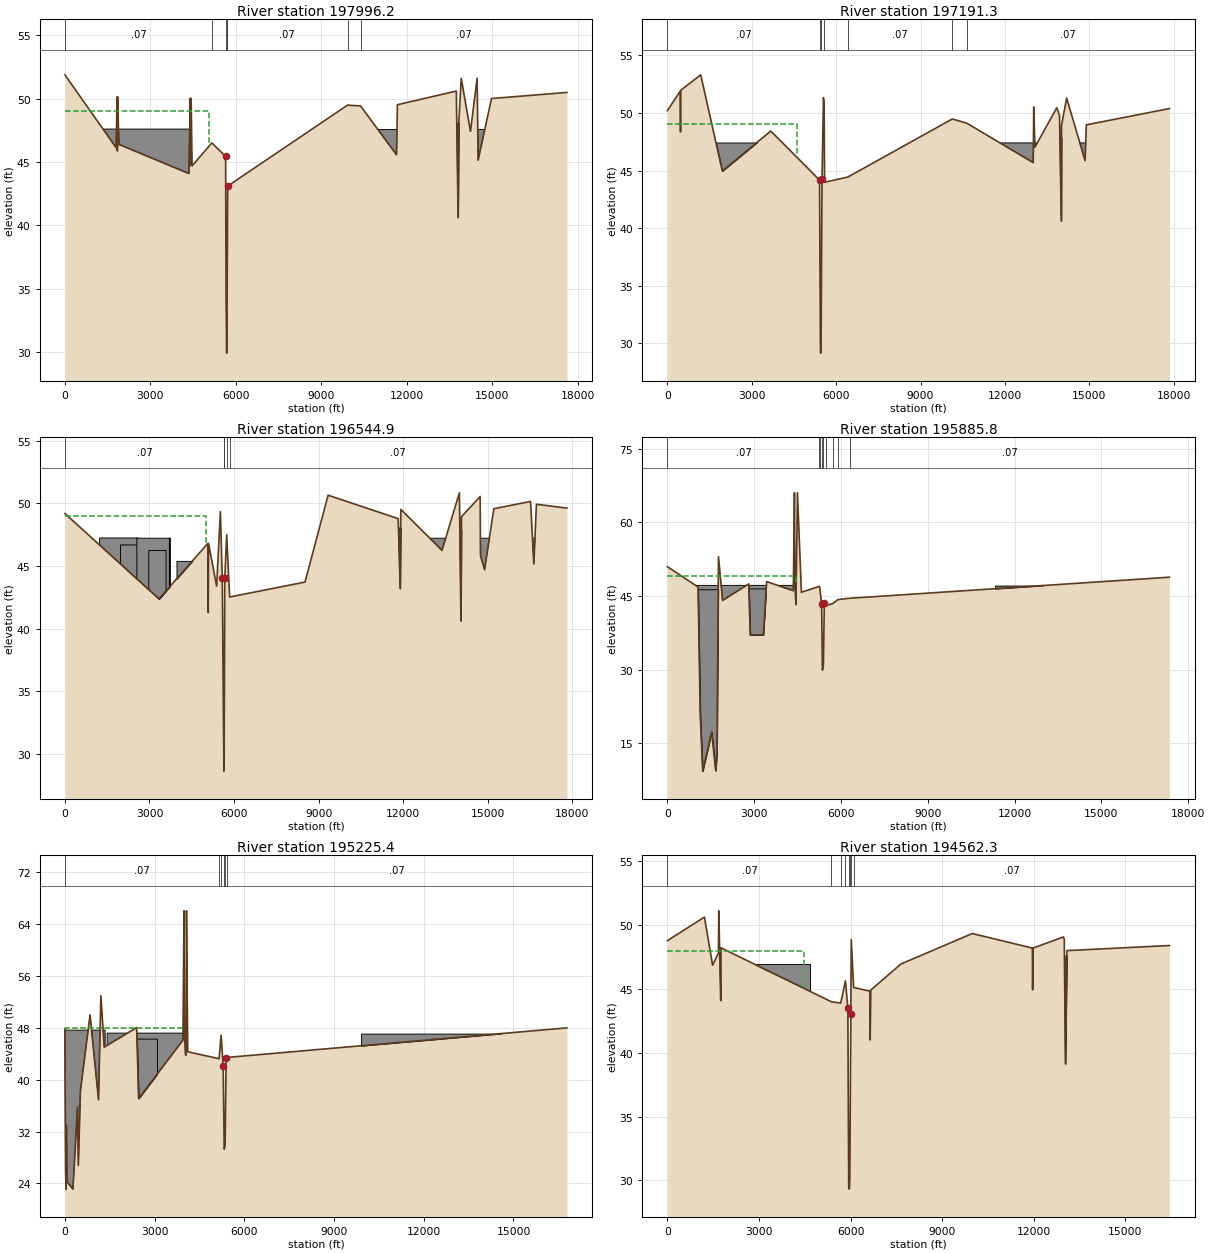
Type RM Length L Ch R = 1 ,197996.2,708.53,804.91,633.82
XS GIS Cut Line= 6
     3136755.333    13788666.335     3137244.603    13783070.606
     3137278.271    13783020.054     3137288.374    13783009.108
     3137331.117    13782930.021     3138067.366    13771116.063
#Sta/Elev= 30
       0   51.87 1799.09   46.12 1831.98   50.13 1841.18   45.87    1849   50.13
 1896.83   46.38 4352.28   44.08  4401.3   50.01 4410.16   44.72 4430.05   50.01
 4463.86   44.68 5157.16    46.5 5641.02   45.43 5657.39   34.25 5677.85   29.91
 5686.47   30.92 5713.41   43.09 9920.32   49.4810378.77   49.4111640.05   45.56
11670.07   49.5113738.04   50.5913800.25   40.6213822.99      4813910.68   51.59
14235.41   47.4214468.58   51.6114503.88   45.1414972.71      5017619.52   50.48
#Mann= 7 ,-1 , 0
       0     .07       0 5157.16     .12       0 5641.02     .07       0
 5677.85    .041       0 5686.47     .07       0 9920.32     .12       0
10378.77     .07       0
#XS Ineff= 2 , 0
       0    5050      49               0
Permanent Ineff=
       F       F
#Block Obstruct= 3 ,-1
  936.81 4381.57   47.59  8967.416845.34   47.5513648.8513893.13   48.09
Bank Sta=5641.02,5713.41
XS Rating Curve= 0
Exp/Cntr=.3,.1

Type RM Length L Ch R = 1 ,197191.3,664.18,646.38,600.72
XS GIS Cut Line= 6
     3137423.237    13788921.044     3137915.627     13783519.33
     3137933.308    13783443.555     3137931.105    13783392.074
     3137957.458    13783314.772     3138585.571    13771116.063
#Sta/Elev= 30
       0    50.2  454.56   51.89     466   48.35  474.54   51.97 1184.85   53.31
 1952.42   44.96 3675.57   48.43 5409.54   44.18 5438.31   30.18  5449.8   29.16
 5464.79   30.14 5497.82   44.24 5547.28   51.33 5573.03   50.83 5587.82   44.42
 5612.71      44 6416.16   44.4410130.06   49.4810647.83   49.1113007.37   45.69
13026.45   50.5213067.52   47.0313844.15   50.4513942.36   49.7714005.42   40.62
 14013.8   48.9214195.18   51.2914852.28   45.8714896.16   48.9717850.61   50.38
#Mann= 7 ,-1 , 0
       0     .07       0 5438.31    .041       0 5464.79     .07       0
 5573.03     .12       0 6416.16     .07       010130.06     .12       0
10647.83     .07       0
#XS Ineff= 2 , 0
       0 4610.69      49               0
Permanent Ineff=
       F       F
#Block Obstruct= 3 ,-1
 1392.44 3773.42   47.44 9035.3717389.27    47.4 13862.614076.34   47.85
Bank Sta=5409.54,5497.82
XS Rating Curve= 0
Exp/Cntr=.3,.1

Type RM Length L Ch R = 1 ,196544.9,1003.84,659.12,399.57
XS GIS Cut Line= 6
     3138159.471     13789004.27     3138536.145    13783431.768
      3138547.09    13783357.676     3138555.509    13783318.946
     3138574.032    13783261.694     3139051.957    13771219.704
#Sta/Elev= 30
       0   49.18 3337.97   42.37 5069.63   46.79 5085.73   41.28 5096.21   46.79
 5384.22   43.38  5516.6   49.33  5583.5   44.02 5641.54   28.63 5650.83    29.9
 5673.34      44 5739.68   47.49 5844.62   42.52 8518.26   43.71 9339.36   50.64
 11825.6   48.7711895.56    43.211919.29   49.51 13378.5   46.2413997.11   50.83
14050.61   40.6214070.86   48.9214733.46   50.5414744.73   45.8314891.12    44.7
 15218.2   49.5616520.89   50.1416637.79   45.1616729.32   49.92 17811.4   49.61
#Mann= 5 ,-1 , 0
       0     .07       0 5641.54    .041       0 5650.83     .07       0
 5739.68     .12       0 5844.62     .07       0
#XS Ineff= 2 , 0
       0 5007.63      49               0
Permanent Ineff=
       F       F
#Block Obstruct= 9 ,-1
 1215.62 2573.82   47.27 1956.77 2616.61   46.71    2536 3716.68   47.25
 2957.91 3572.24   46.27 3688.64 3721.66   47.25 3959.04 4505.12    45.4
10386.1417949.42   47.2111717.8612104.66   48.0713879.4114106.94   47.91
Bank Sta=5583.5,5673.34
XS Rating Curve= 0
Exp/Cntr=.3,.1

Type RM Length L Ch R = 1 ,195885.8,788.62,660.35,400.01
XS GIS Cut Line= 6
     3139085.246    13788791.433     3139500.899    13784433.249
     3139183.604    13783492.388     3139187.814    13783334.943
     3139002.979    13781570.207       3139414.7    13771530.628
#Sta/Elev= 30
       0   50.96 1059.12   46.83 1134.75   20.97 1219.22    9.33 1528.59   17.31
 1670.74     9.4 1713.06   13.24 1765.45      53 1906.88   44.08 2812.48   47.45
 2862.42   37.08 3317.45   37.08 3429.85   47.92  4352.4   46.07 4390.92      66
  4408.1   47.01 4442.36   43.22  4493.3      66 4631.88   45.75  5253.1   46.96
 5263.57   46.74  5330.6    43.4  5356.9   29.88 5389.53   30.85  5423.9   43.59
  5492.4   43.06 5714.06   43.45  5896.1   44.27  6305.7   44.5317351.45   48.82
#Mann= 9 ,-1 , 0
       0     .07       0  5253.1     .12       0 5263.57     .07       0
  5356.9    .041       0 5389.53     .07       0  5492.4     .12       0
 5714.06     .07       0  5896.1     .12       0  6305.7     .07       0
#XS Ineff= 2 , 0
       0 4451.91      49               0
Permanent Ineff=
       F       F
#Block Obstruct= 4 ,-1
  199.89 4379.83   47.15 1016.79  1868.7   46.36 2775.57 3407.63   46.54
11326.1917457.16   47.12
Bank Sta=5330.6,5423.9
XS Rating Curve= 0
Exp/Cntr=.3,.1

Type RM Length L Ch R = 1 ,195225.4,591.36,663.1,582.43
XS GIS Cut Line= 6
     3139932.906    13788475.954     3140123.299    13783852.342
     3139761.182    13783185.918     3139737.608    13783153.924
     3139376.419    13781528.713     3139777.444    13771841.551
#Sta/Elev= 30
       0   47.83   21.77   26.04   37.64   23.13   48.82   32.95   75.88   24.24
  269.01   23.13  422.82    35.8  450.54   26.79  519.91   38.31  841.54   49.98
 1124.59   36.89 1202.54   52.92 1315.89      45 2400.91   48.02 2465.86   37.08
 3947.48   46.07  3983.7      66 3999.07   47.01 4028.96   43.95 4052.79   43.74
 4065.58      66 4107.39   44.29 5155.13   43.22  5222.7   46.82 5292.08   42.11
 5327.28   29.28 5357.96   29.82 5390.58   43.34 5408.13   43.4116786.24   47.97
#Mann= 6 ,-1 , 0
       0     .07       0 5155.13     .12       0  5222.7     .07       0
 5327.28    .041       0 5357.96     .12       0 5408.13     .07       0
#XS Ineff= 2 , 0
       0 3984.73      48               0
Permanent Ineff=
       F       F
#Block Obstruct= 4 ,-1
  -137.4 1346.56   47.62 1413.32 3975.49   47.16 2335.88 3077.86   46.31
 9903.8516960.52   47.09
Bank Sta=5292.08,5390.58
XS Rating Curve= 0
Exp/Cntr=.3,.1

Type RM Length L Ch R = 1 ,194562.3,409.22,879.19,792.49
XS GIS Cut Line= 6
     3140451.112    13788683.236     3140662.713    13783644.875
     3140311.818    13782855.032     3140259.617    13782729.581
     3139998.819     13781736.18     3140144.434    13772358.398
#Sta/Elev= 30
       0   48.79 1213.01   50.64 1480.97   46.87 1672.96   47.81 1682.79   51.13
 1747.41   44.09 1756.95   48.23 5374.84      44  5677.9    43.9 5832.71   45.64
 5911.64   43.55 5940.64   29.48 5960.91   29.31 5976.22      30 6010.11   43.02
    6023   48.88 6101.57   45.12 6635.63   44.83 6643.72   41.01 6665.18   44.92
 7650.22   46.96 9989.44   49.3511958.95   48.2111966.77   44.9411979.63   48.21
12975.44   49.0813002.85   48.9313041.72   39.1413089.75   48.0116449.01   48.41
#Mann= 8 ,-1 , 0
       0     .07       0 5374.84     .12       0  5677.9     .07       0
 5832.71     .12       0 5940.64     .07       0 5976.22    .041       0
 6010.11     .12       0 6101.57     .07       0
#XS Ineff= 2 , 0
       0 4479.39      48               0
Permanent Ineff=
       F       F
#Block Obstruct= 3 ,-1
 1308.62 4682.92   46.98 9065.1316878.66    47.112806.11 13108.4   47.62
Bank Sta=5911.64,6010.11
XS Rating Curve= 0
Exp/Cntr=.3,.1