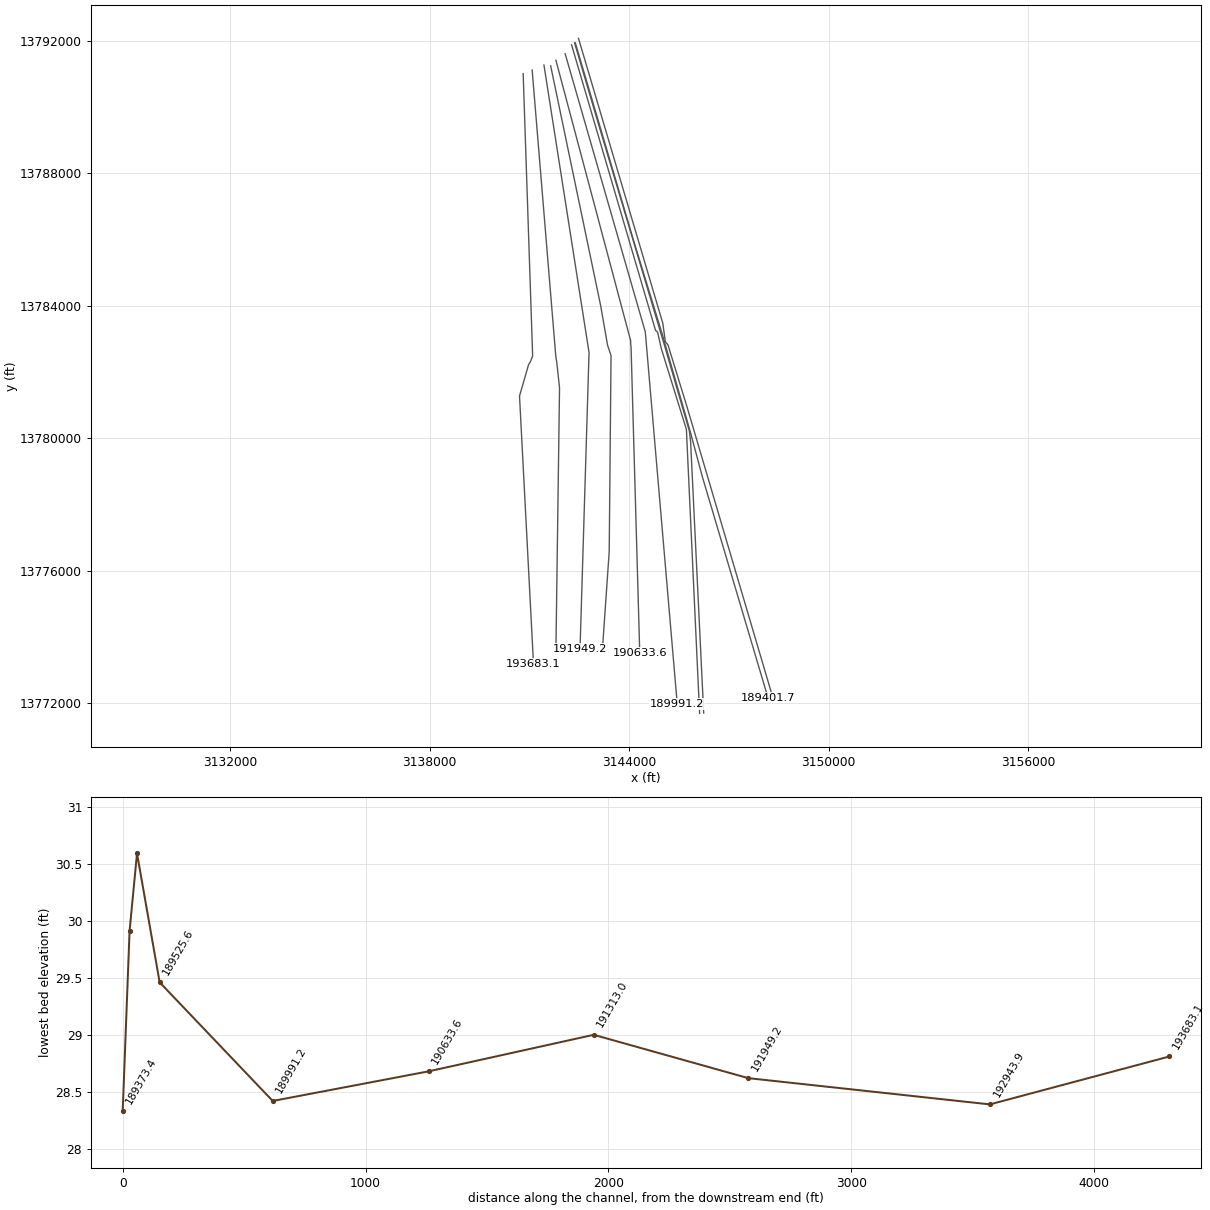
HEC-RAS study A100-00-00.prj: A100-00-00

--- A100-00-00.g01 (geometry) --- (continued)

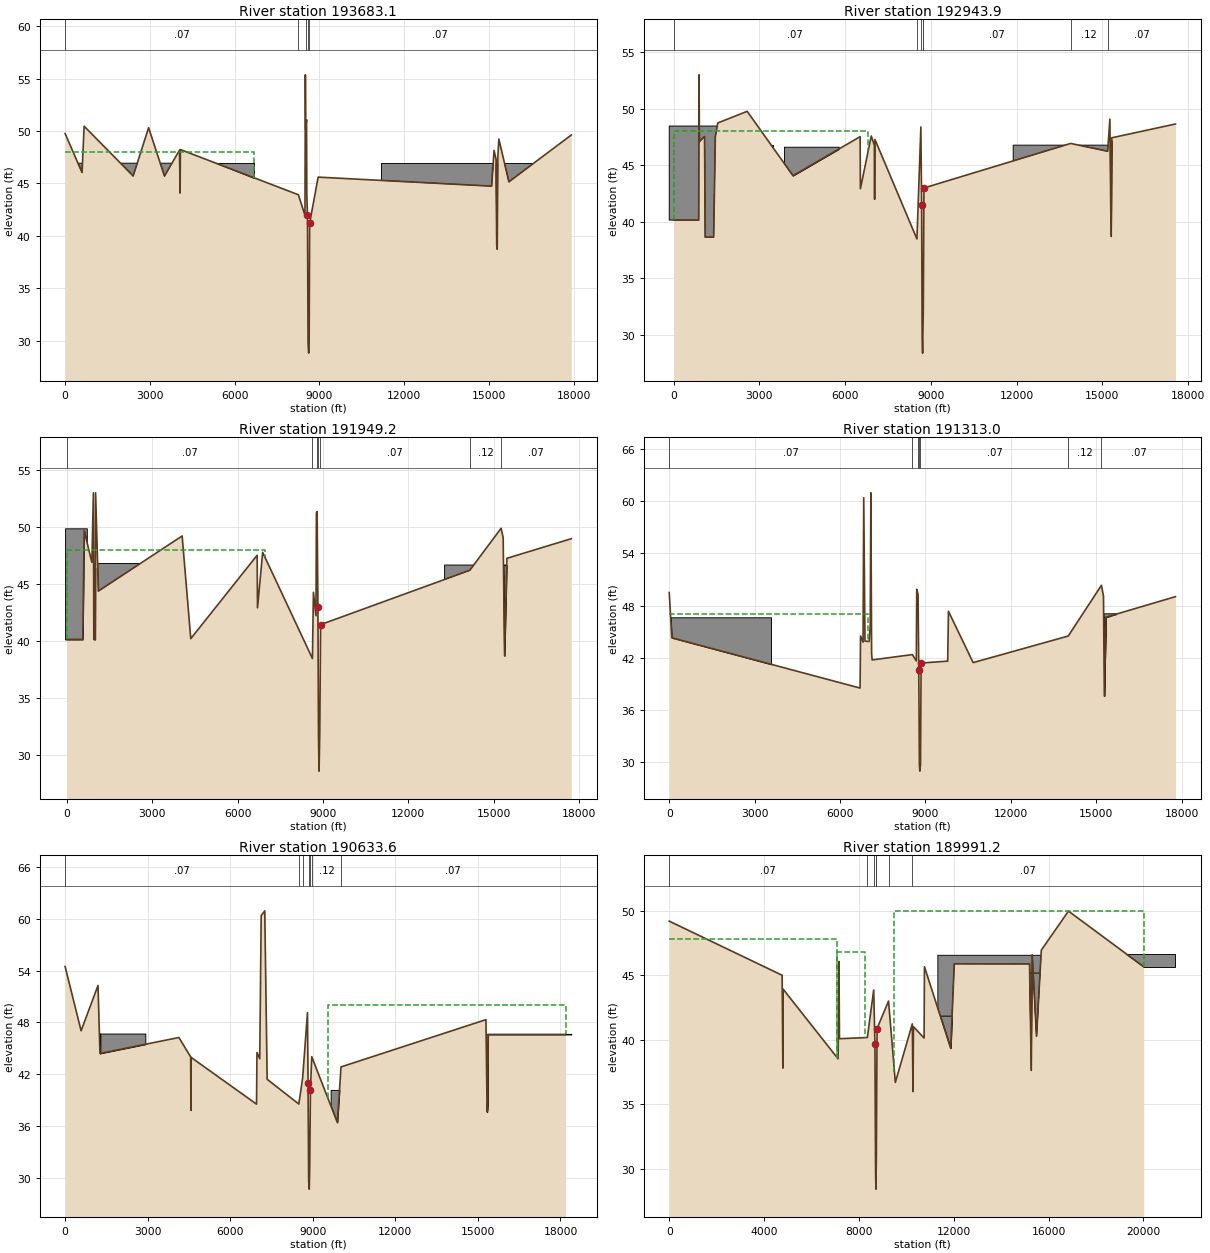
Type RM Length L Ch R = 1 ,193683.1,653.28,739.2,1135.4
XS GIS Cut Line= 6
     3140813.856    13791015.161     3141099.041    13782488.783
     3141031.685    13782316.183      3140977.41    13782228.971
     3140704.206    13781279.753     3141124.779    13773188.886
#Sta/Elev= 30
       0   49.76  600.13   46.04   672.9   50.46 2407.66   45.71 2954.79   50.32
 3515.51    45.7 4046.74   48.17 4068.07   44.09  4078.7   48.23  8252.4   43.92
 8486.03   41.96 8500.07   55.36 8512.27   50.17 8541.86   51.07 8551.15   43.96
 8574.56      42 8596.41   29.64 8617.65   28.81  8633.7   29.67 8651.83    41.2
 8952.29    45.615090.18   44.7415175.81   48.1515246.94   47.2815268.84   39.14
15287.59   38.7315308.71   47.4415345.79   49.23 15700.3   45.1517908.89   49.62
#Mann= 5 ,-1 , 0
       0     .07       0  8252.4     .12       0 8512.27     .07       0
 8596.41    .041       0  8633.7     .07       0
#XS Ineff= 2 , 0
       0 6687.02      48               0
Permanent Ineff=
       F       F
#Block Obstruct= 3 ,-1
    80.3 6672.34   46.9311193.2216598.63    46.9 15114.515297.71   46.53
Bank Sta=8574.56,8651.83
XS Rating Curve= 0
Exp/Cntr=.3,.1

Type RM Length L Ch R = 1 ,192943.9,937.28,994.68,885.57
XS GIS Cut Line= 6
     3141084.089    13791121.973     3141790.282     13782535.09
     3141809.647    13782376.804     3141819.751    13782337.232
     3141907.514    13781528.713     3141798.447    13773603.451
#Sta/Elev= 30
       0   40.16  878.73   40.16  889.26   53.01  903.56    47.1 1082.43   47.56
 1104.91   38.65 1400.92   38.65 1460.16   47.56 1543.24   48.75 2574.06   49.78
 4174.69   44.09 6525.52   47.54 6534.42   42.93 6914.91    47.6 7022.06   46.79
 7031.42      42 7043.71   47.29 8512.16   38.49 8649.85   48.39 8677.31   41.49
 8694.71   29.77 8710.97   28.39 8735.48   32.27 8757.53      4313890.54   46.94
15183.69   46.2515261.85   49.0915303.58   38.7315327.66   47.4417555.75   48.66
#Mann= 7 ,-1 , 0
       0     .07       0 8512.16     .12       0 8649.85     .07       0
 8710.97    .041       0 8735.48     .07       013890.54     .12       0
15183.69     .07       0
#XS Ineff= 2 , 0
       0 6809.16      48               0
Permanent Ineff=
       F       F
#Block Obstruct= 5 ,-1
 -152.67 1709.92   48.48 2054.96 3464.76   46.84 3859.33 5777.33   46.65
11880.0516373.09   46.7915267.3515699.66    47.2
Bank Sta=8677.31,8757.53
XS Rating Curve= 0
Exp/Cntr=.3,.1

Type RM Length L Ch R = 1 ,191949.2,567.33,636.26,708.73
XS GIS Cut Line= 6
     3141438.779    13791273.983     3142798.939    13782563.717
     3142792.203    13782516.568     3142788.836     13782435.74
     3142788.836    13782408.798     3142523.935    13773655.271
#Sta/Elev= 30
       0   40.16  559.44   40.16  609.15   49.69  879.44   46.92  933.45   53.01
   948.5   40.16  995.72   40.16 1010.79   53.01 1109.23    44.4  4052.3   49.23
 4355.35   40.23 6688.06   47.54 6700.06   42.93 6882.45   47.79 8630.98   38.49
 8665.86   44.29 8755.37   42.24 8769.92   51.24 8795.75   51.37 8823.95      43
 8843.16   31.84 8863.14   28.62 8889.54   31.94 8917.82   41.4614160.11   46.22
15260.15    49.915333.85   49.09 15383.3   38.7315464.78   47.2717728.83   48.99
#Mann= 7 ,-1 , 0
       0     .07       0 8630.98     .12       0 8795.75     .07       0
 8843.16    .041       0 8889.54     .07       014160.11     .12       0
15260.15     .07       0
#XS Ineff= 2 , 0
       0 6961.83      48               0
Permanent Ineff=
       F       F
#Block Obstruct= 5 ,-1
  -61.07  702.29    49.9  666.05 3908.65   46.81  854.96 1038.17   46.44
13276.0617732.78   46.68 15114.515541.98   46.68
Bank Sta=8823.95,8917.82
XS Rating Curve= 0
Exp/Cntr=.3,.1

Type RM Length L Ch R = 1 ,191313.0,586.9,679.33,647.23
XS GIS Cut Line= 6
     3141640.489    13791248.895     3143143.999    13784006.374
     3143351.719    13782812.254     3143455.703    13782502.863
     3143400.696    13776580.497     3143199.006    13773665.153
#Sta/Elev= 30
       0   49.49   89.71    44.3  6703.3   38.53 6719.33   44.51  6807.8   43.79
 6831.38   60.37  6875.4   43.92 7020.93   43.87 7058.95   45.59 7082.73   60.93
 7107.87   42.51  7126.7   41.76 8539.96   42.37 8678.07   41.64 8693.12   49.86
 8739.62   49.27 8764.95   40.59 8786.78   29.74 8802.43      29 8824.92   29.74
 8847.36    41.4 9780.33   41.62 9806.61   47.3410674.46   41.4514014.97    44.5
15179.74   50.3215252.56   49.0915282.74   37.6315337.86   46.6617780.48   49.02
#Mann= 7 ,-1 , 0
       0     .07       0 8539.96     .12       0 8739.62     .07       0
 8786.78    .041       0 8824.92     .07       014014.97     .12       0
15179.74     .07       0
#XS Ineff= 2 , 0
       0 6992.37      47               0
Permanent Ineff=
       F       F
#Block Obstruct= 3 ,-1
 -294.47 3574.34   46.6514760.5718158.63   46.7815199.0915699.66   47.11
Bank Sta=8764.95,8847.36
XS Rating Curve= 0
Exp/Cntr=.5,.3

Type RM Length L Ch R = 1 ,190633.6,481.42,642.46,544.6
XS GIS Cut Line= 6
      3141798.57    13791417.191     3144045.867    13782948.488
     3144045.867    13782850.822     3144052.603    13782813.776
     3144057.655    13782760.733      3144318.43    13773528.916
#Sta/Elev= 30
       0   54.48  581.74   47.03  1195.9   52.28 1266.46    44.4 4134.53   46.25
 4562.49      44 4572.33   37.81 4581.16   43.94 6955.76   38.53 6971.74   44.51
 7072.66   43.79 7125.25   60.37 7255.11   60.93 7341.82   41.41 8492.47   38.54
 8631.32   41.56  8807.1   49.13 8828.02   40.98 8849.96   29.58  8871.2   28.68
 8889.55   31.45 8914.17   40.18 8961.75   44.03 9892.41    36.410025.76   42.84
15291.68   48.3215334.25   37.63 15359.4   38.7315370.09    46.618186.15    46.6
#Mann= 7 ,-1 , 0
       0     .07       0 8492.47     .12       0 8631.32     .07       0
  8871.2    .041       0 8889.55     .07       0 8961.75     .12       0
10025.76     .07       0
#XS Ineff= 2 ,-1
       0 7175.57    47.8 9551.3718186.15   50.01
Permanent Ineff=
       F       F
#Block Obstruct= 5 ,-1
 1187.83 2914.64   46.71  1188.9 1281.37   46.71 9648.85 10137.4   40.18
14144.2918393.72   46.6715145.0415603.05   45.63
Bank Sta=8828.02,8914.17
XS Rating Curve= 0
Exp/Cntr=.5,.3

Type RM Length L Ch R = 1 ,189991.2,312.98,465.56,697.46
XS GIS Cut Line= 6
      3142075.92    13791615.298     3144476.946    13783244.855
     3144486.207    13783222.122     3144484.523    13783199.389
     3144491.512    13783148.961     3145445.975    13771982.569
#Sta/Elev= 30
       0   49.21 4762.11   45.01  4793.2   37.81 4800.81   43.94 7121.59   38.53
 7160.44   46.08 7179.53   40.09 8356.51   40.18 8624.46   43.87 8676.48   39.64
 8703.23   29.74 8718.14   28.42 8736.48   30.92  8766.1   40.88  9250.5   43.01
 9536.89    36.710253.24   41.2410282.12   35.9910300.76   41.0210749.91   40.14
10764.27   45.6711873.59   39.3512022.72    45.915197.97   45.8915270.96   37.63
15311.17    46.6 15493.2   40.2815694.05   46.9616839.73   49.9920013.67   45.67
#Mann= 7 ,-1 , 0
       0     .07       0 8356.51     .12       0 8624.46     .07       0
 8703.23    .041       0 8736.48     .07       0  9250.5     .12       0
10253.24     .07       0
#XS Ineff= 3 ,-1
       0    7093    47.8    7093 8269.85    46.8    950020013.67   50.01
Permanent Ineff=
       F       F       F
#Block Obstruct= 5 ,-1
 1218.48 2437.48   46.7111330.1715862.67   46.5611335.8812213.74   41.88
 14885.515839.69   45.1815928.6121352.48   46.67
Bank Sta=8676.48,8766.1
XS Rating Curve= 0
Exp/Cntr=.5,.3

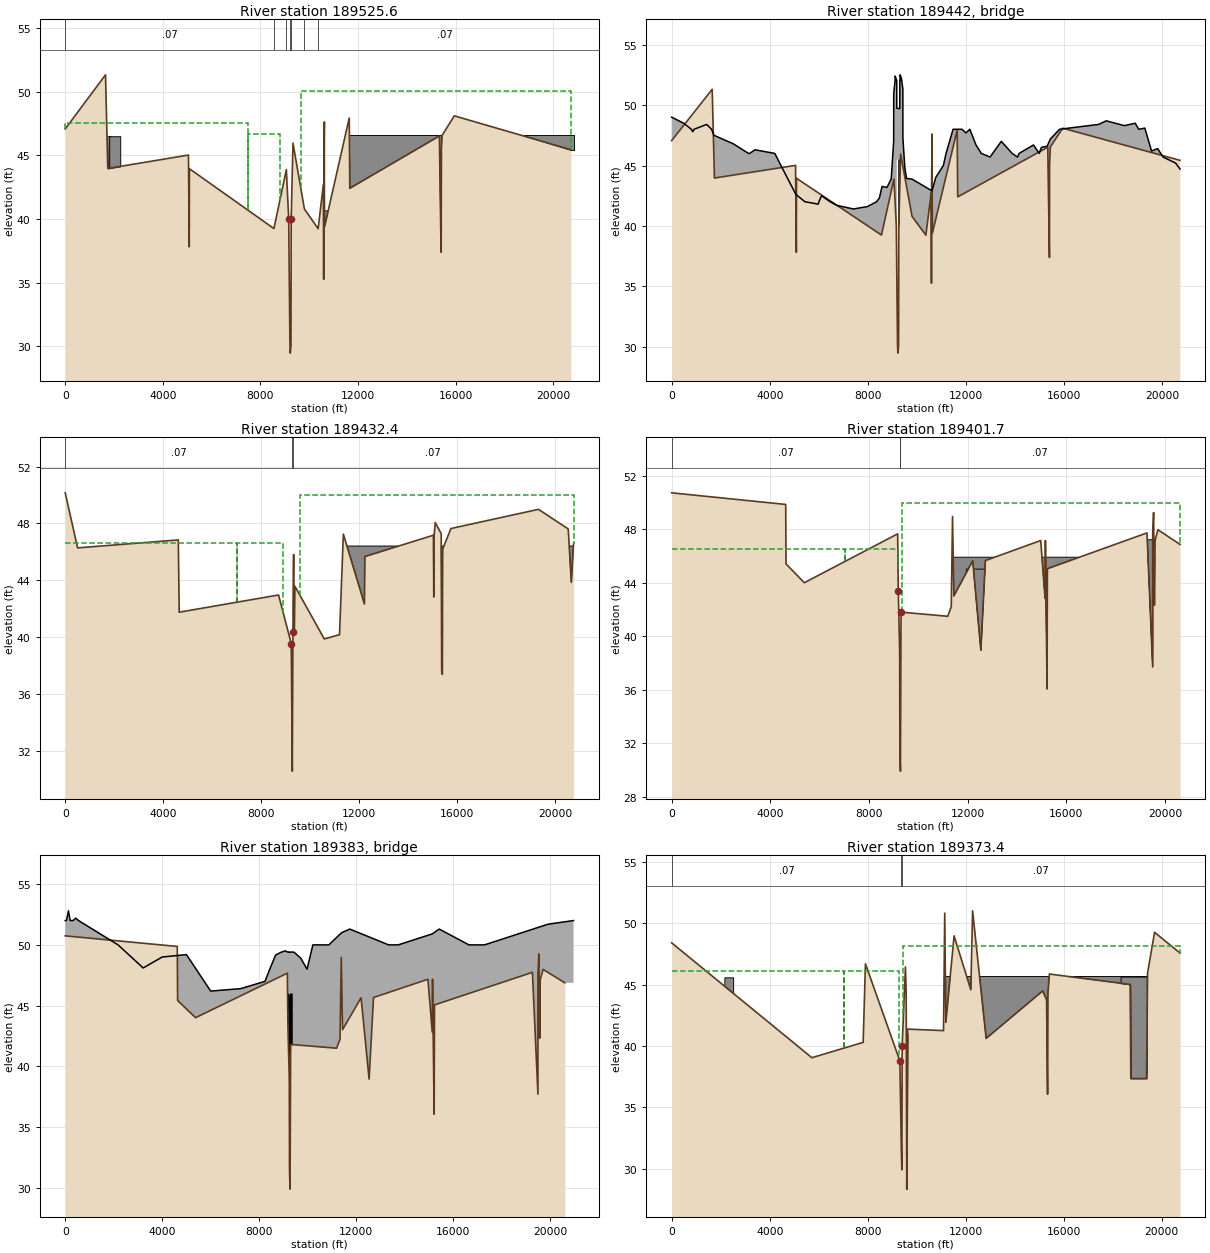
Type RM Length L Ch R = 1 ,189525.6,122.42,93.25,91.54
XS GIS Cut Line= 6
     3142268.066    13791886.174     3144791.737    13783267.685
     3144857.588    13783200.182      3144964.92    13782718.569
     3145721.012    13780272.887     3146118.066    13771698.215
#Sta/Elev= 30
       0   47.06 1651.95   51.31 1743.16   43.96 5049.57   45.01 5082.04   37.81
 5088.48   43.94 8551.41   39.24 9060.74   43.87 9157.11   40.01 9206.38   30.25
 9220.99   29.46 9250.32   30.04 9258.84   39.99 9332.35   45.95 9799.75   40.78
10362.64   39.2310580.69   42.7410590.43   35.2610598.33   43.9310618.24   47.61
10618.52   42.0910628.39    39.411637.78   47.9211660.16    42.415331.16   46.51
15399.78   37.3915405.23   45.0615437.44   46.5415941.88   48.0920717.81   45.43
#Mann= 7 ,-1 , 0
       0     .07       0 8551.41     .12       0 9060.74     .07       0
 9206.38    .041       0 9250.32     .07       0 9799.75     .12       0
10362.64     .07       0
#XS Ineff= 3 ,-1
       0    7506    47.5    7506    8800    46.7    965020717.81   50.01
Permanent Ineff=
       F       F       F
#Block Obstruct= 5 ,-1
 1533.22 1866.36   46.49 1802.78 2255.22   46.4910458.0210839.69   40.63
11487.9520826.84   46.5515190.8415534.35   45.18
Bank Sta=9157.11,9258.84
XS Rating Curve= 0
Exp/Cntr=.5,.3

Type RM Length L Ch R = 3 ,189442  ,,,
BEGIN DESCRIPTION:
Mykawa Rd.
END DESCRIPTION:
Bridge Culvert--1,0,-1,-1, 0
Deck Dist Width WeirC Skew NumUp NumDn MinLoCord MaxHiCord MaxSubmerge Is_Ogee
5,84,2.6,0, 82, 82, , , .95, 0, 0,0,,
       0     491     800     861     911    1428    1625    1724    2510    3132
    3180    3396    4204    4707    5065    5431    5974    6003    6110    6456
    6725    7411    7983    8351    8466    8577    8776    8950    9050    9051
    9108    9109    9175    9176    9217    9259    9299    9300    9301    9310
    9311    9364    9425    9426    9503    9573    9700    9800   10614   10763
   11076   11185   11472   11835   11997   12155   12406   12623   12979   13085
   13436   13882   14097   14163   14748   14986   15070   15308   15439   15811
   16600   17402   17718   18451   18898   19039   19288   19562   19808   20034
   20544   20722
      49    48.5      48    47.8      48    48.4      48    47.5    46.8      46
      46    46.3      46      44    42.6      42    41.8      42    42.5      42
    41.7    41.4    41.6      42    42.3   43.27   43.18   43.89      47   50.95
   52.06   52.41   52.03   49.75   49.72   49.72   49.71   52.07   52.07   52.08
   52.51   52.23   51.33    47.3   44.85   43.93    43.9   43.87    42.9      44
      45      46      48      48    47.7      48    46.7      46    45.7      46
      47      46    45.7      46    46.7      46    46.5    46.6    47.2      48
    48.2    48.4    48.7    48.3    48.5      48    48.1    46.2    46.4    45.7
    45.2    44.7
                                                                                
                                                                                
                                                                                
                           45.47    45.5   45.52    45.5   45.58
                                                                                
                                                                                
                                                                                
                                                                                
                
       0     518     827     888     938    1455    1652    1751    2537    3159
    3207    3423    4231    4734    5092    5458    6001    6030    6137    6483
    6752    7438    8010    8378    8493    8604    8803    8977    9077    9078
    9135    9136    9202    9203    9244    9286    9326    9327    9328    9337
    9338    9391    9452    9453    9530    9600    9727    9827   10641   10790
   11103   11212   11499   11862   12024   12182   12433   12650   13006   13112
   13463   13909   14124   14190   14775   15013   15097   15335   15466   15838
   16627   17429   17745   18478   18925   19066   19315   19589   19835   20061
   20571   20749
      49    48.5      48    47.8      48    48.4      48    47.5    46.8      46
      46    46.3      46      44    42.6      42    41.8      42    42.5      42
    41.7    41.4    41.6      42    42.3   43.27   43.18   43.89      47   50.95
   52.06   52.41   52.03   49.75   49.72   49.72   49.71   52.07   52.07   52.08
   52.51   52.23   51.33    47.3   44.85   43.93    43.9   43.87    42.9      44
      45      46      48      48    47.7      48    46.7      46    45.7      46
      47      46    45.7      46    46.7      46    46.5    46.6    47.2      48
    48.2    48.4    48.7    48.3    48.5      48    48.1    46.2    46.4    45.7
    45.2    44.7
                                                                                
                                                                                
                                                                                
                           45.47    45.5   45.52    45.5   45.58
                                                                                
                                                                                
                                                                                
                                                                                
                
Pier Skew, UpSta & Num, DnSta & Num=  ,9218, 2 ,9245, 2 , 0 , 0 , 0 ,,
     1.5     1.5
       0      48
     1.5     1.5
       0      48
Pier Skew, UpSta & Num, DnSta & Num=  ,9260, 2 ,9287, 2 , 0 , 0 , 0 ,,
     1.5     1.5
       0      48
     1.5     1.5
       0      48
Abutment Skew #Up #Dn= , 2 , 2
    9176    9196
      44      34
    9203    9225
      44      34
Abutment Skew #Up #Dn= , 2 , 2
    9295    9300
      43      44
    9321    9327
      43      44
BR Coef=-1 , 1 , 1 ,1.25, 0 ,,,.8,-1,2,0,
WSPro=,,,, 1 ,,,, 0 ,,,, 0 ,,,,-1 ,-1 ,-1 , 0 , 0 , 0 , 0 , 0
BC Design=,, 0 ,, 0 ,,,,,,
BC HTab HWMax=51.31

Type RM Length L Ch R = 1 ,189432.4,15.47,30.63,17.62
XS GIS Cut Line= 6
     3142359.204    13791944.272     3143012.958    13789712.577
     3145090.029    13782716.021     3145809.828    13780227.022
     3145847.731    13779909.625     3146241.113     13771709.45
#Sta/Elev= 30
       0   50.15  506.69   46.28  4615.1   46.84 4652.29   41.76 8706.43   42.97
 9225.57   39.55 9267.42   30.59 9293.29   40.34 9321.86   45.81 9326.42   41.53
 9349.17   40.14 9374.93   43.5810572.41   39.8811194.81   40.1811350.95   47.25
12211.19   42.3412227.67   45.6715024.61   47.1715041.25   42.8315055.23   47.17
15101.25   48.0615344.44   47.2815363.67   37.6315391.97   37.3915402.03   46.18
15740.65   47.64 19313.5   48.9920527.95   47.6120654.34   43.8620744.12   46.58
#Mann= 3 ,-1 , 0
       0     .07       0 9267.42    .041       0 9293.29     .07       0
#XS Ineff= 3 ,-1
       0    7024    46.6    7024    8900    46.6    960020744.12   50.01
Permanent Ineff=
       F       F       F
#Block Obstruct= 1 ,-1
11359.4521074.99   46.41
Bank Sta=9225.57,9293.29
XS Rating Curve= 0
Exp/Cntr=.5,.3

Type RM Length L Ch R = 1 ,189401.7,147.17,28.33,89.77
XS GIS Cut Line= 6
     3142382.383    13791940.961     3144132.893     13785976.63
     3144994.785    13783148.849     3145839.206    13780196.832
     3146210.993    13778807.167     3148175.142    13772167.077
#Sta/Elev= 30
       0   50.74 4622.12   49.87 4636.94   45.42 5377.03   44.01  9161.7   47.67
 9185.61   43.42 9242.11    38.9 9251.14   31.42 9273.81   29.91 9298.28   41.81
11191.95    41.511334.32   42.2211385.25   48.9711438.51   43.0212203.63   45.65
12534.81   38.9612717.46   45.67 14960.3   47.17   15139   42.8315150.56   47.17
15216.97   36.0715231.21   45.0619268.92   47.7419499.14   37.7219500.37   47.74
19536.24   49.2619569.97   42.3319591.64   47.1319710.09   47.9820606.58   46.88
#Mann= 3 ,-1 , 0
       0     .07       0 9251.14    .041       0 9273.81     .07       0
#XS Ineff= 3 ,-1
       0    7024    46.5    7024    9176    46.5    934320606.58      50
Permanent Ineff=
       F       F       F
#Block Obstruct= 4 ,-1
11393.9120735.73   45.9211946.56 12862.6   45.03   1500015305.34   44.32
 18931.319732.82   47.23
Bank Sta=9185.61,9298.28
XS Rating Curve= 0
Exp/Cntr=.5,.3

Type RM Length L Ch R = 3 ,189383  ,,,
BEGIN DESCRIPTION:
AT&SF RR
END DESCRIPTION:
Bridge Culvert--1,0,-1,-1, 0
Deck Dist Width WeirC Skew NumUp NumDn MinLoCord MaxHiCord MaxSubmerge Is_Ogee
5,19,2.6,0, 49, 49, , , .95, 0, 0,0,,
       0      51     133     205     326     436     549    2179    3216    4000
    5000    6000    7238    8240    8437    8677    8876    9076    9175    9176
    9189    9203    9217    9231    9246    9260    9273    9287    9301    9315
    9329    9343    9344    9443    9717    9975   10215   10376   10876   11398
   11736   13338   13739   15136   15426   16651   17297   19914   20966
      52      52    52.8      52      52    52.2      52      50    48.1      49
    49.2    46.2    46.4      47      48   49.16   49.37   49.51   49.41   49.41
    49.4    49.4   49.39   49.42   49.41   49.41    49.4   49.39    49.4    49.4
   49.41   49.42   49.42   49.39    48.9      48      50      50      50      51
    51.3      50      50    50.9    51.3      50      50    51.7      52
                                                                                
                                                                           46.07
   46.02   46.03   45.97   45.98      46   46.04   46.06   46.03      46   46.03
   46.08   46.07
                                                                        
       0     168     250     322     443     553     666    2296    3333    4100
    5100    5940    7355    8357    8554    8794    8993    9193    9292    9293
    9306    9320    9334    9348    9363    9377    9390    9404    9418    9432
    9446    9460    9461    9560    9834   10092   10332   10493   10993   11515
   11853   13455   13856   15253   15543   16768   17414   20031   21083
      52      52    52.8      52      52    52.2      52      50    48.1      49
    49.2    46.2    46.4      47      48   49.16   49.37   49.51   49.41   49.41
    49.4    49.4   49.39   49.42   49.41   49.41    49.4   49.39    49.4    49.4
   49.41   49.42   49.42   49.39    48.9      48      50      50      50      51
    51.3      50      50    50.9    51.3      50      50    51.7      52
                                                                                
                                                                           46.07
   46.02   46.03   45.97   45.98      46   46.04   46.06   46.03      46   46.03
   46.08   46.07
                                                                        
Pier Skew, UpSta & Num, DnSta & Num=  ,9177.1, 2 ,9294.1, 2 , 0 , 0 , 0 ,,
       1       1
       0      47
       1       1
       0      47
Pier Skew, UpSta & Num, DnSta & Num=  ,9189, 2 ,9306, 2 , 0 , 0 , 0 ,,
       1       1
       0      47
       1       1
       0      47
Pier Skew, UpSta & Num, DnSta & Num=  ,9203, 2 ,9320, 2 , 0 , 0 , 0 ,,
       1       1
       0      47
       1       1
       0      47
Pier Skew, UpSta & Num, DnSta & Num=  ,9218, 2 ,9335, 2 , 0 , 0 , 0 ,,
       1       1
       0      47
       1       1
       0      47
Pier Skew, UpSta & Num, DnSta & Num=  ,9231, 2 ,9348, 2 , 0 , 0 , 0 ,,
       1       1
       0      47
       1       1
       0      47
Pier Skew, UpSta & Num, DnSta & Num=  ,9246, 2 ,9363, 2 , 0 , 0 , 0 ,,
       1       1
       0      47
       1       1
       0      47
Pier Skew, UpSta & Num, DnSta & Num=  ,9260, 2 ,9377, 2 , 0 , 0 , 0 ,,
       1       1
       0      47
       1       1
       0      47
Pier Skew, UpSta & Num, DnSta & Num=  ,9273, 2 ,9390, 2 , 0 , 0 , 0 ,,
       1       1
       0      47
       1       1
       0      47
Pier Skew, UpSta & Num, DnSta & Num=  ,9287, 2 ,9404, 2 , 0 , 0 , 0 ,,
       1       1
       0      47
       1       1
       0      47
Pier Skew, UpSta & Num, DnSta & Num=  ,9301, 2 ,9418, 2 , 0 , 0 , 0 ,,
       1       1
       0      47
       1       1
       0      47
Pier Skew, UpSta & Num, DnSta & Num=  ,9315, 2 ,9432, 2 , 0 , 0 , 0 ,,
       1       1
       0      47
       1       1
       0      47
Pier Skew, UpSta & Num, DnSta & Num=  ,9329, 2 ,9446, 2 , 0 , 0 , 0 ,,
       1       1
       0      47
       1       1
       0      47
Pier Skew, UpSta & Num, DnSta & Num=  ,9341.9, 2 ,9458.9, 2 , 0 , 0 , 0 ,,
       1       1
       0      47
       1       1
       0      47
BR Coef=-1 , 0 , 1 ,1.05, 0 ,,,.8,-1,1.2,0,
WSPro=,,,, 1 ,,,, 0 ,,,, 0 ,,,,-1 ,-1 ,-1 , 0 , 0 , 0 , 0 , 0
BC Design=,, 0 ,, 0 ,,,,,,
BC HTab HWMax=51.55

Type RM Length L Ch R = 1 ,189373.4,452.92,583.55,408.24
XS GIS Cut Line= 6
     3142477.343    13792079.353     3145012.816    13783474.842
     3145088.594    13782916.088     3145167.671    13782824.168
     3145742.132    13780944.499      3148312.49    13772199.676
#Sta/Elev= 30
       0    48.4 5721.82   39.04 7814.26   40.29 7907.27   46.69 9312.24   38.78
 9372.27   31.42 9393.71   29.91 9405.66   40.01 9539.16   46.44 9570.75   44.14
 9593.85   28.33 9626.58   41.3711093.47   41.2511142.98   50.8211187.38   41.92
 11524.8   48.9712207.52   44.5812279.48   51.0112833.11   40.6115140.45   44.48
15298.36   43.7715339.01   36.0715350.96   44.18 15413.7   45.86 18712.7   45.01
18735.54   37.3519379.38   37.3519420.41   45.9419706.94   49.2620743.58   47.57
#Mann= 3 ,-1 , 0
       0     .07       0 9372.27    .041       0 9393.71     .07       0
#XS Ineff= 3 ,-1
       0    7024    46.1    7024    9293    46.1    946020743.58   48.14
Permanent Ineff=
       F       F       F
#Block Obstruct= 4 ,-1
    2150 2509.15   45.59  9548.1 9631.72   41.0211132.7321086.54   45.66
18320.6119389.31   45.65
Bank Sta=9312.24,9405.66
XS Rating Curve= 0
Exp/Cntr=.5,.3