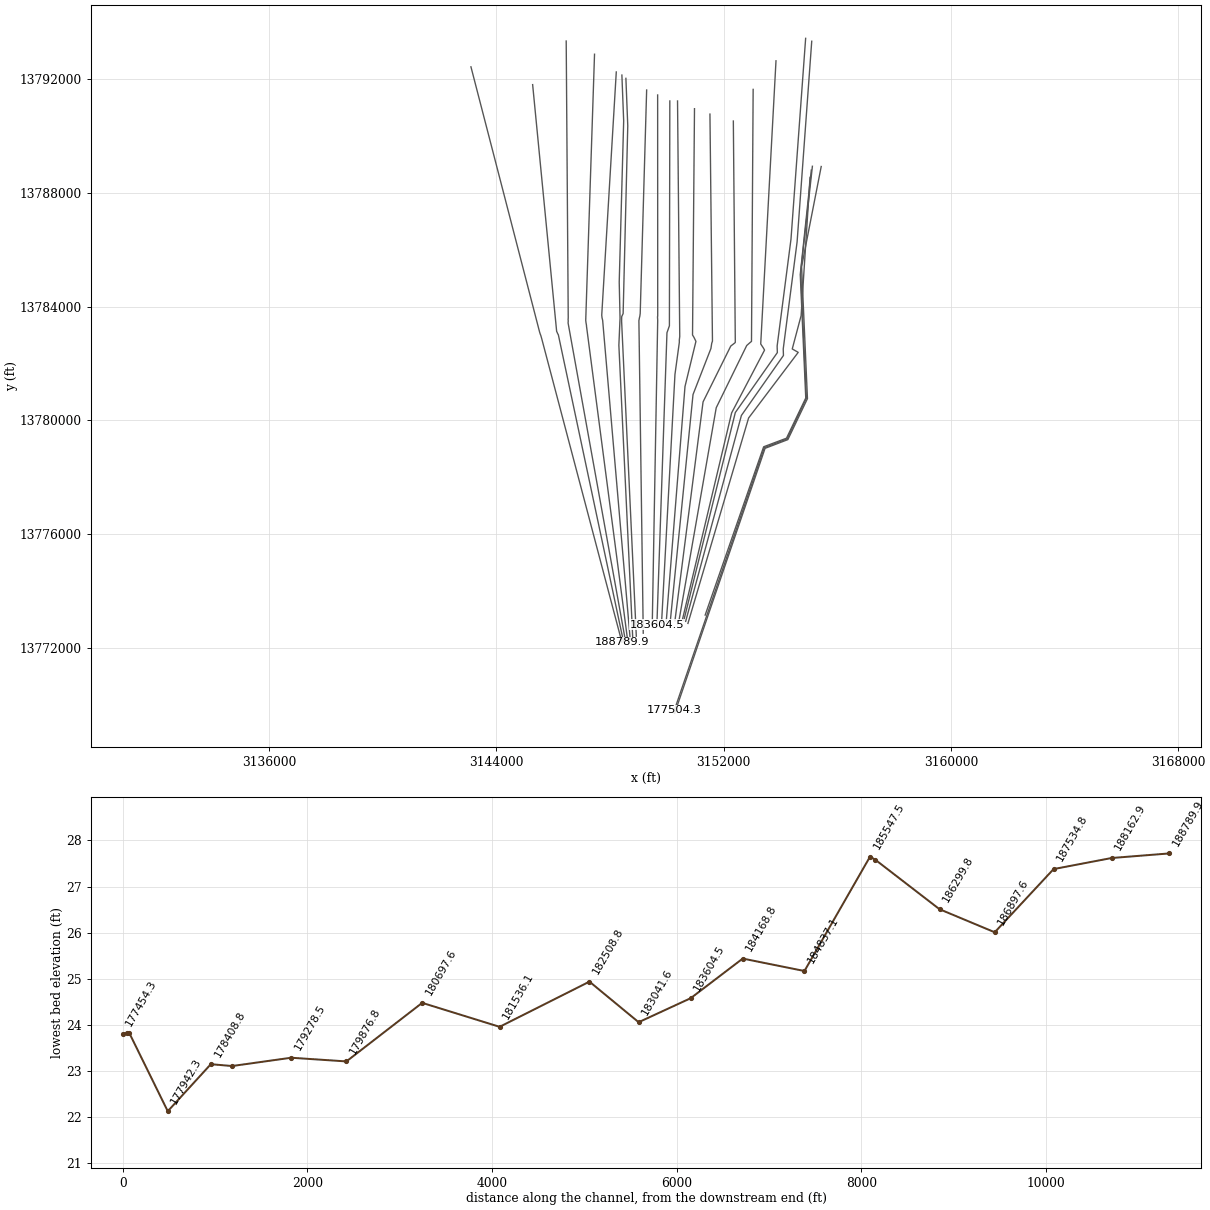
HEC-RAS study A100-00-00.prj: A100-00-00

--- A100-00-00.g01 (geometry) --- (continued)

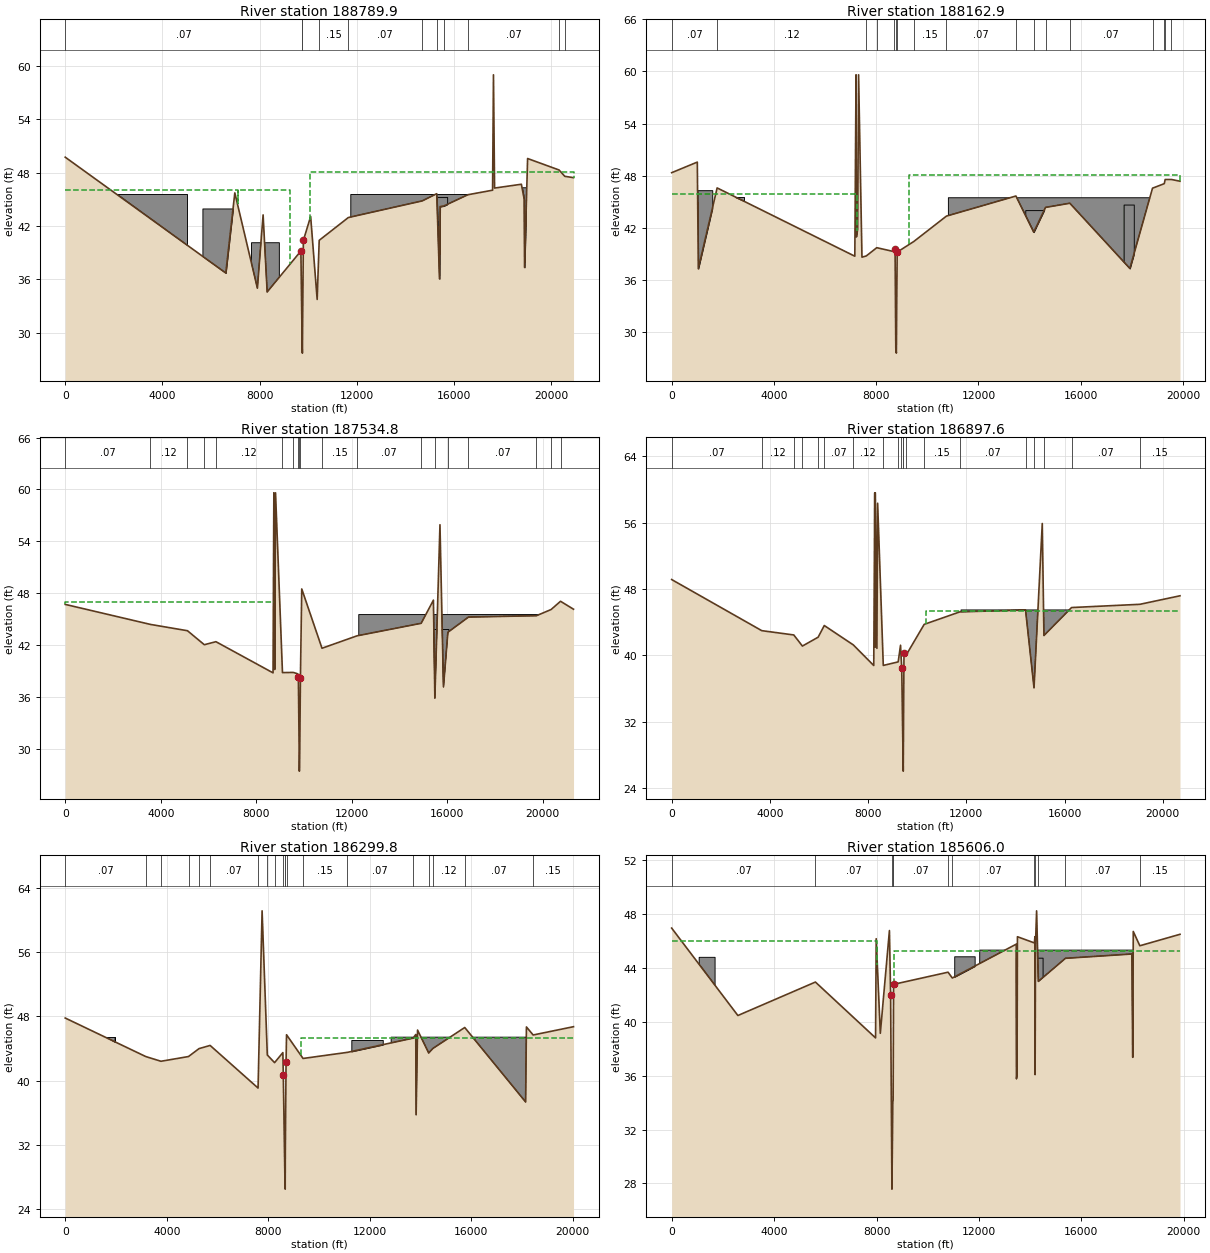
Type RM Length L Ch R = 1 ,188789.9,848.6,626.98,556.9
XS GIS Cut Line= 6
     3143110.892    13792439.395     3145526.858    13783105.933
     3145552.958    13783024.264     3145565.588    13782999.005
     3145600.949    13782875.238     3148421.789    13772197.515
#Sta/Elev= 30
       0   49.73 6611.16   36.72 6983.47   45.72 7912.42   35.02 8147.69   43.25
 8314.83   34.59 9703.47   39.19 9758.13   28.25 9764.71   27.72 9805.57   40.38
10105.31   43.07 10373.3   33.7510457.46   40.3911656.77   42.9514700.28   44.82
15296.86   45.6315410.11   36.0715434.88   44.1815583.15   44.2416576.75   45.51
17595.56   46.0217631.97   58.9817677.67   46.2618780.63   46.6918897.42   45.01
18912.06   37.3519037.46   49.5820332.37   48.29 20568.7   47.5820928.43   47.43
#Mann= 11 ,-1 , 0
       0     .07       0 9758.13    .041       0 9764.71     .07       0
10457.46     .15       011656.77     .07       014700.28     .12       0
15296.86     .07       015583.15     .12       016576.75     .07       0
20332.37     .15       0 20568.7     .07       0
#XS Ineff= 3 ,-1
       0    7095      46    7095    9250      4610066.1620928.43   48.11
Permanent Ineff=
       F       F       F
#Block Obstruct= 6 ,-1
  308.68 4994.14   45.55 5648.85  7022.9   43.97 7671.76 8816.79   40.12
11757.9519998.78   45.54 15114.515725.19   45.2518587.7918969.46   46.35
Bank Sta=9703.47,9805.57
XS Rating Curve= 0
Exp/Cntr=.5,.3

Type RM Length L Ch R = 1 ,188162.9,534.85,628.03,389.55
XS GIS Cut Line= 6
     3145281.404    13791813.388     3146126.326    13783130.349
     3146144.007    13783096.671     3146157.479    13783061.309
     3146186.105    13783010.792     3148476.245    13772224.365
#Sta/Elev= 30
       0   48.36 1002.95   49.58 1041.57   37.33 1778.54   46.61 7164.52   38.76
 7212.31   59.61 7227.46   40.97 7276.57   41.85 7311.47   59.61 7443.86   38.65
 7612.22   38.79 8023.56   39.74 8696.38   39.29 8738.94   39.57 8767.66    28.2
  8789.5   27.62 8802.54   32.72 8821.79   39.23 9475.32   40.46 10748.4   43.37
13466.99   45.6814163.82   41.5214625.29   44.37 15575.2   44.8517923.87   37.35
18809.73   46.5819270.08    47.119305.19   47.5819550.65   47.5819884.88   47.38
#Mann= 17 ,-1 , 0
       0     .07       0 1778.54     .12       0 7612.22     .07       0
 8023.56     .12       0 8696.38     .07       0 8767.66    .041       0
 8802.54     .07       0 9475.32     .15       0 10748.4     .07       0
13466.99     .12       014163.82     .07       014625.29     .12       0
 15575.2     .07       018809.73     .15       019270.08     .07       0
19305.19     .15       019550.65     .07       0
#XS Ineff= 2 ,-1
       0 7267.18    45.9 9303.3419884.88   48.08
Permanent Ineff=
       F       F
#Block Obstruct= 5 ,-1
  854.96 1587.79   46.35 1759.81 2826.28    45.6 10824.919311.32   45.48
13832.0614870.23   44.0617679.3918076.34    44.7
Bank Sta=8738.94,8821.79
XS Rating Curve= 0
Exp/Cntr=.5,.3

Type RM Length L Ch R = 1 ,187534.8,654.21,637.23,591.55
XS GIS Cut Line= 6
     3146462.298    13793347.087      3146533.83    13783600.158
     3146528.779     13783558.06      3146533.83     13783497.44
     3146528.779      13783428.4     3148547.428    13772240.061
#Sta/Elev= 30
       0   46.69 3570.35   44.37 5120.39   43.64 5826.07   42.02 6311.56   42.37
 8704.28   38.76 8738.54   59.61 8773.12   39.15 8808.35   59.61 9099.11   38.79
 9554.58   38.81  9734.3   38.65 9765.24   38.33 9806.21   27.38 9824.35   29.75
 9850.65   38.11 9906.46   48.4810754.43   41.61 12223.1   43.0514908.11    44.5
15420.94   47.1815481.08   35.8515695.17   55.9115841.81   37.1416025.89   43.46
16889.43   45.2219734.76   45.38 20346.7   46.0920744.36   47.0521288.71   46.13
#Mann= 19 ,-1 , 0
       0     .07       0 3570.35     .12       0 5120.39     .07       0
 5826.07     .15       0 6311.56     .12       0 9099.11     .07       0
 9554.58     .12       0  9734.3     .07       0 9806.21    .041       0
 9824.35     .07       010754.43     .15       0 12223.1     .07       0
14908.11     .12       015481.08     .07       016025.89     .12       0
16889.43     .07       019734.76     .15       0 20346.7     .07       0
20744.36     .15       0
#XS Ineff= 2 , 0
       0 8740.46      47               0
Permanent Ineff=
       F       F
#Block Obstruct= 3 ,-1
12294.4621464.04   45.5115343.51 16068.7   43.7819122.1419580.15   45.25
Bank Sta=9765.24,9850.65
XS Rating Curve= 0
Exp/Cntr=.5,.3

Type RM Length L Ch R = 1 ,186897.6,583.35,597.82,564.74
XS GIS Cut Line= 6
     3147458.768    13792883.182     3147149.296    13783521.856
     3147158.557    13783439.345     3147175.396    13783345.889
     3147176.238     13783316.42     3148621.146    13772282.325
#Sta/Elev= 30
       0   49.14 3668.68   42.97 4973.32   42.45 5324.62   41.11 5965.26   42.18
  6215.4   43.59 7397.19   41.25 8230.38   38.76 8270.34   59.61 8282.88   40.97
 8295.12   59.61    8358   40.84 8388.41   58.35 8618.18   38.77 9225.43    39.2
 9320.21   41.21 9369.58   38.41 9431.28   26.01    9440   30.37 9461.65   40.22
 9543.06   39.9910284.96   43.7311740.16   45.2414412.23   45.4614757.16   36.07
15093.29   55.9115160.71   42.3816286.26   45.7619069.45   46.1520702.44   47.18
#Mann= 20 ,-1 , 0
       0     .07       0 3668.68     .12       0 4973.32     .07       0
 5324.62     .15       0 5965.26     .12       0  6215.4     .07       0
 7397.19     .12       0 8618.18     .07       0 9225.43     .12       0
 9320.21     .07       0 9431.28    .041       0    9440     .12       0
 9543.06     .07       010284.96     .15       011740.16     .07       0
14412.23     .12       014757.16     .07       015160.71     .12       0
16286.26     .07       019069.45     .15       0
#XS Ineff= 2 ,-1
       0 8320.61      4710357.2220702.44    45.3
Permanent Ineff=
       F       F
#Block Obstruct= 2 ,-1
 1185.45 1855.55   45.9411783.9721262.53   45.47
Bank Sta=9369.58,9461.65
XS Rating Curve= 0
Exp/Cntr=.5,.3

Type RM Length L Ch R = 1 ,186299.8,565.83,693.75,502.33
XS GIS Cut Line= 6
     3148224.197    13792258.855     3147712.561    13783702.876
     3147723.506    13783606.051     3147742.871    13783530.276
     3147745.397    13783509.227     3148714.502    13772288.791
#Sta/Elev= 30
       0   47.79 3172.15      43 3773.23   42.41 4858.47      43 5271.13   43.98
 5709.99   44.38 7599.32   39.08 7758.32   61.12 7963.99   43.19  8250.2   42.24
 8576.87   43.49 8593.84   40.65 8660.57   27.17 8668.86   26.51 8672.88   30.83
 8703.03   42.36 8721.06   45.71 9372.53   42.7611122.25   43.5213710.45   45.29
13813.88   45.7413827.42   35.7613884.04   46.2914323.79   43.44   14487      44
15743.41   46.6118142.37   37.35 18174.2   46.6818439.52   45.6820030.37   46.71
#Mann= 20 ,-1 , 0
       0     .07       0 3172.15     .12       0 3773.23     .07       0
 4858.47     .15       0 5271.13     .12       0 5709.99     .07       0
 7599.32     .12       0 7963.99     .07       0  8250.2     .12       0
 8576.87     .07       0 8660.57    .041       0 8672.88     .12       0
 8721.06     .07       0 9372.53     .15       011122.25     .07       0
13710.45     .12       014323.79     .07       0   14487     .12       0
15743.41     .07       018439.52     .15       0
#XS Ineff= 2 ,-1
       0 7824.43      47 9283.6820030.37    45.3
Permanent Ineff=
       F       F
#Block Obstruct= 5 ,-1
   60.67  366.83   45.91  797.55 1954.55   45.39 1946.48 1959.64   45.39
 11274.812512.08   45.0612844.2620338.36   45.41
Bank Sta=8593.84,8703.03
XS Rating Curve= 0
Exp/Cntr=.5,.3

Type RM Length L Ch R = 1 ,185606.0,170.49,58.58,134.64
XS GIS Cut Line= 6
     3148421.493    13792149.411     3148484.108    13790533.966
     3148327.572    13784867.383     3148356.535    13783595.409
     3148315.049     13782644.58      3148803.44    13772332.026
#Sta/Elev= 30
       0   46.93 2585.36   40.45  5612.8   42.93 7961.84   38.79 7986.53   46.14
 8147.44   39.13 8503.37   46.75 8549.32      42 8600.84   27.58 8635.71   34.04
 8647.77   34.17 8665.09   42.7610792.11   43.6610959.82   43.2313455.48   45.74
 13463.8   35.7613486.46   36.0713501.65   46.2914164.34   45.8314184.68   46.29
14191.89   36.0714208.86   45.8714250.39   48.2114319.88   42.9815377.53   44.69
 17971.5   45.0118004.16   37.3518025.16   46.68 18281.5   45.6219849.82   46.47
#Mann= 12 ,-1 , 0
       0     .07       0  5612.8     .07       0 8600.84    .041       0
 8635.71     .12       0 8647.77     .07       010792.11     .15       0
10959.82     .07       014164.34     .12       014184.68     .07       0
14319.88     .12       015377.53     .07       0 18281.5     .15       0
#XS Ineff= 2 ,-1
       0 8030.53      46 8668.4219849.82    45.2
Permanent Ineff=
       F       F
#Block Obstruct= 4 ,-1
 1054.69 1675.42    44.811033.3511831.15   44.8412029.1119925.14    45.3
13129.7714503.82    44.7
Bank Sta=8549.32,8665.09
XS Rating Curve= 0
Exp/Cntr=.5,.3

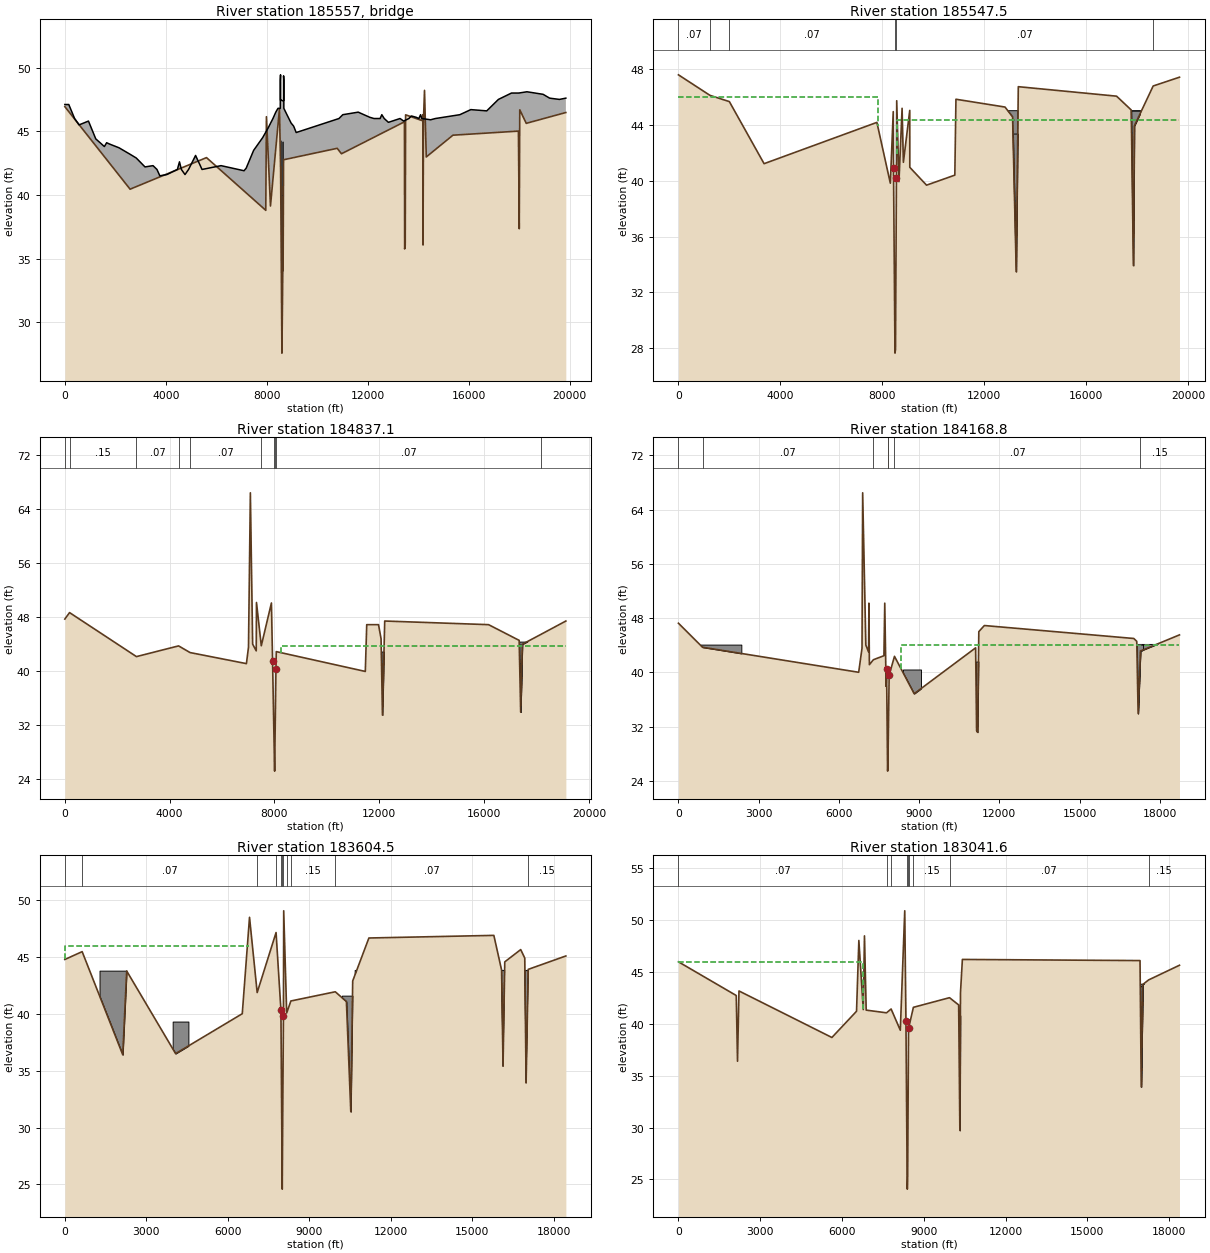
Type RM Length L Ch R = 3 ,185557  ,,,
BEGIN DESCRIPTION:
SH35
END DESCRIPTION:
Bridge Culvert--1,0,-1,-1, 0
Deck Dist Width WeirC Skew NumUp NumDn MinLoCord MaxHiCord MaxSubmerge Is_Ogee
5,48,2.6,0, 78, 78, , , .95, 0, 0,0,,
       0     156     387     564     936    1226    1566    1656    1766    2149
    2579    2829    3176    3494    3650    3765    4041    4459    4542    4618
    4761    4902    5180    5436    6189    7100    7184    7480    7838    8055
    8245    8355    8445    8536    8537    8546    8547    8575    8606    8636
    8666    8667    8676    8677    8773    8966    9066    9166   10861   11012
   11624   12077   12248   12492   12559   12654   12820   13280   13424   13632
   13729   13914   14026   14095   14144   14493   14680   15649   16086   16716
   17178   17696   17985   18310   18949   19208   19594   19851
    47.1    47.1      46    45.5    45.8    44.4    43.8    44.1      44    43.7
    43.2    42.9    42.2    42.3      42    41.5    41.6      42    42.6      42
    41.6      42    43.1      42    42.3    41.9    42.1    43.5    44.5   45.26
      46   46.49    46.8    46.8      49   49.43   47.44   47.44   47.41   47.39
    47.4   49.35      49    46.8   46.41   45.64    45.4    44.9      46    46.3
    46.5    46.1      46      46    46.3      46    45.7      46    45.8      46
    46.2    46.1      46    46.3      46    45.9      46    46.3    46.7    46.6
    47.5      48      48    48.1    47.9    47.6    47.5    47.6
                                                                                
                                                                                
                                                                                
                                                    44.4   44.28   44.22   44.21
   44.22
                                                                                
                                                                                
                                                                
       0      43     274     451     823    1113    1453    1543    1653    2036
    2466    2716    3063    3381    3537    3652    3928    4346    4429    4505
    4648    4789    5067    5323    6076    6987    7071    7367    7725    7942
    8132    8242    8332    8423    8424    8433    8434    8462    8493    8523
    8553    8554    8563    8564    8660    8853    8953    9053   10748   10899
   11511   11964   12135   12379   12446   12541   12707   13167   13311   13519
   13616   13801   13913   13982   14031   14380   14567   15536   15973   16603
   17065   17583   17872   18197   18836   19095   19481   19738
    47.1    47.1      46    45.5    45.8    44.4    43.8    44.1      44    43.7
    43.2    42.9    42.2    42.3      42    41.5    41.6      42    42.6      42
    41.6      42    43.1      42    42.3    41.9    42.1    43.5    44.5   45.26
      46   46.49    46.8    46.8      49   49.43   47.44   47.44   47.41   47.39
    47.4   49.35      49    46.8   46.41   45.64    45.4    44.9      46    46.3
    46.5    46.1      46      46    46.3      46    45.7      46    45.8      46
    46.2    46.1      46    46.3      46    45.9      46    46.3    46.7    46.6
    47.5      48      48    48.1    47.9    47.6    47.5    47.6
                                                                                
                                                                                
                                                                                
                                                    44.4   44.28   44.22   44.21
   44.22
                                                                                
                                                                                
                                                                
Pier Skew, UpSta & Num, DnSta & Num=  ,8575, 2 ,8462, 2 , 0 , 0 , 0 ,,
    1.33    1.33
       0      46
    1.33    1.33
       0      46
Pier Skew, UpSta & Num, DnSta & Num=  ,8606, 2 ,8493, 2 , 0 , 0 , 0 ,,
    1.33    1.33
       0      46
    1.33    1.33
       0      46
Pier Skew, UpSta & Num, DnSta & Num=  ,8636, 2 ,8523, 2 , 0 , 0 , 0 ,,
    1.33    1.33
       0      46
    1.33    1.33
       0      46
BR Coef=-1 , 1 , 1 ,1.25, 0 ,,,.8,-1,2,0,
WSPro=,,,, 1 ,,,, 0 ,,,, 0 ,,,,-1 ,-1 ,-1 , 0 , 0 , 0 , 0 , 0
BC Design=,, 0 ,, 0 ,,,,,,
BC HTab HWMax=49.26

Type RM Length L Ch R = 1 ,185547.5,616.45,710.41,601.34
XS GIS Cut Line= 6
     3148562.507    13792034.153      3148628.12    13790364.907
     3148465.323    13783759.112      3148414.71    13783650.626
     3148411.752    13783488.919     3148928.668    13772407.163
#Sta/Elev= 30
       0    47.6 1235.21   46.13  1997.4   45.68 3359.56   41.23 7785.06   44.19
 8312.71   39.83 8427.08   44.96 8437.13   40.93 8495.19   27.65 8515.92   27.91
 8551.89   40.21 8562.98   45.74 8651.14   39.94 8773.79    45.2 8824.96   41.33
 9074.61   45.05 9076.31   40.97 9733.45   39.6910843.07   40.41 10886.9   45.85
12811.77   45.2913109.03   44.59   13252   33.4913333.17   46.7517189.02   46.07
17764.06   45.0817849.79   33.9317887.32   43.9418624.85    46.819656.49   47.43
#Mann= 6 ,-1 , 0
       0     .07       0 1235.21     .15       0  1997.4     .07       0
 8495.19    .041       0 8515.92     .07       018624.85     .15       0
#XS Ineff= 2 ,-1
       0 7816.79      46 8555.2919656.49   44.35
Permanent Ineff=
       F       F
#Block Obstruct= 4 ,-1
 1463.16 1991.69   45.3210888.2618768.22   45.03 12977.113557.25   43.39
17618.3218106.87   45.03
Bank Sta=8437.13,8551.89
XS Rating Curve= 0
Exp/Cntr=.5,.3

Type RM Length L Ch R = 1 ,184837.1,600.29,668.23,700.97
XS GIS Cut Line= 6
     3149292.538    13791623.551     3149065.948    13783764.312
     3149051.958    13783662.385     3149039.967    13783618.417
     3149019.981    13783510.495     3149172.863    13772513.607
#Sta/Elev= 30
       0   47.73  179.99   48.69 2732.33   42.16 4339.57   43.75 4778.72   42.76
 6928.94   41.12 7007.85   43.56 7079.57   66.46 7166.26   44.02 7303.36   43.01
 7312.96   50.19 7496.48   43.77 7883.17   50.12 7926.98   41.48  7991.2   27.91
  8005.5   25.17 8055.66   40.25 8068.48    42.911465.88   39.9611519.95    46.9
   11970    46.912067.12    44.812119.79   33.4912206.46   47.44 16170.4    46.9
17336.16   44.5717394.56   33.9317456.41   43.9918153.47   45.4319118.72   47.44
#Mann= 10 ,-1 , 0
       0     .07       0  179.99     .15       0 2732.33     .07       0
 4339.57     .15       0 4778.72     .07       0 7496.48     .12       0
  7991.2    .041       0  8005.5     .12       0 8068.48     .07       0
18153.47     .15       0
#XS Ineff= 2 ,-1
       0 7083.97      46 8262.1619118.72    43.7
Permanent Ineff=
       F       F
#Block Obstruct= 7 ,-1
   435.9  703.11   45.26   689.3 1065.98   44.83 1058.34 1580.19   44.82
 1547.91 1680.86   44.38   1200012335.88   42.9112210.0419008.34   44.39
 17068.717770.99   43.95
Bank Sta=7926.98,8055.66
XS Rating Curve= 0
Exp/Cntr=.5,.3

Type RM Length L Ch R = 1 ,184168.8,439.43,564.29,415.34
XS GIS Cut Line= 6
     3149679.334    13791448.581     3149681.504    13783666.383
     3149675.509    13783654.391     3149675.509    13783620.416
     3149681.504    13783522.486     3149488.033    13772717.552
#Sta/Elev= 30
       0   47.24  900.25    43.7 6739.54   40.01 6863.96   43.56  6888.2   66.46
 7007.04   44.02 7109.55   43.01 7122.22   50.19 7139.54   41.13 7289.54   41.86
 7683.07   42.45 7714.52   50.19 7764.78   37.94 7782.27   40.42 7819.98   25.44
 7825.19   25.49 7844.65   29.77 7878.66   39.58 8077.88   42.36 8814.37   36.85
11112.09   43.6111148.82   31.3911185.68   31.16 11231.7      4611439.47    46.9
17026.23   44.9917137.57   44.5717188.88   33.9317276.27   43.15 18734.7   45.52
#Mann= 7 ,-1 , 0
       0     .15       0  900.25     .07       0 7289.54     .12       0
 7825.19    .041       0 7844.65     .12       0 8077.88     .07       0
17276.27     .15       0
#XS Ineff= 2 ,-1
       0 6870.23      46 8321.95 18734.7      44
Permanent Ineff=
       F       F
#Block Obstruct= 5 ,-1
  832.18 2351.55   44.09 8396.95  9068.7   40.4210992.3711297.71    41.6
 11294.418989.16   44.1917007.6317374.04   44.08
Bank Sta=7782.27,7878.66
XS Rating Curve= 0
Exp/Cntr=.5,.3

Type RM Length L Ch R = 1 ,183604.5,351.94,562.95,559.32
XS GIS Cut Line= 6
      3150107.79    13791238.216     3150093.207    13783328.626
     3150059.232    13783232.695     3150045.242    13783190.726
     3150007.269    13783084.802     3149652.824    13772811.719
#Sta/Elev= 30
       0   44.78   637.4   45.47 2132.49    36.4    2277   43.77 4078.61    36.5
 6532.82   40.01 6799.78   48.49 7081.86   41.87 7777.24   47.15 7956.17   40.33
 8004.18   24.58 8022.34   30.84 8048.36   39.79 8058.39   49.06 8168.14   40.07
 8322.51   41.13 9957.58   41.94 10366.9   41.0810529.06   31.3910598.86   42.89
11195.27   46.6715795.83    46.916081.01   43.8516134.06    35.416197.92   44.57
16784.91   45.6516934.57    44.916983.07   33.9317061.56   43.9118447.32   45.09
#Mann= 11 ,-1 , 0
       0     .15       0   637.4     .07       0 7081.86     .12       0
 7777.24     .07       0 7956.17     .12       0 8004.18    .041       0
 8022.34     .12       0 8168.14     .07       0 8322.51     .15       0
 9957.58     .07       017061.56     .15       0
#XS Ineff= 2 , 0
       0 6778.63      46               0
Permanent Ineff=
       F       F
#Block Obstruct= 5 ,-1
 1276.87 2273.45    43.8 3969.47 4549.62   39.3210198.4710625.95    41.6
10689.3118671.08   43.82   1600017129.77    43.8
Bank Sta=7956.17,8048.36
XS Rating Curve= 0
Exp/Cntr=.3,.1

Type RM Length L Ch R = 1 ,183041.6,499.06,532.77,549.52
XS GIS Cut Line= 6
     3150379.061    13791238.216     3150456.945    13782952.897
     3150440.956    13782818.994     3150442.955    13782751.043
      3150288.45    13781616.306     3149817.616    13772882.344
#Sta/Elev= 30
       0   45.99 2120.33   42.74 2166.85    36.4 2220.33   43.18 5629.26   38.69
  6533.1   41.22 6618.35   48.05 6779.89   41.38 6824.42   48.49 6887.36   41.33
 7633.15   41.07 7801.55   41.44 8139.31   39.39 8301.74   50.91 8345.88   40.26
 8381.12   28.19 8395.48   24.06 8409.52   25.35 8440.85   39.56 8618.95    41.6
 9944.18   42.5310279.58   41.8310323.95   29.7210346.65   43.0210416.52   46.22
16933.08   46.1116977.38   33.9317035.01    43.817245.28   44.2418380.37   45.66
#Mann= 9 ,-1 , 0
       0     .07       0 7633.15     .07       0 7801.55     .12       0
 8381.12    .041       0 8409.52     .12       0 8440.85     .07       0
 8618.95     .15       0 9944.18     .07       017245.28     .15       0
#XS Ineff= 2 , 0
       0 6778.63      46               0
Permanent Ineff=
       F       F
#Block Obstruct= 3 ,-1
10229.0110381.68    40.810396.96 18758.1   43.8816702.2917496.18   43.64
Bank Sta=8345.88,8440.85
XS Rating Curve= 0
Exp/Cntr=.3,.1

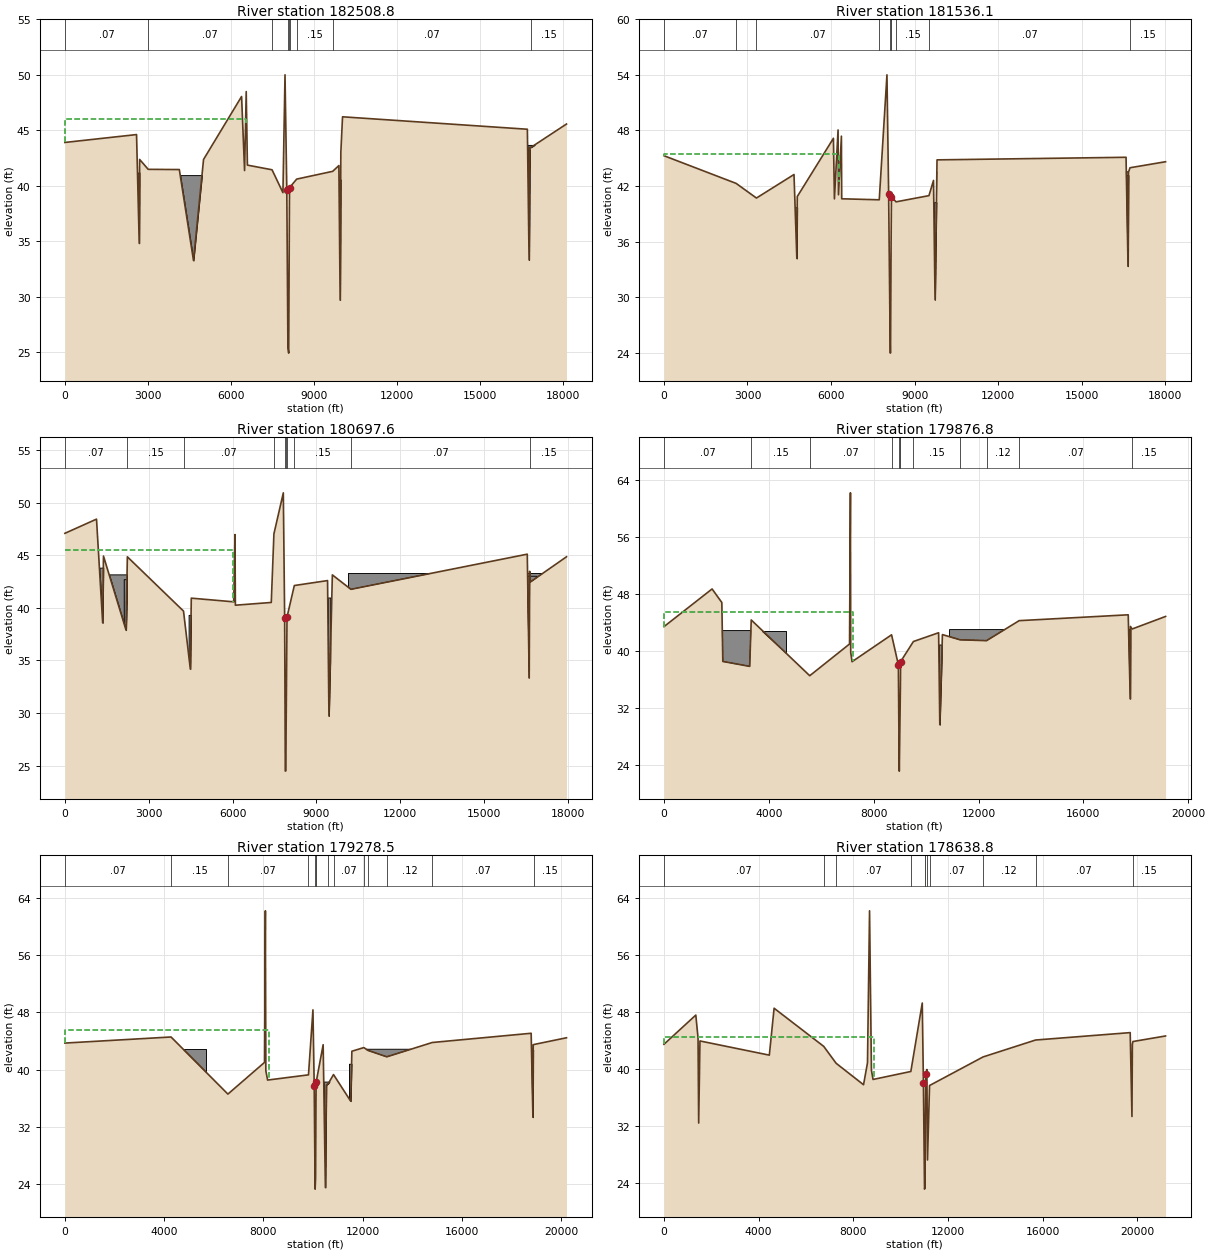
Type RM Length L Ch R = 1 ,182508.8,661.59,972.76,386.93
XS GIS Cut Line= 6
     3150975.858    13790966.945     3150906.621     13783004.86
     3150952.587    13782930.913     3151026.534    13782781.021
     3150641.575    13781192.555     3149982.408    13772929.427
#Sta/Elev= 30
       0   43.91 2592.21   44.62 2688.99   34.83 2704.13   42.38 3013.67   41.49
 4138.89   41.47 4652.31   33.28 5015.24   42.38 6391.12   48.05 6499.07   41.38
  6558.6   48.49  6601.1   41.87 7492.62   41.45  7886.5   39.39 7961.32      50
 8026.24   39.62 8066.55   25.44 8094.87   24.94 8124.08   39.84 8383.35   40.61
 9686.18   41.31 9909.38   41.83 9955.36   29.72 9980.48   43.0210041.61   46.22
16726.43    45.116788.53   33.3416807.76   43.4716863.99   43.4818140.96   45.57
#Mann= 9 ,-1 , 0
       0     .07       0 3013.67     .07       0 7492.62     .12       0
 8066.55    .041       0 8094.87     .12       0 8124.08     .07       0
 8383.35     .15       0 9686.18     .07       016863.99     .15       0
#XS Ineff= 2 , 0
       0 6534.35      46               0
Permanent Ineff=
       F       F
#Block Obstruct= 7 ,-1
  145.68 1337.15   43.67 1269.52 1841.84   43.54 2473.28 2778.63    41.2
 4030.53 5099.24   40.97 9648.8510076.34   40.5810043.2919051.49   43.69
16671.7616916.03   43.25
Bank Sta=8026.24,8124.08
XS Rating Curve= 0
Exp/Cntr=.3,.1

Type RM Length L Ch R = 1 ,181536.1,810.24,838.5,453.79
XS GIS Cut Line= 6
     3151519.379    13790776.322     3151608.115    13782789.015
     3151582.133     13782713.07     3151554.153    13782531.201
     3150924.075    13780910.055     3150123.658    13772929.427
#Sta/Elev= 30
       0   45.27 2592.63   42.28 3321.12    40.7 4669.83   43.24 4771.92   34.18
 4787.33   40.86 6085.62   47.15  6121.3   40.61 6252.31   48.05 6267.32   41.05
 6372.42   47.38 6383.17   40.62 7731.06   40.51 8007.85      54 8068.07   41.19
 8125.65   24.19 8129.21   23.96 8136.94   24.03  8156.6   36.04 8169.61   40.85
 8333.36   40.29 9516.25   40.96 9679.64    42.6  9735.4   29.72 9805.61   44.82
16593.64    45.116664.75   33.34 16679.9   43.4716735.15   43.9718012.46   44.62
#Mann= 10 ,-1 , 0
       0     .07       0 2592.63     .15       0 3321.12     .07       0
 7731.06     .12       0 8125.65    .041       0 8136.94     .12       0
  8156.6     .07       0 8333.36     .15       0 9516.25     .07       0
16735.15     .15       0
#XS Ineff= 2 , 0
       0 6290.08    45.5               0
Permanent Ineff=
       F       F
#Block Obstruct= 5 ,-1
  -30.39 1397.85   43.52 4580.15 4854.96    39.7 9374.05  9862.6   40.25
 9788.8218798.64   43.5316519.0816732.82   43.18
Bank Sta=8068.07,8169.61
XS Rating Curve= 0
Exp/Cntr=.3,.1

Type RM Length L Ch R = 1 ,180697.6,611.77,820.73,506.45
BEGIN DESCRIPTION:
Original TSARP section
END DESCRIPTION:
XS GIS Cut Line= 6
     3152342.461    13790532.716     3152411.535    13782745.047
     3152393.548    13782725.062      3152251.65    13782615.141
       3151277.2    13780651.097      3150288.45    13772952.969
#Sta/Elev= 30
       0   47.08 1132.26   48.43 1352.92   38.57 1381.16   44.92 2189.12   37.88
 2235.99   44.85 4245.49   39.69 4489.16   34.18 4523.43   40.92 6042.68   40.57
 6086.99   46.96 6101.22   40.25 7385.31   40.51  7480.2   47.03 7816.55   50.93
 7864.19   39.07 7883.82    26.9 7887.22   24.48 7904.26    24.5 7948.91   39.13
 8210.55   42.12 9399.49   42.59 9449.38   29.72 9570.85   43.1310235.47   41.76
16545.41    45.116615.04   33.3416631.13   43.4716657.66   42.4617948.65   44.85
#Mann= 10 ,-1 , 0
       0     .07       0 2235.99     .15       0 4245.49     .07       0
  7480.2     .12       0 7883.82    .041       0 7904.26     .12       0
 7948.91     .07       0 8210.55     .15       010235.47     .07       0
16657.66     .15       0
#XS Ineff= 2 , 0
       0 6015.27    45.5               0
Permanent Ineff=
       F       F
#Block Obstruct= 7 ,-1
 1190.84 1374.05   43.82 1501.11 2835.44   43.18 2106.87 2259.54   42.72
 4427.48 4671.76   39.33 9343.51 9496.18   40.9810146.8617771.36   43.26
16488.55 16885.5      43
Bank Sta=7864.19,7948.91
XS Rating Curve= 0
Exp/Cntr=.3,.1

Type RM Length L Ch R = 1 ,179876.8,452.63,598.33,576.11
BEGIN DESCRIPTION:
Revised Section (US Limit)
END DESCRIPTION:
XS GIS Cut Line= 6
     3153039.477    13791646.237     3152981.124    13782779.023
      3152931.16    13782739.051     3152813.245    13782635.126
     3151740.598    13780445.384       3150429.7    13772952.969
#Sta/Elev= 30
       0   43.44 1835.79   48.72 2207.77   46.82 2245.05   38.57  3270.3   37.88
 3328.93   44.38 5560.85   36.57 7078.98   41.01  7113.2   62.18 7123.97   39.83
 7174.13   38.53 8682.18    42.3 8941.49    38.1 8969.42    25.1 8975.67   23.21
 8991.37   27.13  9019.8   35.27 9026.27   38.54  9515.5   41.3610476.87   42.59
10522.27   29.7210621.45   42.3311295.51    41.612305.06   41.4813549.33   44.28
17709.07    45.117785.86   33.3417795.61   43.4717857.53   43.1119133.27   44.87
#Mann= 12 ,-1 , 0
       0     .07       0 3328.93     .15       0 5560.85     .07       0
 8682.18     .12       0 8969.42    .041       0 8991.37     .12       0
  9019.8     .07       0  9515.5     .15       011295.51     .07       0
12305.06     .12       013549.33     .07       017857.53     .15       0
#XS Ineff= 2 , 0
       0 7227.32    45.5               0
Permanent Ineff=
       T       F
#Block Obstruct= 4 ,-1
 2060.34 4657.76   42.8910351.1510595.42   40.9410893.6219283.55   43.03
17587.7917832.06   43.04
Bank Sta=8941.49,9026.27
XS Rating Curve= 0
Exp/Cntr=.3,.1

Type RM Length L Ch R = 1 ,179278.5,780.18,639.73,143.49
BEGIN DESCRIPTION:
Revised Section
END DESCRIPTION:
XS GIS Cut Line= 6
     3153843.243    13792651.466      3153305.89    13782688.588
     3153398.323    13782548.689     3153440.793    13782473.743
     3152282.739    13780264.671     3150547.408     13772976.51
#Sta/Elev= 30
       0    43.7 4279.97   44.55 6570.53   36.57 8050.28   41.01 8081.54   62.18
 8099.86   39.83  8170.9   38.53 9818.99   39.26 9998.69   48.3410049.94   37.64
 10086.1   23.2910105.58   24.8910122.13   36.0510127.34   38.2110410.01   43.47
10500.58   23.5210538.81   37.8310625.17   38.0810827.22    39.311520.78   35.58
11567.64   42.5612050.59   43.0712213.06   42.6812975.67   41.7814807.21   43.78
18794.05   45.0718864.62   33.3418876.36   43.4718906.06    43.520217.41   44.44
#Mann= 14 ,-1 , 0
       0     .07       0 4279.97     .15       0 6570.53     .07       0
 9818.99     .12       0 10086.1    .041       010105.58     .12       0
10122.13     .07       010625.17     .12       010827.22     .07       0
12050.59     .15       012213.06     .07       012975.67     .12       0
14807.21     .07       018906.06     .15       0
#XS Ineff= 2 , 0
       0  8225.6    45.5               0
Permanent Ineff=
       F       F
#Block Obstruct= 5 ,-1
 -111.02 5676.92   42.8610381.6810687.02   38.3211450.3811641.22   40.81
   1208121169.15   42.8418702.2918969.46   42.77
Bank Sta=10049.94,10127.34
XS Rating Curve= 0
Exp/Cntr=.3,.1

Type RM Length L Ch R = 1 ,178638.8,230,230,230
BEGIN DESCRIPTION:
Added Section
END DESCRIPTION:
XS GIS Cut Line= 6
      3154886.25     13793441.97     3154370.937     13786379.13
     3153883.334     13782615.26     3153890.828     13782385.42
     3152411.609     13780275.86        3150599.       13772960.
#Sta/Elev= 30
       0   43.42 1345.53   47.52  1440.4   44.32 1466.69   32.38 1521.53   43.89
 4451.47    41.9 4653.06   48.48  6749.6   43.13  7273.4   40.76 8431.25   37.75
 8598.26   40.83 8684.99   62.14 8764.38   39.79 8832.58   38.4910429.54   39.61
10911.81   49.2110960.61   38.0411007.75   23.1111027.19   23.3511057.94   39.23
 11106.4   39.8911133.11    27.211219.49   37.6413481.46   41.6515697.18   44.02
19695.99   45.0619770.15    33.319787.65   43.4319811.99   43.8121190.04   44.59
#Mann= 11 ,-1 , 0
       0     .07       0  6749.6     .15       0  7273.4     .07       0
10429.54     .12       011007.75    .041       011027.19     .07       0
11133.11     .12       011219.49     .07       013481.46     .12       0
15697.18     .07       019811.99     .15       0
#XS Ineff= 2 , 0
       0 8886.92    44.5               0
Permanent Ineff=
       F       F
Bank Sta=10960.61,11057.94
XS Rating Curve= 0
Exp/Cntr=.3,.1

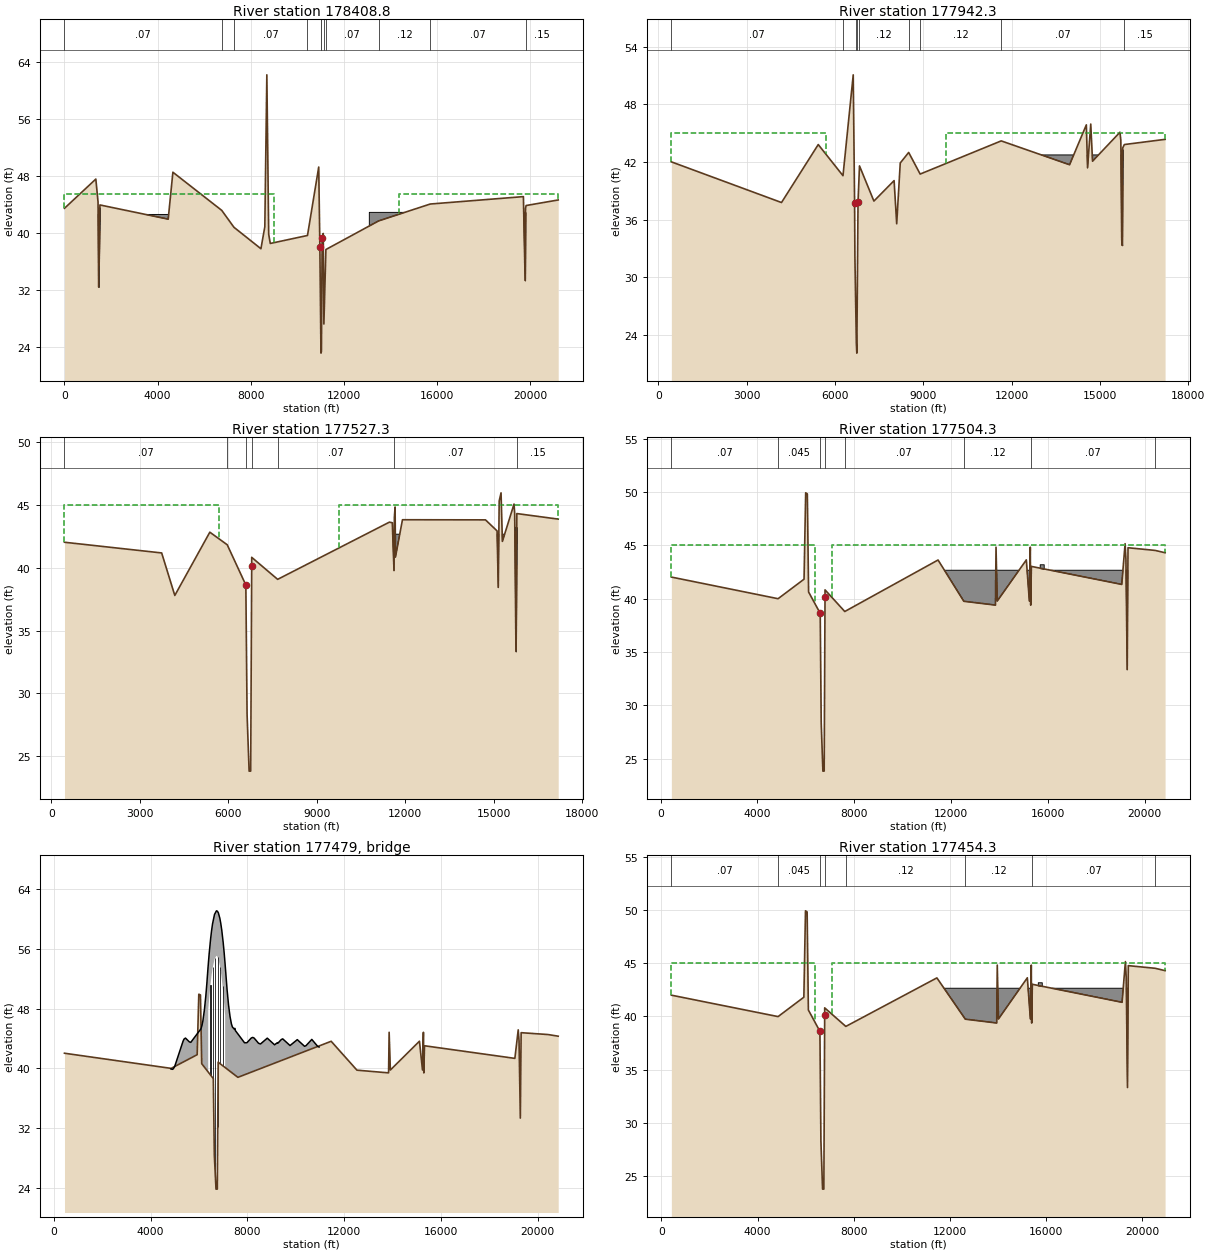
Type RM Length L Ch R = 1 ,178408.8,400,466.43,265.8
BEGIN DESCRIPTION:
Revised Section
END DESCRIPTION:
XS GIS Cut Line= 6
     3155100.741    13793340.426     3154585.422    13786277.591
     3154097.819    13782513.714     3154105.313     13782283.88
     3152626.094    13780174.314     3150665.116    13772929.427
#Sta/Elev= 30
       0   43.46 1345.53   47.56  1440.4   44.36 1466.69   32.42 1521.53   43.93
 4451.47   41.94 4653.06   48.52  6749.6   43.17  7273.4    40.8 8431.25   37.79
 8598.26   40.87 8684.99   62.18 8764.38   39.83 8832.58   38.5310429.54   39.65
10911.81   49.2510960.61   38.0811007.75   23.1511027.19   23.3911057.94   39.27
 11106.4   39.9311133.11   27.2411219.49   37.6813481.46   41.6915697.18   44.06
19695.99    45.119770.15   33.3419787.65   43.4719811.99   43.8521190.04   44.63
#Mann= 11 ,-1 , 0
       0     .07       0  6749.6     .15       0  7273.4     .07       0
10429.54     .12       011007.75    .041       011027.19     .07       0
11133.11     .12       011219.49     .07       013481.46     .12       0
15697.18     .07       019811.99     .15       0
#XS Ineff= 2 , 0
       0    9007    45.5   14337       0    45.5
Permanent Ineff=
       F       F
#Block Obstruct= 5 ,-1
 -388.67 4878.72    42.6 1297.71 1526.72   43.56 5877.86 6793.89   42.64
13083.4121735.55   42.8919541.9820305.34   42.91
Bank Sta=10960.61,11057.94
XS Rating Curve= 0
Exp/Cntr=.5,.3

Type RM Length L Ch R = 1 ,177942.3,320,415,415
BEGIN DESCRIPTION:
Revised Section
END DESCRIPTION:
XS GIS Cut Line= 6
 3155040.494043513788550.6948728     3154727.072     13783687.04
      3154415.09     13782513.71     3154624.938      13782393.8
     3152879.093     13780083.96 3150744.978412713772857.4419458
#Sta/Elev= 30
  444.36   42.02  4185.5   37.79 5433.57   43.82 6273.89   40.58 6621.75   51.07
 6668.16    37.7  6678.5   32.13  6727.6   23.15 6743.51   22.13 6784.64   37.86
 6834.53    41.6 7323.97   37.94 8009.75   40.07 8097.95   35.58 8218.71    41.9
 8504.99      43 8894.58   40.7511648.01    44.213969.64   41.7214539.79   45.87
14580.51    41.414689.03   45.9514750.15   42.0915681.24    45.115710.55   44.27
 15741.1   33.9315757.51   33.34 15775.2   43.4715830.64   43.8217214.48   44.36
#Mann= 9 ,-1 , 0
  444.36     .07       0 6273.89     .12       0  6727.6    .041       0
 6743.51     .07       0 6834.53     .12       0 8504.99     .07       0
 8894.58     .12       011648.01     .07       015830.64     .15       0
#XS Ineff= 2 , 0
       0    5683      45    9763       0      45
Permanent Ineff=
       T       T
#Block Obstruct= 6 ,-1
                                                 5001.53 5276.34   39.63
                        11380.98 17850.9   42.7415664.1215829.01    43.3
Bank Sta=6668.16,6784.64
XS Rating Curve= 0
Exp/Cntr=.5,.3

Type RM Length L Ch R = 1 ,177527.3,23,23,23
BEGIN DESCRIPTION:
Added Section
END DESCRIPTION:
XS GIS Cut Line= 6
 3155085.372515413788806.9449424     3154696.655     13785131.84
     3154890.388     13780787.13     3154213.143     13779373.75
     3153408.794     13779071.81 3151351.316041113773150.5740203
#Sta/Elev= 30
  444.36   42.02 3740.13   41.17 4185.81   37.79 5373.54   42.82 5963.54   41.82
 6594.54   38.62 6636.54   28.32 6705.54   23.82 6758.54   23.82 6793.54   40.12
 6793.54   40.82 7673.18   39.0711463.98   43.6211561.71   43.5711618.88   39.77
 11631.6   44.0311656.14   44.8211668.31   40.8411905.72   43.8114721.13    43.8
15114.29   42.9215154.77   38.4315185.75    45.315248.69   45.9515294.64   42.09
 15689.5   45.0615711.72   44.2715754.88   33.3415784.83    44.317187.37   43.86
#Mann= 7 ,-1 , 0
  444.36     .07       0 5963.54     .12       0 6594.54    .041       0
 6793.54    .045       0 7673.18     .07       0 11631.6     .07       0
15784.83     .15       0
#XS Ineff= 2 , 0
       0    5683      45    9763       0      45
Permanent Ineff=
       T       T
#Block Obstruct= 6 ,-1
                                                 5001.53 5276.34   39.55
                        11380.98 17850.9   42.6615664.1215829.01   43.22
Bank Sta=6594.54,6793.54
XS Rating Curve= 0
Exp/Cntr=.5,.3

Type RM Length L Ch R = 1 ,177504.3,50,50,50
BEGIN DESCRIPTION:
Added Section (US face of US bridge)
END DESCRIPTION:
XS GIS Cut Line= 6
     3155124.012     13788941.36     3154711.305     13785211.66
     3154912.801      13780781.5     3154235.418       13779349.
     3153431.068     13779039.63 3150266.955125913769803.5223337
#Sta/Elev= 30
  444.36   42.02 4853.54   39.99 5926.54   41.82  5994.5   49.92 6062.54   49.82
 6114.54   40.62 6594.54   38.62 6636.54   28.32 6705.54   23.82 6758.54   23.82
 6793.54   40.12 6793.54   40.82 7609.54   38.7911463.98   43.6212528.81   39.75
13835.84   39.3913858.76   44.8213909.46   39.7715111.27   43.6315237.28   39.77
15275.14   44.8215292.08   39.3915319.14   43.0219054.19   41.33 19192.5   45.15
19226.75   43.6719279.49   33.3419312.68   44.7720431.66   44.5220844.98    44.3
#Mann= 8 ,-1 , 0
  444.36     .07       0 4853.54    .045       0 6594.54    .041       0
 6793.54    .045       0 7609.54     .07       012528.81     .12       0
15319.14     .07       020431.66     .15       0
#XS Ineff= 2 , 0
       0 6393.54      45    7073       0      45
Permanent Ineff=
       T       T
#Block Obstruct= 6 ,-1
                                                 5001.53 5276.34   39.55
                        11380.98   19791   42.6615664.1215829.01   43.22
Bank Sta=6594.54,6793.54
XS Rating Curve= 0
Exp/Cntr=.5,.3

Type RM Length L Ch R = 3 ,177479  ,,,
BEGIN DESCRIPTION:
Pearland Parkway (US bridge)
END DESCRIPTION:
Bridge Culvert--1,0,-1,-1, 0
Deck Dist Width WeirC Skew NumUp NumDn MinLoCord MaxHiCord MaxSubmerge Is_Ogee
14,35,2.6,0, 60, 60, , , .95, 0, 0,0,,
 4843.54 4903.54 4943.54 5003.54 5343.54 5383.54 5443.54 5603.54 5663.54 6083.54
 6123.54 6163.54 6223.54 6283.54 6323.54 6363.54 6383.54 6423.54 6483.54 6523.54
 6563.54 6643.54 6723.54 6763.54 6803.54 6863.54 6903.54 6943.54 7003.54 7043.54
 7083.54 7103.54 7163.54 7223.54 7283.54 7343.54 7383.54 7463.54 7483.54 7503.54
 7883.54 7983.54 8163.54 8223.54 8283.54 8463.54 8543.54 8823.54 9123.54 9243.54
 9263.54 9403.54 9463.54 9763.5410063.5410363.5410423.5410663.5410903.5410963.54
   39.92   39.86   39.94    40.3   43.63   43.91   44.05   43.54   43.48   45.29
   45.72   46.37   47.77   49.67   51.22   52.97   53.83   55.39   57.38   58.47
   59.37   60.61   61.09   61.04   60.81    60.1   59.39    58.5    56.8   55.43
   53.87   53.02   50.51   48.48   46.96   45.93   45.53   45.24   45.35   45.06
   43.42   43.43   44.06   44.14   44.04   43.35   43.26   44.04   43.15   43.44
   43.37   43.86   43.94   43.05   43.84   42.95   43.03   43.87   42.95   42.85
                                                                                
                                                   47.83   49.39   51.38   52.47
   53.37   54.61   55.09   54.95   54.62   53.77   52.97   51.98   50.14   48.67
   47.02
                                                                                
                                                                                
 4843.54 4903.54 4943.54 5003.54 5343.54 5383.54 5443.54 5603.54 5663.54 6083.54
 6123.54 6163.54 6223.54 6283.54 6323.54 6363.54 6383.54 6423.54 6483.54 6523.54
 6563.54 6643.54 6723.54 6763.54 6803.54 6863.54 6903.54 6943.54 7003.54 7043.54
 7083.54 7103.54 7163.54 7223.54 7283.54 7343.54 7383.54 7463.54 7483.54 7503.54
 7883.54 7983.54 8163.54 8223.54 8283.54 8463.54 8543.54 8823.54 9123.54 9243.54
 9263.54 9403.54 9463.54 9763.5410063.5410363.5410423.5410663.5410903.5410963.54
   39.92   39.86   39.94    40.3   43.63   43.91   44.05   43.54   43.48   45.29
   45.72   46.37   47.77   49.67   51.22   52.97   53.83   55.39   57.38   58.47
   59.37   60.61   61.09   61.04   60.81    60.1   59.39    58.5    56.8   55.43
   53.87   53.02   50.51   48.48   46.96   45.93   45.53   45.24   45.35   45.06
   43.42   43.43   44.06   44.14   44.04   43.35   43.26   44.04   43.15   43.44
   43.37   43.86   43.94   43.05   43.84   42.95   43.03   43.87   42.95   42.85
                                                                                
                                                   47.83   49.39   51.38   52.47
   53.37   54.61   55.09   54.95   54.62   53.77   52.97   51.98   50.14   48.67
   47.02
                                                                                
                                                                                
Pier Skew, UpSta & Num, DnSta & Num=  ,6476.28, 2 ,6476.28, 2 , 0 , 0 , 0 ,,
       3       3
       0    52.5
       3       3
       0    52.5
Pier Skew, UpSta & Num, DnSta & Num=  ,6576.28, 2 ,6576.28, 2 , 0 , 0 , 0 ,,
       3       3
       0      55
       3       3
       0      55
Pier Skew, UpSta & Num, DnSta & Num=  ,6676.28, 2 ,6676.28, 2 , 0 , 0 , 0 ,,
       3       3
       0    57.5
       3       3
       0    57.5
Pier Skew, UpSta & Num, DnSta & Num=  ,6776.28, 2 ,6776.28, 2 , 0 , 0 , 0 ,,
       3       3
       0      56
       3       3
       0      56
Pier Skew, UpSta & Num, DnSta & Num=  ,6876.28, 2 ,6876.28, 2 , 0 , 0 , 0 ,,
       3       3
       0      56
       3       3
       0      56
Pier Skew, UpSta & Num, DnSta & Num=  ,6976.28, 2 ,6976.28, 2 , 0 , 0 , 0 ,,
       3       3
       0      56
       3       3
       0      56
Abutment Skew #Up #Dn= , 4 , 4
  6383.3 6405.28  7056.6 7083.72
      48       0       0    47.2
  6383.3 6405.28  7056.6 7083.72
      48       0       0    47.2
BR Coef=-1 , 0 , 0 ,, 0 ,,,.8,-1,,0,
WSPro=,,,, 1 ,,,, 0 ,,,, 0 ,,,,-1 ,-1 ,-1 , 0 , 0 , 0 , 0 , 0
BC Design=,, 0 ,, 0 ,,,,,,
BC HTab HWMax=49.92

Type RM Length L Ch R = 1 ,177454.3,50,50,50
BEGIN DESCRIPTION:
Added Section between Two Bridges
END DESCRIPTION:
XS GIS Cut Line= 6
     3155434.278     13788932.81     3154743.892     13785406.35
     3154950.216      13780767.3     3154260.167     13779324.25
     3153458.292     13779017.36 3150277.063590113769692.5772813
#Sta/Elev= 30
  411.46      42 4853.54   39.99 5926.54   41.81  5994.5   49.91 6062.54   49.81
 6114.54   40.61 6594.54   38.61 6636.54   28.31 6705.54   23.81 6758.54   23.81
 6793.54   40.11 6793.54   40.81 7673.18   39.0711463.98   43.6212646.65   39.75
13953.68   39.39 13976.6   44.82 14027.3   39.7715229.11   43.6315355.12   39.77
15392.98   44.8215409.92   39.3915436.98   43.0219172.03   41.3319310.34   45.15
19344.59   43.6719397.33   33.3419430.52   44.77 20549.5   44.5220962.82    44.3
#Mann= 8 ,-1 , 0
  411.46     .07       0 4853.54    .045       0 6594.54    .041       0
 6793.54    .045       0 7673.18     .12       012646.65     .12       0
15436.98     .07       0 20549.5     .15       0
#XS Ineff= 2 , 0
       0 6393.54      45    7078       0      45
Permanent Ineff=
       T       T
#Block Obstruct= 6 ,-1
                                                 5001.53 5276.34   39.54
                        11380.98   19965   42.6515664.1215829.01   43.21
Bank Sta=6594.54,6793.54
XS Rating Curve= 0
Exp/Cntr=.5,.3