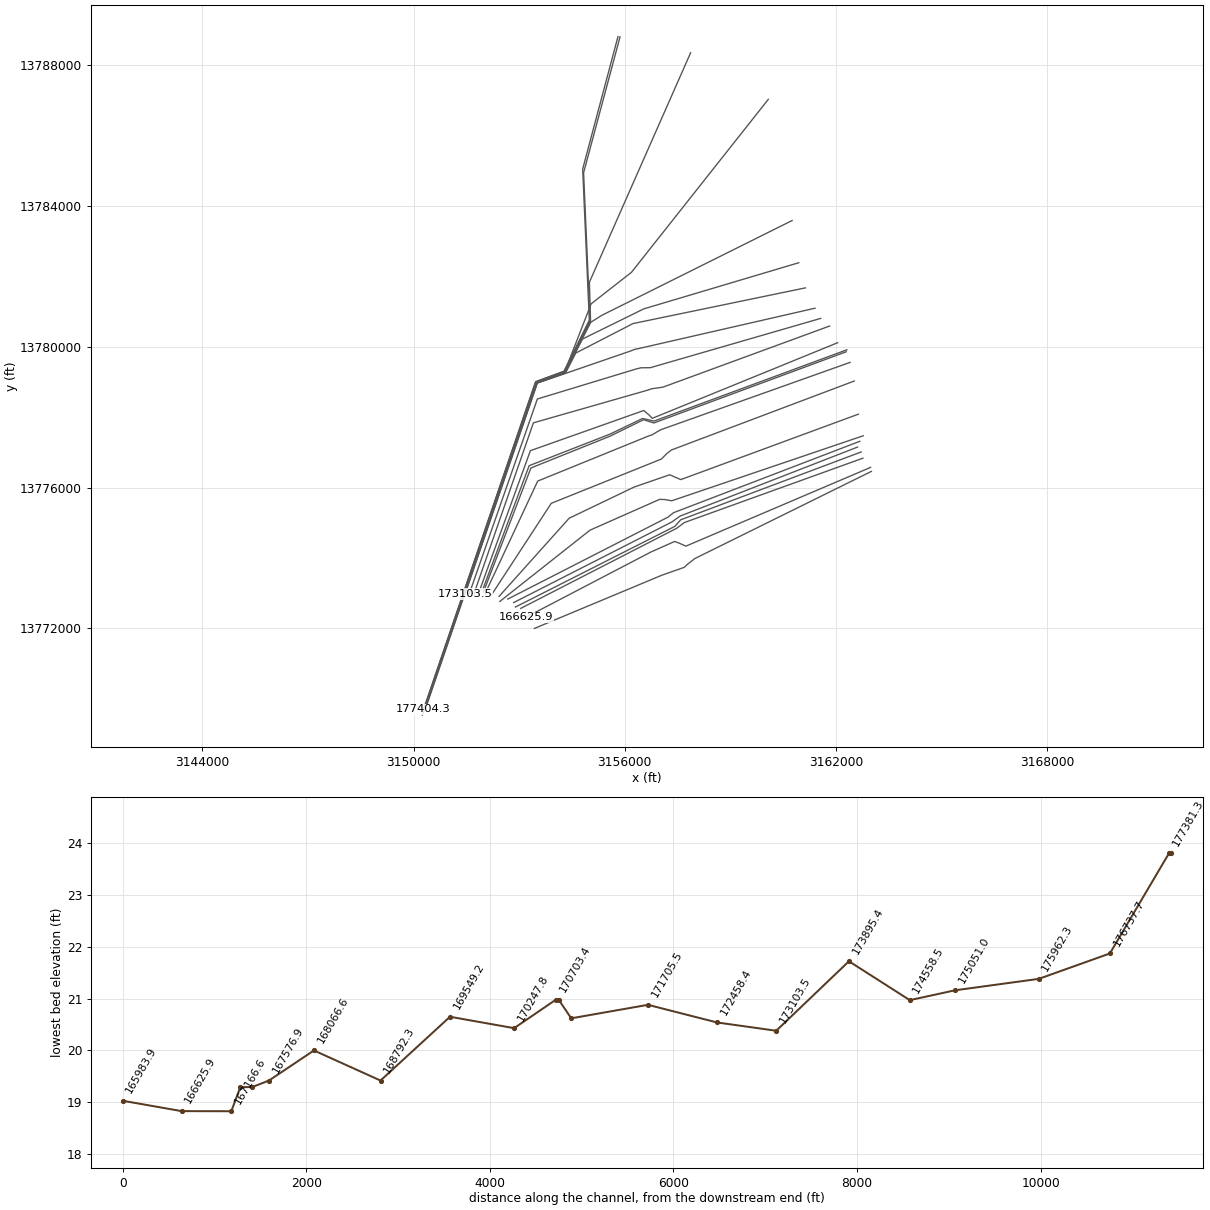
HEC-RAS study A100-00-00.prj: A100-00-00

--- A100-00-00.g01 (geometry) --- (continued)

Type RM Length L Ch R = 3 ,177429  ,,,
BEGIN DESCRIPTION:
Pearland Parkway (DS bridge)
END DESCRIPTION:
Bridge Culvert--1,0,-1,-1, 0
Deck Dist Width WeirC Skew NumUp NumDn MinLoCord MaxHiCord MaxSubmerge Is_Ogee
14,35,2.6,0, 60, 60, , , .95, 0, 0,0,,
 4843.54 4903.54 4943.54 5003.54 5343.54 5383.54 5443.54 5603.54 5663.54 6083.54
 6123.54 6163.54 6223.54 6283.54 6323.54 6363.54 6383.54 6423.54 6483.54 6523.54
 6563.54 6643.54 6723.54 6763.54 6803.54 6863.54 6903.54 6943.54 7003.54 7043.54
 7083.54 7103.54 7163.54 7223.54 7283.54 7343.54 7383.54 7463.54 7483.54 7503.54
 7883.54 7983.54 8163.54 8223.54 8283.54 8463.54 8543.54 8823.54 9123.54 9243.54
 9263.54 9403.54 9463.54 9763.5410063.5410363.5410423.5410663.5410943.54   11300
    40.1   40.04   40.12   40.48   43.81   44.09   44.23   43.72   43.66   45.47
    45.9   46.55   47.95   49.85    51.4   53.15   54.01   55.57   57.56   58.65
   59.55   60.79   61.27   61.22   60.99   60.28   59.57   58.68   56.98   55.61
   54.05    53.2   50.69   48.66   47.14   46.11   45.71   45.42   45.53   45.24
    43.6   43.61   44.24   44.32   44.22   43.53   43.44   44.22   43.33   43.62
   43.55   44.04   44.12   43.23   44.02   43.13   43.21   44.05   43.04   43.03
                                                                                
                                                   48.01   49.57   51.56   52.65
   53.55   54.79   55.27   55.13    54.8   53.95   53.15   52.16   50.32   48.85
    47.2
                                                                                
                                                                                
 4843.54 4903.54 4943.54 5003.54 5343.54 5383.54 5443.54 5603.54 5663.54 6083.54
 6123.54 6163.54 6223.54 6283.54 6323.54 6363.54 6383.54 6423.54 6483.54 6523.54
 6563.54 6643.54 6723.54 6763.54 6803.54 6863.54 6903.54 6943.54 7003.54 7043.54
 7083.54 7103.54 7163.54 7223.54 7283.54 7343.54 7383.54 7463.54 7483.54 7503.54
 7883.54 7983.54 8163.54 8223.54 8283.54 8463.54 8543.54 8823.54 9123.54 9243.54
 9263.54 9403.54 9463.54 9763.5410063.5410363.5410423.5410663.5410943.54   11300
    40.1   40.04   40.12   40.48   43.81   44.09   44.23   43.72   43.66   45.47
    45.9   46.55   47.95   49.85    51.4   53.15   54.01   55.57   57.56   58.65
   59.55   60.79   61.27   61.22   60.99   60.28   59.57   58.68   56.98   55.61
   54.05    53.2   50.69   48.66   47.14   46.11   45.71   45.42   45.53   45.24
    43.6   43.61   44.24   44.32   44.22   43.53   43.44   44.22   43.33   43.62
   43.55   44.04   44.12   43.23   44.02   43.13   43.21   44.05   43.04   43.03
                                                                                
                                                   48.01   49.57   51.56   52.65
   53.55   54.79   55.27   55.13    54.8   53.95   53.15   52.16   50.32   48.85
    47.2
                                                                                
                                                                                
Pier Skew, UpSta & Num, DnSta & Num=  ,6441.41, 2 ,6441.41, 2 , 0 , 0 , 0 ,,
       3       3
       0    52.5
       3       3
       0    52.5
Pier Skew, UpSta & Num, DnSta & Num=  ,6541.41, 2 ,6541.41, 2 , 0 , 0 , 0 ,,
       3       3
       0      55
       3       3
       0      55
Pier Skew, UpSta & Num, DnSta & Num=  ,6641.41, 2 ,6641.41, 2 , 0 , 0 , 0 ,,
       3       3
       0      57
       3       3
       0      57
Pier Skew, UpSta & Num, DnSta & Num=  ,6783.18, 2 ,6783.18, 2 , 0 , 0 , 0 ,,
       3       3
       0    56.5
       3       3
       0    56.5
Pier Skew, UpSta & Num, DnSta & Num=  ,6883.18, 2 ,6883.18, 2 , 0 , 0 , 0 ,,
       3       3
       0    55.5
       3       3
       0    55.5
Pier Skew, UpSta & Num, DnSta & Num=  ,6983.18, 2 ,6983.18, 2 , 0 , 0 , 0 ,,
       3       3
       0    52.5
       3       3
       0    52.5
Abutment Skew #Up #Dn= , 4 , 4
  6383.3 6405.28  7056.6 7083.72
      48       0       0    47.2
  6383.3 6405.28  7056.6 7083.72
      48       0       0    47.2
BR Coef=-1 , 0 , 0 ,, 0 ,,,.8,-1,,0,
WSPro=,,,, 1 ,,,, 0 ,,,, 0 ,,,,-1 ,-1 ,-1 , 0 , 0 , 0 , 0 , 0
BC Design=,, 0 ,, 0 ,,,,,,
BC HTab HWMax=49.91

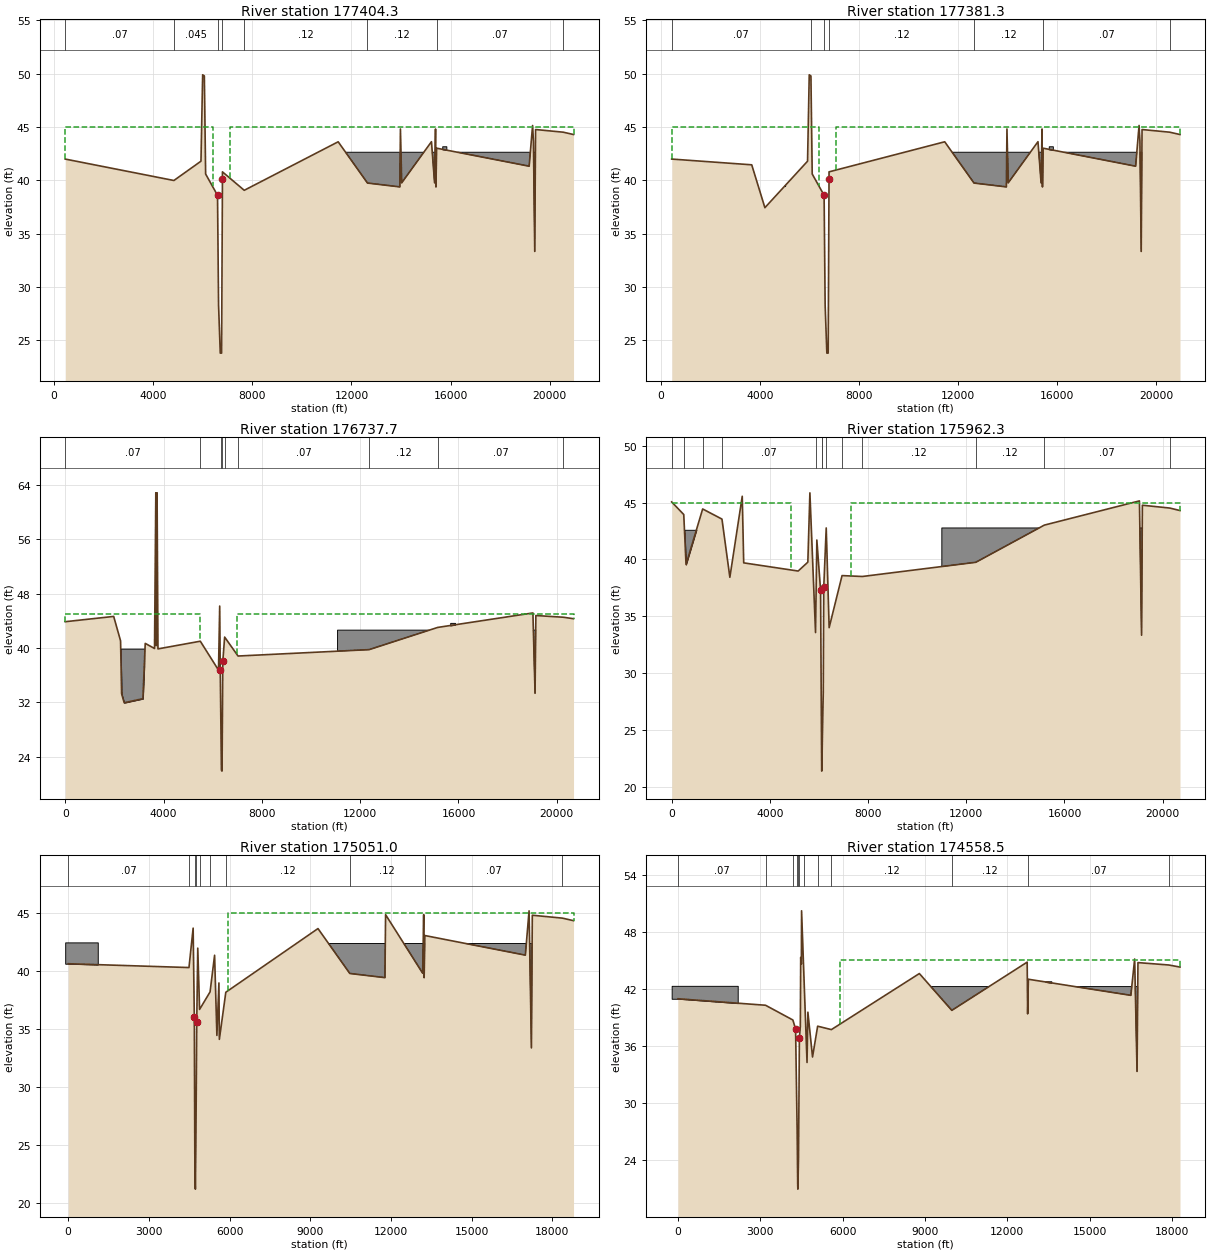
Type RM Length L Ch R = 1 ,177404.3,23,23,23
BEGIN DESCRIPTION:
Added Section (DS face of DS bridge)
END DESCRIPTION:
XS GIS Cut Line= 6
     3155810.185     13788814.87     3154807.551     13785051.11
     3154996.148     13780755.76     3154277.491     13779306.93
     3153468.192     13779007.46 3150286.353063913769698.5596909
#Sta/Elev= 30
  447.23      42 4833.54   39.99 5926.54    41.8  5994.5    49.9 6062.54    49.8
 6114.54    40.6 6594.54    38.6 6636.54    28.3 6705.54    23.8 6758.54    23.8
 6793.54    40.1 6793.54    40.8 7673.18   39.0711463.98   43.6212646.65   39.75
13953.68   39.39 13976.6   44.82 14027.3   39.7715229.11   43.6315355.12   39.77
15392.98   44.8215409.92   39.3915436.98   43.0219172.03   41.3319310.34   45.15
19344.59   43.6719397.33   33.3419430.52   44.77 20549.5   44.5220962.82    44.3
#Mann= 8 ,-1 , 0
  447.23     .07       0 4833.54    .045       0 6594.54    .041       0
 6793.54    .045       0 7673.18     .12       012646.65     .12       0
15436.98     .07       0 20549.5     .15       0
#XS Ineff= 2 , 0
       0 6393.54      45    7078       0      45
Permanent Ineff=
       T       T
#Block Obstruct= 6 ,-1
                                                 5001.53 5276.34   39.53
                        11380.98   20034   42.6415664.1215829.01    43.2
Bank Sta=6594.54,6793.54
XS Rating Curve= 0
Exp/Cntr=.5,.3

Type RM Length L Ch R = 1 ,177381.3,650,644,490
BEGIN DESCRIPTION:
Added Section
END DESCRIPTION:
XS GIS Cut Line= 6
     3155869.151      13788807.5      3154833.21     13784944.69
     3155015.886      13780750.8     3154282.441     13779297.03
     3153475.616     13779002.51 3150292.731408813769697.3013618
#Sta/Elev= 30
  440.62      42 3672.81   41.46 4204.13   37.44 5926.54    41.8  5994.5    49.9
 6062.54    49.8 6114.54    40.6 6594.54    38.6 6636.54    28.3 6705.54    23.8
 6758.54    23.8 6793.54    40.1 6793.54    40.811463.98   43.6212646.65   39.75
13953.68   39.39 13976.6   44.82 14027.3   39.7715229.11   43.6315355.12   39.77
15392.98   44.8215409.92   39.3915436.98   43.0219172.03   41.3319310.34   45.15
19344.59   43.6719397.33   33.3419430.52   44.77 20549.5   44.5220962.82    44.3
#Mann= 7 ,-1 , 0
  440.62     .07       0 6062.54     .12       0 6594.54    .041       0
 6793.54     .12       012646.65     .12       015436.98     .07       0
 20549.5     .15       0
#XS Ineff= 2 , 0
       0 6393.54      45    7078       0      45
Permanent Ineff=
       T       T
#Block Obstruct= 6 ,-1
                                                 5001.53 5276.34   39.53
                        11380.98   19967   42.6415664.1215829.01    43.2
Bank Sta=6594.54,6793.54
XS Rating Curve= 0
Exp/Cntr=.5,.3

Type RM Length L Ch R = 1 ,176737.7,900,775.37,660
BEGIN DESCRIPTION:
Revised Section
END DESCRIPTION:
XS GIS Cut Line= 6
     3157874.755     13788355.11     3154998.512     13781834.76
     3155031.076     13780730.05     3154287.391      13779289.6
     3153483.041     13778997.56 3150280.2217204 13769635.267193
#Sta/Elev= 30
       0   43.86 1972.18   44.64 2251.88   41.05 2294.27   33.26 2399.99   31.93
 3161.18   32.53 3255.92   40.67 3633.52   39.92 3686.72   62.83 3700.98   40.34
 3720.19   41.64 3737.19   62.83 3773.22   39.86 5496.33   40.99 6236.44   36.74
 6285.28   46.16 6307.86   36.69 6354.73   22.03 6378.99   21.87 6386.95   25.14
 6411.94   38.04 6486.27    41.6 7031.45   38.8112364.03   39.7515154.36   43.02
19027.72   45.1519114.71   33.34 19147.9   44.7720266.88   44.52 20680.2    44.3
#Mann= 9 ,-1 , 0
       0     .07       0 5496.33     .12       0 6354.73    .041       0
 6386.95     .07       0 6486.27     .12       0 7031.45     .07       0
12364.03     .12       015154.36     .07       020266.88     .15       0
#XS Ineff= 2 , 0
       0    5489      45    6969       0      45
Permanent Ineff=
       T       T
#Block Obstruct= 5 ,-1
 1273.72 1804.77   42.76 1848.57 1974.49   42.78 2198.47 3215.27    39.9
   11080   20078   42.6215664.1215856.49   43.69
Bank Sta=6307.86,6411.94
XS Rating Curve= 0
Exp/Cntr=.5,.3

Type RM Length L Ch R = 1 ,175962.3,1420,911.34,590
BEGIN DESCRIPTION:
Revised Section
END DESCRIPTION:
XS GIS Cut Line= 6
     3160081.787     13787030.89     3156193.807      13782116.5
     3155047.964      13781220.8     3154292.341      13779279.7
     3153490.466     13778990.14 3150252.3767198 13769532.816821
#Sta/Elev= 30
       0   45.06  492.49   43.95   584.8   39.55 1262.68   44.44 2048.48   43.55
 2370.41   38.43 2874.71   45.56 2933.97    39.7 5152.56   38.98 5546.35   39.76
 5630.14   45.86  5859.8   33.57 5913.01   41.71 6064.96    37.3 6110.35   21.38
  6117.9   21.44 6140.01   24.52 6174.71    28.3 6194.47   37.55 6295.25   42.77
 6414.14      34 6939.88   38.58 7764.91    38.512388.88   39.7515179.21   43.02
19052.57   45.1519139.56   33.3419172.75   44.7720291.73   44.5220705.05    44.3
#Mann= 13 ,-1 , 0
       0     .15       0  492.49     .07       0 1262.68     .15       0
 2048.48     .07       0  5859.8     .12       0  6117.9    .041       0
 6140.01     .07       0 6295.25     .12       0 6939.88     .07       0
 7764.91     .12       012388.88     .12       015179.21     .07       0
20291.73     .15       0
#XS Ineff= 2 , 0
       0    4864      45    7293       0      45
Permanent Ineff=
       T       T
#Block Obstruct= 3 ,-1
   -9.23 2048.34   42.61   11004   20014   42.7715361.8315856.49   42.77
Bank Sta=6064.96,6194.47
XS Rating Curve= 0
Exp/Cntr=.5,.3

Type RM Length L Ch R = 1 ,175051.0,754.94,492.43,470
BEGIN DESCRIPTION:
Revised Section
END DESCRIPTION:
XS GIS Cut Line= 6
      3160758.61     13783587.92     3155347.359     13780892.34
     3155037.883     13780696.02     3154302.241     13779267.33
     3153497.891     13778982.71 3150307.118134513769669.2171651
#Sta/Elev= 30
       0   40.59 4489.85   40.26 4644.66   43.66  4688.1   35.98 4707.04   24.16
 4727.27   21.16 4746.09   24.84 4778.75   35.57 4816.37   41.93 4884.25   36.65
  5273.9   38.16 5441.88   41.32 5527.59   34.41 5603.11   38.93 5619.35   34.07
 5858.76   38.13  9285.2   43.6210467.87   39.75 11774.9   39.3911797.82   44.82
13176.34   39.77 13214.2   44.8213231.14   39.39 13258.2   43.0216993.25   41.33
17131.56   45.1517218.55   33.3417251.74   44.7718370.72   44.5218784.04    44.3
#Mann= 10 ,-1 , 0
       0     .07       0 4489.85     .12       0 4707.04    .041       0
 4746.09     .07       0 4884.25     .12       0  5273.9     .07       0
 5858.76     .12       010467.87     .12       0 13258.2     .07       0
18370.72     .15       0
#XS Ineff= 2 , 0
       0                    5925       0      45
Permanent Ineff=
       F       T
#Block Obstruct= 2 ,-1
 -110.73  1098.8   42.43    9088   17742   42.33
Bank Sta=4688.1,4778.75
XS Rating Curve= 0
Exp/Cntr=.5,.3

Type RM Length L Ch R = 1 ,174558.5,397.98,663.19,730
BEGIN DESCRIPTION:
Revised Section
END DESCRIPTION:
XS GIS Cut Line= 6
     3160947.563      13782388.4     3156543.554     13781077.25
     3154799.635     13780219.52     3154307.191      13779259.9
      3153507.79     13778980.24 3150325.260088413769706.3790339
#Sta/Elev= 30
       0   40.97 3190.23   40.29 4186.96   38.74 4285.87   37.79 4342.62   27.06
  4362.8   21.44 4368.53   20.97 4392.79   24.34 4424.71   36.83 4458.61   38.05
 4472.06   45.31 4496.61   44.63  4503.8   50.21 4591.79   43.16 4702.68   34.28
 4734.19   39.56 4903.26   34.85    5090   38.09 5589.97   37.73 8797.04   43.62
9979.707   39.7512726.04   44.8212742.98   39.3912770.04   43.0216505.09   41.33
 16643.4   45.1516730.39   33.3416763.58   44.7717882.56   44.5218295.88    44.3
#Mann= 12 ,-1 , 0
       0     .07       0 3190.23     .07       0 4186.96     .12       0
 4342.62     .07       0  4362.8    .041       0 4392.79     .07       0
 4591.79     .12       0    5090     .07       0 5589.97     .12       0
9979.707     .12       012770.04     .07       017882.56     .15       0
#XS Ineff= 2 , 0
       0                    5920       0      45
Permanent Ineff=
       F       T
#Block Obstruct= 3 ,-1
 -230.48 2176.16   42.33    8621   17455   42.2513386.2613606.11   42.81
Bank Sta=4285.87,4424.71
XS Rating Curve= 0
Exp/Cntr=.3,.1

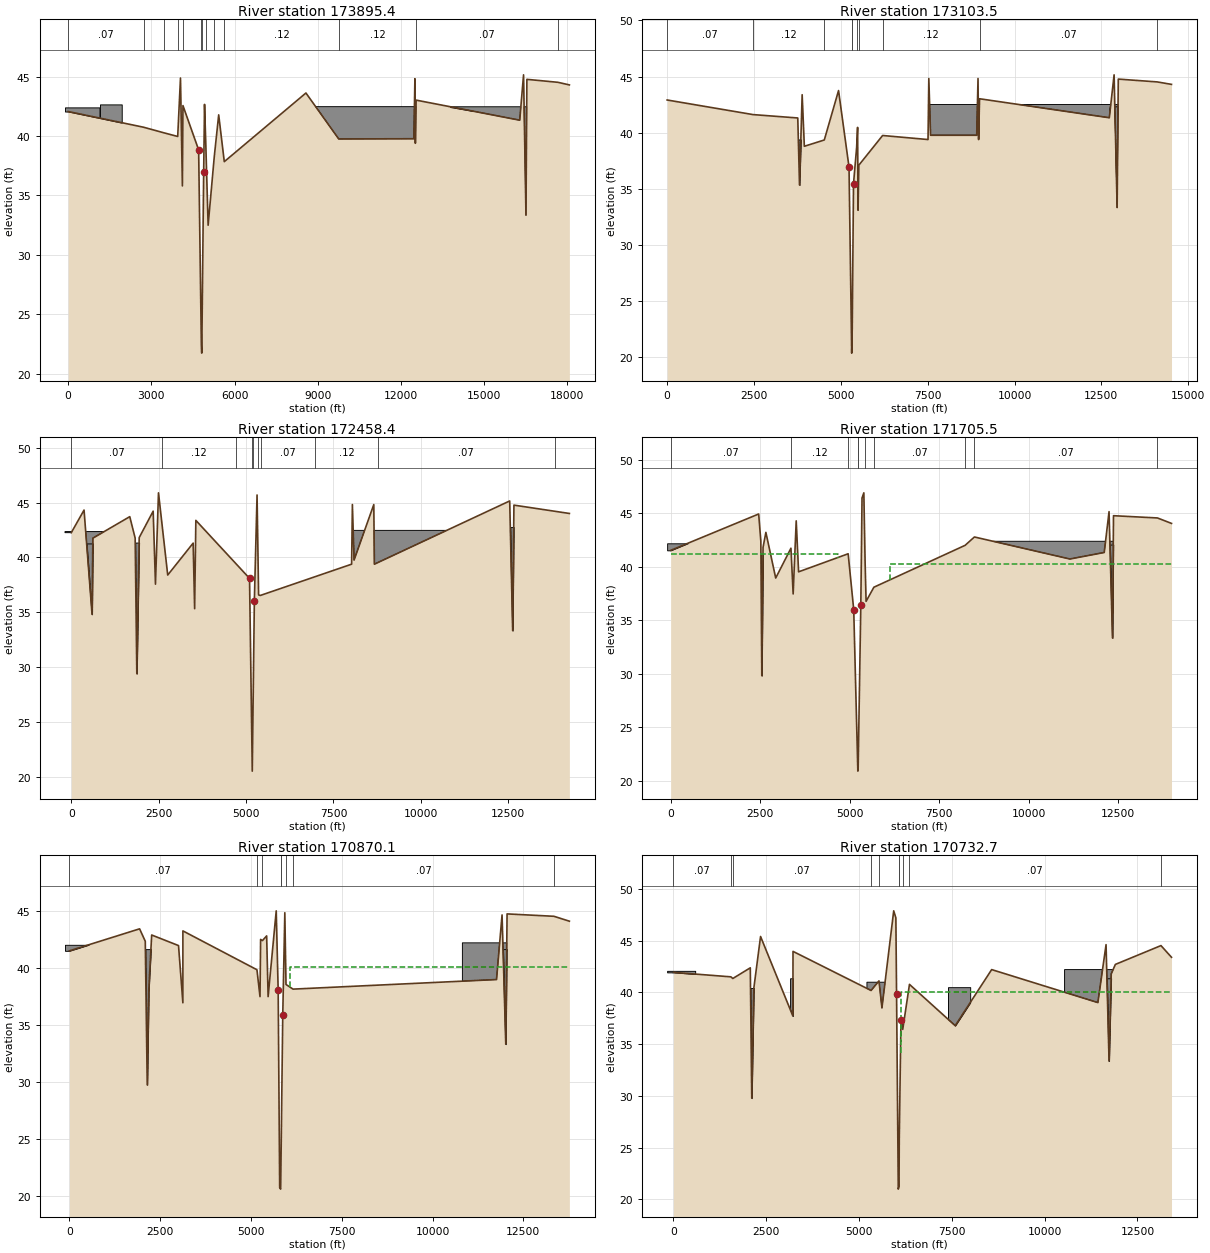
Type RM Length L Ch R = 1 ,173895.4,608.2,791.87,351.06
BEGIN DESCRIPTION:
Revised Section (DS Limit of Revisions)
END DESCRIPTION:
XS GIS Cut Line= 6
     3161137.703     13781674.24     3156238.774     13780660.05
     3154609.036      13779821.3     3154319.565     13779254.95
      3153512.74     13778972.81 3150361.323086313769776.5070609
#Sta/Elev= 30
       0   42.06 2716.61   40.74 3463.73   40.26 3949.57   39.96 4049.45   44.88
 4118.27    35.8 4138.72   42.56 4704.23   38.83  4801.8   22.42 4813.63   21.72
 4817.27   21.74 4885.71   36.97 4916.63   42.66 4958.57    39.6 5046.39   32.49
 5269.06   38.29  5427.2   41.78 5628.94   37.84 8572.84   43.629755.507   39.75
12463.98   39.7712501.84   44.8212518.78   39.3912545.84   43.0216280.89   41.33
 16419.2   45.1516506.19   33.3416539.38   44.7717658.36   44.5218071.68    44.3
#Mann= 13 ,-1 , 0
       0     .07       0 2716.61     .12       0 3463.73     .07       0
 3949.57     .12       0 4138.72     .07       0  4801.8    .041       0
 4817.27     .07       0 4958.57     .12       0 5269.06     .07       0
 5628.94     .12       09755.507     .12       012545.84     .07       0
17658.36     .15       0
#XS Ineff= 2 , 0
       0                 6838.81       0
Permanent Ineff=
       F       T
#Block Obstruct= 5 ,-1
    -114 1128.62   42.41 1146.95  1930.7   42.66  3908.4 4103.82   39.48
 8549.8314603.38   42.4713093.13   17623   42.46
Bank Sta=4704.23,4885.71
XS Rating Curve= 0
Exp/Cntr=.3,.1

Type RM Length L Ch R = 1 ,173103.5,514.26,645.11,445.33
BEGIN DESCRIPTION:
Original TSARP Section
END DESCRIPTION:
XS GIS Cut Line= 6
     3161408.774    13781095.953     3156348.695    13779938.072
     3156316.218    13779938.072     3156141.345    13779870.621
     3153519.497    13778968.051     3151465.533     13772976.51
#Sta/Elev= 30
       0   42.91 2473.91   41.61 3760.69   41.31 3810.71   35.34 3886.79   43.38
 3949.93   38.79 4524.15   39.35 4934.38   43.75 5235.92   36.94 5313.01   20.38
 5328.69    22.6 5365.11   35.46 5455.22    38.7 5482.86   40.47 5495.58    33.1
 5519.25   37.11 6203.05   39.75 7510.08   39.39    7533   44.82  7583.7   39.77
 8911.52   39.77 8949.38   44.82 8966.32   39.39 8993.38   43.0212728.43   41.33
12866.74   45.1512953.73   33.3412986.92   44.77 14105.9   44.5214519.22    44.3
#Mann= 10 ,-1 , 0
       0     .07       0 2473.91     .12       0 4524.15     .07       0
 5313.01    .041       0 5328.69     .07       0 5455.22     .12       0
 5519.25     .07       0 6203.05     .12       0 8993.38     .07       0
 14105.9     .15       0
#Block Obstruct= 3 ,-1
 3761.83 3883.97    39.4 7542.5515189.34   42.5112751.1513093.13    42.3
Bank Sta=5235.92,5365.11
XS Rating Curve= 0
Exp/Cntr=.3,.1

Type RM Length L Ch R = 1 ,172458.4,537.28,752.91,643.34
XS GIS Cut Line= 6
     3161571.416    13780806.811     3156730.919    13779405.956
      3156466.11    13779403.458       3156341.2    13779373.479
     3153519.497    13778516.267     3151583.242     13772976.51
#Sta/Elev= 30
       0   42.26  365.23   44.32  594.37   34.82  617.33   41.76 1673.21   43.72
 1827.49   41.76 1875.06   29.42 1942.78   41.81 2342.61   44.22 2408.28   37.57
 2494.78   45.89 2758.87    38.4 3486.35   41.31 3529.03   35.34 3563.74   43.38
 5099.37    38.1 5177.83   20.54 5237.36   36.04 5314.63   45.69 5358.81   36.59
 5406.96   36.54 8019.67   39.39 8042.16   44.82 8090.19   39.77 8654.34   44.82
 8671.29   39.3912542.33   45.1512627.84   33.3412663.61   44.7714250.05   44.01
#Mann= 10 ,-1 , 0
       0     .07       0 2594.08     .12       0 4698.53     .07       0
 5162.93    .041       0 5190.44     .07       0 5335.22     .12       0
 5425.71     .07       0 6979.39     .12       0 8770.48     .07       0
13825.25     .15       0
#Block Obstruct= 5 ,-1
 -179.58 1610.64   42.36  293.13  659.54   41.28 1758.78 1978.63   41.36
  8037.814251.92   42.4712458.0212726.72   42.77
Bank Sta=5099.37,5237.36
XS Rating Curve= 0
Exp/Cntr=.5,.3

Type RM Length L Ch R = 1 ,171705.5,673.79,835.4,705.24
XS GIS Cut Line= 6
     3161824.415    13780589.955      3157090.66    13778853.854
     3156768.392    13778806.388     3156650.977    13778766.417
     3153406.551    13777838.591     3151724.492    13773000.052
#Sta/Elev= 30
       0   41.53 2456.32   44.93 2516.77    42.4 2543.75   29.81 2578.76   41.81
  2657.8   43.21 2932.34   38.94 3358.22   41.73 3419.52   37.45 3505.01   44.29
 3571.47   39.52 4956.05   41.21 5111.76   35.98 5226.42   20.88 5234.93   21.09
 5309.94   36.44 5343.73   46.43 5394.23   46.91 5429.84   40.37 5457.17   36.76
 5674.31   38.08 8223.36      42 8483.36   42.7811150.69   40.7212109.51   41.33
12244.33   45.1512340.52   33.3412368.41   44.7713596.56   44.5613989.07   44.05
#Mann= 10 ,-1 , 0
       0     .07       0 3358.22     .12       0 4956.05     .07       0
 5226.42    .041       0 5234.93     .07       0 5429.84     .12       0
 5674.31     .07       0 8223.36     .12       0 8483.36     .07       0
13596.56     .15       0
#XS Ineff= 2 ,-1
       0 4667.59   41.19 6115.0413989.07   40.22
Permanent Ineff=
       F       F
#Block Obstruct= 4 ,-1
 -100.85    2360   42.19 2500.76 2629.01    41.2 8447.6113727.39   42.38
12183.2112396.95   42.07
Bank Sta=5111.76,5309.94
XS Rating Curve= 0
Exp/Cntr=.5,.3

Type RM Length L Ch R = 1 ,170870.1,155.06,137.38,375.42
BEGIN DESCRIPTION:
Modified from Sta. 3124.36 to Sta. 4138.68 to reflect fill
END DESCRIPTION:
XS GIS Cut Line= 6
     3162053.402    13780115.524       3156786.5    13777967.004
     3156690.948    13778064.423     3156543.554    13778189.333
     3153321.842    13777047.969       3151842.2     13772976.51
#Sta/Elev= 30
       0   41.53 1932.52   43.46 2088.64   42.37 2142.89   29.77 2184.67   38.08
 2265.15   42.92 3004.68   41.99 3124.36   36.97 3124.72   43.28 5164.57   39.87
 5248.85   37.51 5265.49   42.53 5315.95   42.43 5431.79   42.84 5472.28   37.51
 5695.54   45.04 5749.16   38.07 5790.77   20.76 5816.42   20.62 5819.32   21.01
  5875.2   35.86 5932.44   44.87 5964.76   38.58 6158.17   38.1711763.55   39.01
11915.59   44.6812018.01   33.3412053.75   44.7713345.52   44.5613770.11   44.13
#Mann= 8 ,-1 , 0
       0     .07       0 5164.57     .12       0 5315.95     .07       0
 5816.42    .041       0 5819.32     .07       0 5964.76     .12       0
 6158.17     .07       013345.52     .15       0
#XS Ineff= 2 ,-1
       0 5713.49   41.07 6065.1813770.11   40.07
Permanent Ineff=
       F       F
#Block Obstruct= 4 ,-1
 -121.98  969.08   42.06 2051.91 2329.77   41.6810822.9913660.26   42.23
11883.9712140.46   41.68
Bank Sta=5749.16,5875.2
XS Rating Curve= 0
Exp/Cntr=.5,.3

Type RM Length L Ch R = 1 ,170732.7,40.39,29.24,74.36
BEGIN DESCRIPTION:
Modified from Sta. 3216.83 to Sta. 4417.63 to reflect fill
END DESCRIPTION:
XS GIS Cut Line= 6
      3162314.57    13779914.011     3156835.354    13777888.839
     3156509.202    13777962.703     3155584.275    13777518.227
     3153286.605     13776621.36     3151971.501    13773111.813
#Sta/Elev= 30
       0   41.93 1546.29    41.5  1599.6   41.34 2069.39   42.37 2109.12   29.77
    2165    40.4 2346.07    45.4 3216.83   37.71 3220.61   43.96 5323.38   40.18
 5536.41   41.11 5615.91    38.5 5933.31   47.88 5991.24    47.2 6009.98   39.81
 6056.13   20.98 6076.87   21.25  6082.6   25.79 6128.73   37.35 6176.44   36.42
 6357.76   40.77 7589.44   36.78  8572.1    42.211433.29   39.0111653.46   44.61
11734.62   33.3611793.18   41.78 11904.3    42.713132.92   44.5213416.86   43.39
#Mann= 10 ,-1 , 0
       0     .07       0 1546.29     .12       0  1599.6     .07       0
 5323.38     .12       0 5536.41     .07       0 6076.87    .041       0
  6082.6     .07       0 6176.44     .12       0 6357.76     .07       0
13132.92     .15       0
#XS Ineff= 2 ,-1
       0 6006.06      41 6116.0813416.86      40
Permanent Ineff=
       F       F
#Block Obstruct= 7 ,-1
 -170.69   584.9   42.08 1987.79 2265.65   40.42 3141.98 3398.47   41.36
 5211.84 5694.47   40.98 7395.42 7993.89    40.510536.1913284.04    42.2
11563.3611905.34   41.36
Bank Sta=6009.98,6128.73
XS Rating Curve= 0
Exp/Cntr=.5,.3

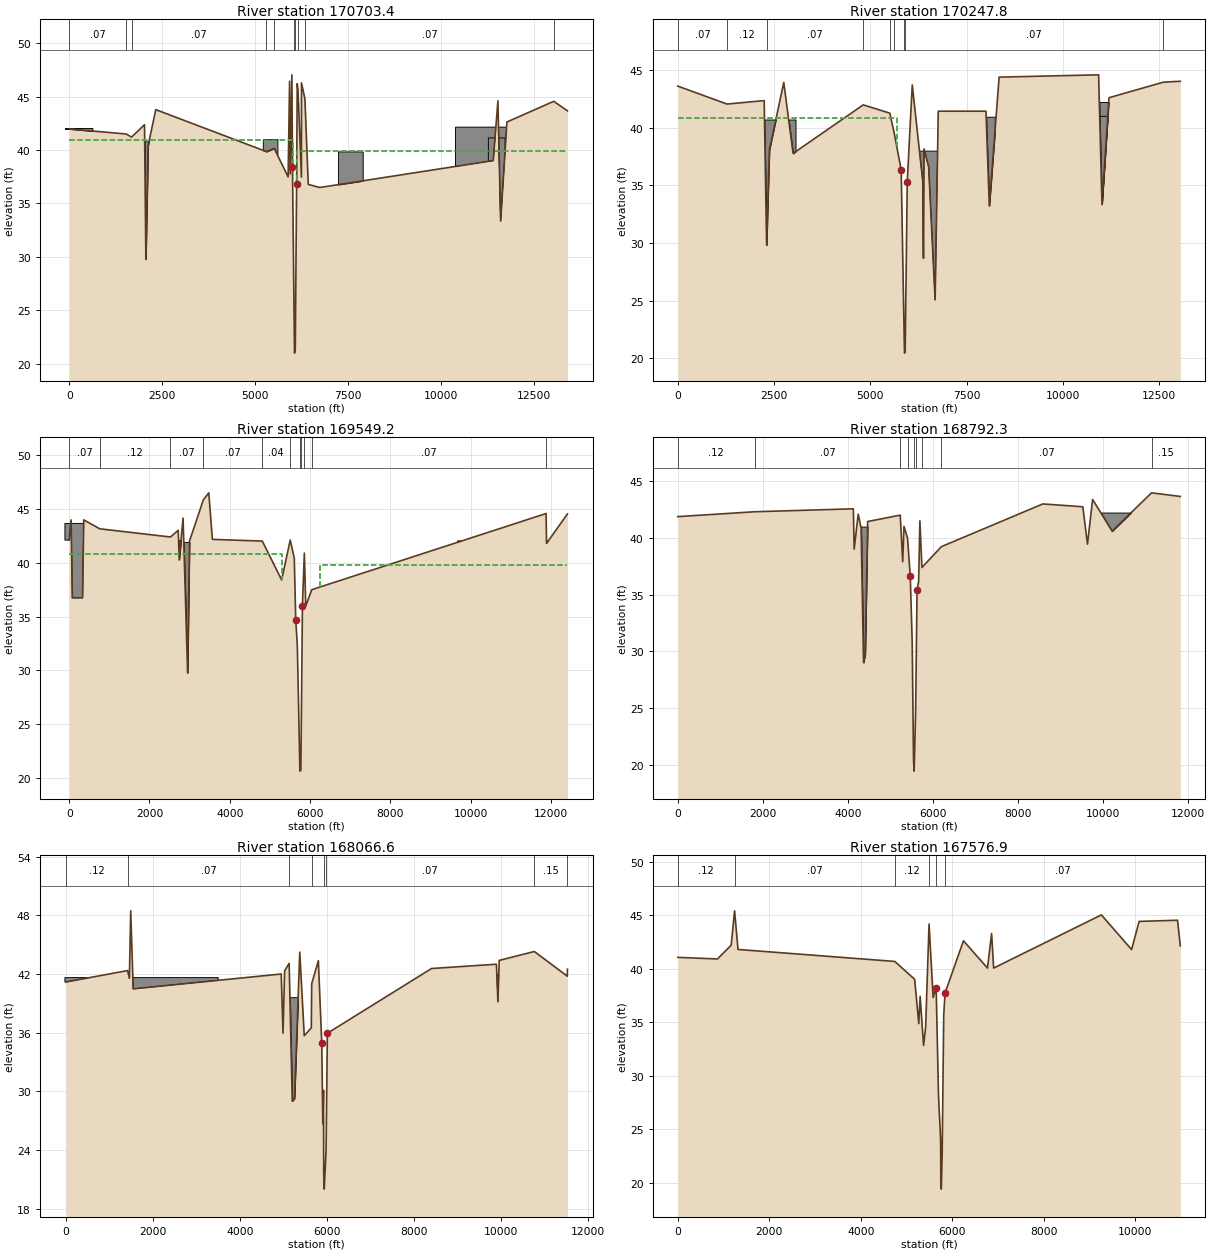
Type RM Length L Ch R = 1 ,170703.4,282.3,455.69,425.57
BEGIN DESCRIPTION:
Modified from Sta. 4788.51 to Sta 5419.03 to reflect fill
END DESCRIPTION:
XS GIS Cut Line= 6
     3162295.934    13779858.103     3156830.469      13777835.1
     3156539.676    13777927.541     3155576.449    13777455.617
     3153335.668    13776555.775     3151990.137    13773037.268
#Sta/Elev= 30
       0   41.97 1525.55    41.5 1674.13   41.21 2022.02   42.37 2058.28   29.77
  2118.8    40.4 2324.74   43.78 5300.51   39.85 5508.57   40.15 5881.95   37.48
 5921.67   46.44 5939.33   37.76 5983.49   47.04 5998.83   38.43 6053.09   20.98
  6074.6   21.25 6110.29   36.81  6126.4   46.21 6147.07   45.64 6239.71   37.47
  6240.7   46.29 6332.85    44.8 6423.86   36.78 6732.07   36.4911394.95   39.01
   11521   44.6111593.89   33.3611762.09   42.6213021.59   44.5613389.82   43.67
#Mann= 10 ,-1 , 0
       0     .07       0 1525.55     .12       0 1674.13     .07       0
 5300.51     .12       0 5508.57     .07       0 6053.09    .041       0
  6074.6     .07       0 6147.07     .12       0 6332.85     .07       0
13021.59     .15       0
#XS Ineff= 2 ,-1
       0 6001.59   40.98 6110.9813389.82   39.94
Permanent Ineff=
       F       F
#Block Obstruct= 7 ,-1
 -117.65  620.49   42.06 1945.04 2180.15   40.81 2949.62 3419.85   41.13
 5200.93 5593.42   41.02 7224.43 7887.02   39.8710381.2713578.88   42.14
11264.1211712.98   41.13
Bank Sta=5998.83,6110.29
XS Rating Curve= 0
Exp/Cntr=.5,.3

Type RM Length L Ch R = 1 ,170247.8,624.05,698.58,751
BEGIN DESCRIPTION:
modified elevations from sta 3006 to sta 4813.61 for fill
END DESCRIPTION:
XS GIS Cut Line= 6
     3162406.527    13779556.409     3157018.212     13777639.73
     3156768.392    13777492.336     3156698.443     13777472.35
     3153529.047    13776183.341     3152030.534     13772976.51
#Sta/Elev= 30
       0   43.63 1278.91   42.07 2243.21   42.37 2306.18   29.81 2378.23   38.08
 2751.47   43.95 2993.27   37.78 4813.61      42 5504.19   41.28 5622.61   39.47
 5799.02   36.35 5882.59   20.76 5886.34   20.43 5903.03   20.74 5956.22    35.3
 6086.94   43.73 6358.58   35.38 6377.04   28.67 6391.26   38.18 6511.74   36.63
 6679.96   25.07 6761.32   41.45 7999.18   41.45  8086.4   33.22 8340.97   44.41
10923.01   44.6111010.63   33.3611192.62   42.6212601.96   43.9713043.14   44.05
#Mann= 9 ,-1 , 0
       0     .07       0 1278.91     .12       0 2306.18     .07       0
 4813.61     .04       0 5504.19     .12       0 5622.61     .07       0
 5882.59    .041       0 5903.03     .07       012601.96     .15       0
#XS Ineff= 2 ,-1
       0 5683.81   40.89 6150.4913043.14   39.85
Permanent Ineff=
       F       F
#Block Obstruct= 6 ,-1
  2137.4 2564.89   40.73  2885.5 3056.49   40.73 6155.73 6839.69   37.98
 7929.77 8229.01   40.97 9691.2913129.28   42.2510687.0211242.75   41.05
Bank Sta=5799.02,5956.22
XS Rating Curve= 0
Exp/Cntr=.5,.3

Type RM Length L Ch R = 1 ,169549.2,956.67,756.91,617.64
BEGIN DESCRIPTION:
modified elevations from sta 2997.64 to sta 4811.94 for fill
END DESCRIPTION:
XS GIS Cut Line= 6
     3162524.236    13779026.721     3157330.487    13777067.642
     3157200.581    13776967.715     3157045.692    13776810.328
     3153914.808    13775551.435     3152218.867    13772952.969
#Sta/Elev= 30
       0   42.09   47.24   43.97   78.02   36.74  333.53   36.74  362.24   43.97
  761.66   43.14 2522.37   42.38 2716.79      43 2741.44   40.27 2837.54   44.14
 2950.43   29.77 2997.64      42 3342.08   45.83 3478.15   46.48 3567.75   42.16
 4811.94      42 5293.57   38.39 5507.41    42.1 5608.42   40.43 5644.66   34.71
 5684.69   32.28  5748.6   20.65 5772.71   20.72 5811.28   35.97 5859.26   40.89
 5894.43   35.98 6044.88   37.4911882.95   44.5611894.04   41.7812415.01   44.52
#Mann= 11 ,-1 , 0
       0     .07       0  761.66     .12       0 2522.37     .07       0
 3342.08     .07       0 4811.94     .04       0 5507.41     .07       0
  5748.6    .041       0 5772.71     .07       0 5859.26     .12       0
 6044.88     .07       011882.95     .15       0
#XS Ineff= 2 ,-1
       0  5294.5   40.81 6253.8112415.01   39.75
Permanent Ineff=
       F       F
#Block Obstruct= 5 ,-1
 -106.87  363.36   43.64 1397.17 2834.35   42.11 2842.75 3056.49   41.91
 3475.04 4326.62   41.98 9677.3212440.39   42.02
Bank Sta=5644.66,5811.28
XS Rating Curve= 0
Exp/Cntr=.5,.3

Type RM Length L Ch R = 1 ,168792.3,569.88,725.62,663.92
BEGIN DESCRIPTION:
modified elevations from sta 4508.7 to sta 5235.63 for fill
END DESCRIPTION:
XS GIS Cut Line= 6
     3162641.944    13778085.054     3157595.296     13776225.75
     3157280.523    13776363.151     3156268.035    13776013.387
     3154423.065    13775127.888     3152430.742    13772905.885
#Sta/Elev= 30
       0   41.87 1808.67    42.3 4131.99   42.56 4151.41      39 4246.76   42.09
 4314.34   40.87  4372.4      29 4411.81   29.76 4469.88   41.44 5235.63      42
 5293.58    37.9 5323.81   41.01 5406.81   39.99 5472.06    36.6 5517.42   30.74
 5548.07   20.47 5562.48   19.42 5597.36   24.56 5631.43   35.41 5668.66   36.15
 5698.26    41.5 5745.52   37.38 6203.53   39.22 8590.61   42.99 9532.63   42.74
 9642.39   39.44  9762.5   43.3910221.87   40.59 11149.5   43.9711826.13   43.65
#Mann= 9 ,-1 , 0
       0     .12       0 1808.67     .07       0 5235.63     .04       0
 5406.81     .07       0 5548.07    .041       0 5597.36     .07       0
 5745.52     .12       0 6203.53     .07       0 11149.5     .15       0
#Block Obstruct= 4 ,-1
 1296.93 2962.46    41.8 4232.06 4525.19   40.99 9791.4711385.65   42.23
       0    1000    41.8
Bank Sta=5472.06,5631.43
XS Rating Curve= 0
Exp/Cntr=.3,.1

Type RM Length L Ch R = 1 ,168066.6,396.13,489.71,553.12
BEGIN DESCRIPTION:
modified n Value from sta 5333.33 to sta 5501.59 for pond
END DESCRIPTION:
XS GIS Cut Line= 6
     3162781.067    13777471.517     3157337.981    13775623.684
     3157140.624    13775658.659      3156993.23    13775663.655
     3155016.031     13774789.05     3152454.284    13772764.635
#Sta/Elev= 30
       0   41.18 1417.56   42.35 1458.77   41.57 1489.54   48.46 1546.49   40.48
 4947.74      42 4988.78   35.95 5025.85   42.33 5129.75   43.08 5201.34      29
 5252.49   29.29 5373.91   44.24 5476.68   35.69 5638.63   36.49 5647.87   41.01
 5800.92   43.36  5878.9   34.94 5903.26   26.69 5919.48    30.1 5923.51   21.64
 5936.08      20 5978.11   23.94 6007.32   35.94  8400.7   42.56 9891.58      43
 9926.29   39.17 9956.26   43.3910762.34    44.311519.82   41.7811523.47   42.49
#Mann= 8 ,-1 , 0
       0     .12       0 1417.56     .07       0 5129.75     .12       0
 5647.87     .07       0 5936.08    .041       0 5978.11     .07       0
10762.34     .15       011519.82     .07       0
#Block Obstruct= 3 ,-1
  -22.13 3499.91   41.63 5093.13  5331.3   39.63 8899.9811962.73   41.91
Bank Sta=5878.9,6007.32
XS Rating Curve= 0
Exp/Cntr=.3,.1

Type RM Length L Ch R = 1 ,167576.9,174.98,184.18,178.79
BEGIN DESCRIPTION:
added x-section
END DESCRIPTION:
XS GIS Cut Line= 4
 3162681.905230913777313.8337412 3157386.633433613775283.9272666
 3157233.197784113775159.3026779   3152680.8926613772831.0566418
#Sta/Elev= 30
       0   41.08  867.86   40.93 1167.12   42.22 1241.94   45.43 1316.75   41.82
  4743.3    40.7 5177.22   39.03    5267   34.89 5296.93   37.44 5371.74   32.85
 5416.63   34.53 5491.44    44.2 5581.22   37.335646.713  38.2615697.824  28.205
5744.035  24.069 5748.92  19.7825758.694   19.42 5778.25  22.729 5812.19   35.69
 5840.43   37.74 6243.53   42.63 6768.34   40.08 6858.31   43.31  6903.3   40.08
 9257.42   45.05 9917.16   41.81 10082.1   44.4410921.77   44.5510981.74   42.16
#Mann= 6 ,-1 , 0
       0     .12       0 1241.94     .07       0  4743.3     .12       0
 5491.44     .07       05646.713     .04       0 5840.43     .07       0
Bank Sta=5646.713,5840.43
XS Rating Curve= 0
Exp/Cntr=.3,.1

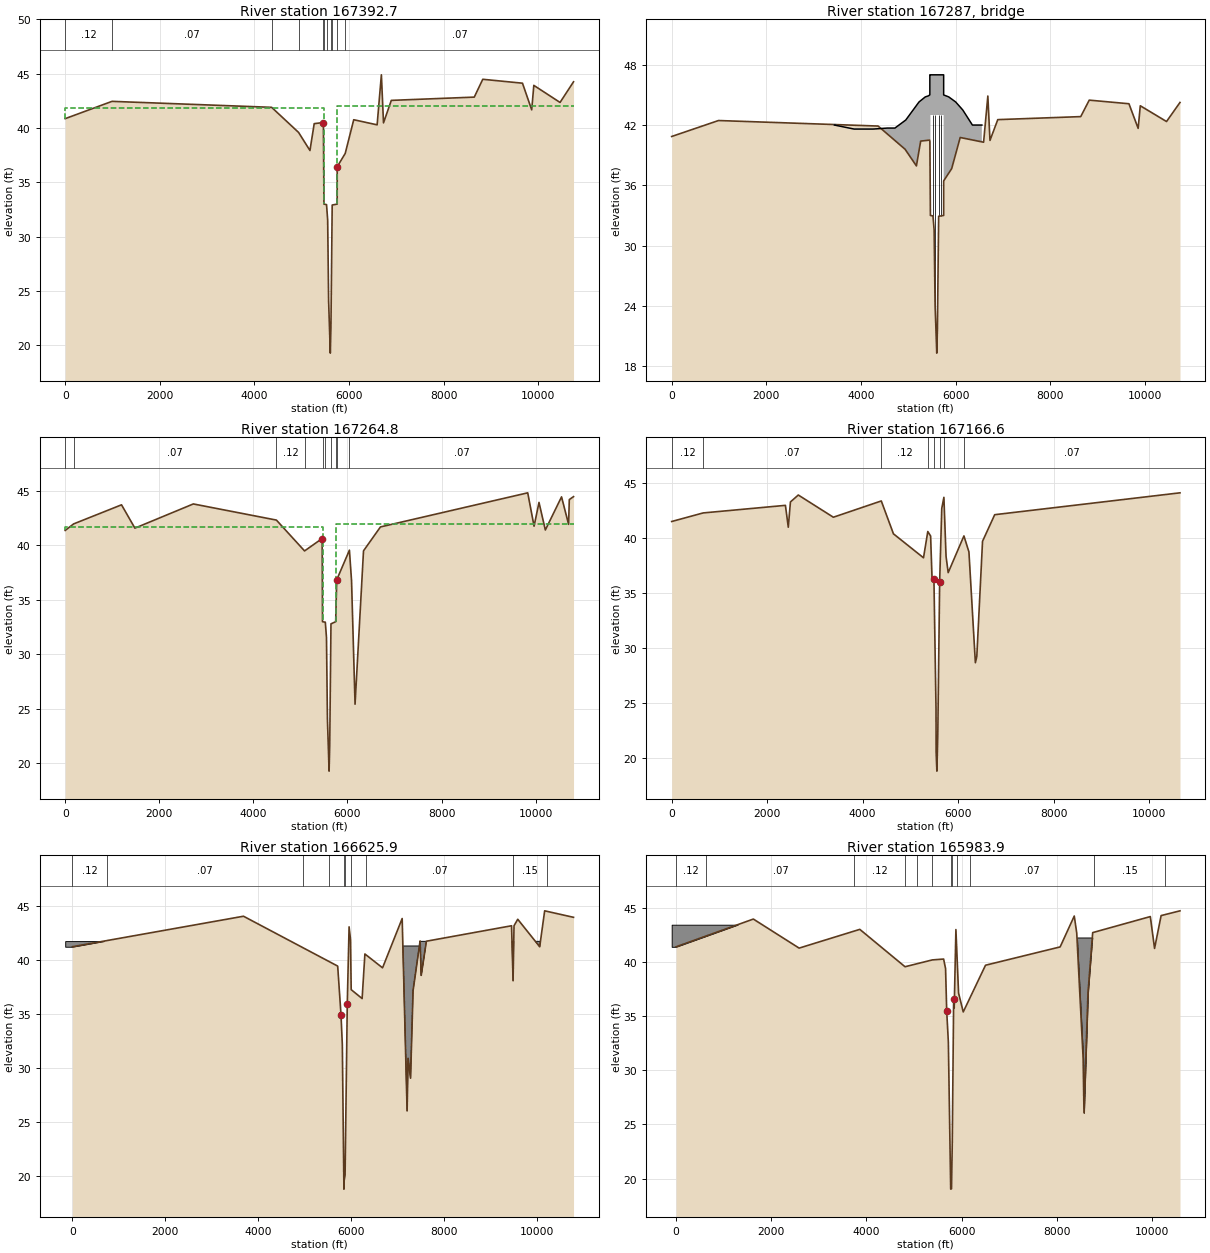
Type RM Length L Ch R = 1 ,167392.7,105.73,127.89,145.42
BEGIN DESCRIPTION:
added x-section
END DESCRIPTION:
XS GIS Cut Line= 4
 3162618.767525313777149.6757066 3157573.268171113775187.4391661
  3157345.65692113775023.1280861 3152845.050694613772730.0363128
#Sta/Elev= 30
       0   40.86  989.75   42.45 4363.91    41.9 4933.77   39.59  5173.7   37.93
 5263.68    40.4 5451.86    40.5 5457.96   40.36 5469.34      33 5524.16   32.95
5548.255  31.5395568.292  24.0775603.797  19.2935617.304  21.685 5643.76 32.9152
 5749.34      33    5750   36.44 5919.19   37.66 6099.05   40.76 6593.66   40.29
 6683.59   44.89 6728.55   40.47 6893.43   42.54 8647.05   42.84 8826.91   44.48
 9666.26   44.12 9861.11   41.67 9906.07   43.9210460.64   42.3510745.41   44.25
#Mann= 11 ,-1 , 0
       0     .12       0  989.75     .07       0 4363.91     .12       0
 4933.77     .07       0 5451.86     .04       0 5469.34    .015       0
 5524.16    .025       05617.304    .025       0 5643.76    .015       0
    5750     .04       0 5919.19     .07       0
#XS Ineff= 2 , 0
       0 5469.34   41.81 5749.34       0      42
Permanent Ineff=
       F       F
Bank Sta=5451.86,5750
XS Rating Curve= 0
Exp/Cntr=.5,.3

Type RM Length L Ch R = 3 ,167287  ,,,
BEGIN DESCRIPTION:
Barry Rose Bridge
END DESCRIPTION:
Bridge Culvert--1,0,-1,-1, 0
Deck Dist Width WeirC Skew NumUp NumDn MinLoCord MaxHiCord MaxSubmerge Is_Ogee
91,35,2.6,0, 22, 22, , , .98, 0, 0,0,,
 3439.34 3857.34 4257.34 4557.34 4718.83 4948.17 5228.57 5360.43 5422.25 5457.24
 5457.34 5469.24 5469.34 5749.34 5749.34 5749.34 5857.34 6002.94 6078.48 6153.52
 6357.34 6557.34
      42    41.6    41.6    41.7    41.7    42.5    44.3    44.8    44.9      45
      47      47      47      47      47      45    44.8    44.3    43.9    43.5
      42      42
                                                                               0
       0       0      43      43
                
 3439.34 3857.34 4257.34 4557.34 4718.83 4948.17 5228.57 5360.43 5422.25 5457.24
 5457.34 5469.24 5469.34 5749.34 5749.34 5749.34 5857.34 6002.94 6078.48 6153.52
 6357.34 6557.34
      42    41.6    41.6    41.7    41.7    42.5    44.3    44.8    44.9      45
      47      47      47      47      47      45    44.8    44.3    43.9    43.5
      42      42
                                                                               0
       0       0      43      43
                
Pier Skew, UpSta & Num, DnSta & Num=  ,5519.34, 2 ,5519.34, 2 , 0 , 0 , 0 ,,
     2.5     2.5
      10      43
     2.5     2.5
      10      43
Pier Skew, UpSta & Num, DnSta & Num=  ,5569.34, 2 ,5569.34, 2 , 0 , 0 , 0 ,,
     2.5     2.5
      10      43
     2.5     2.5
      10      43
Pier Skew, UpSta & Num, DnSta & Num=  ,5649.34, 2 ,5649.34, 2 , 0 , 0 , 0 ,,
     2.5     2.5
      10      43
     2.5     2.5
      10      43
Pier Skew, UpSta & Num, DnSta & Num=  ,5699.34, 2 ,5699.34, 2 , 0 , 0 , 0 ,,
     2.5     2.5
      10      43
     2.5     2.5
      10      43
BR Coef=-1 , 0 , 0 ,, 0 ,,,.8,-1,,1,
WSPro=,,,, 1 ,,,, 0 ,,,, 0 ,,,,-1 ,-1 ,-1 , 0 , 0 , 0 , 0 , 0
BC Design=,, 0 ,, 0 ,,,,,,
BC HTab HWMax=44.82

Type RM Length L Ch R = 1 ,167264.8,116.32,98.16,86.29
BEGIN DESCRIPTION:
added x-section
END DESCRIPTION:
XS GIS Cut Line= 4
 3162719.787854313777010.7727542 3157593.157851913775083.0363183
 3157426.893831613774896.6597148 3152895.560859113772603.7609016
#Sta/Elev= 30
       0   41.37  179.58   41.97 1197.18   43.72 1481.51   41.58 2723.58    43.8
 4489.44   42.32 5088.03   39.49 5462.15   40.63 5469.34      33 5529.34  32.952
  5553.8   31.545573.835  24.077 5609.34  19.2935622.847  21.685 5649.34    32.8
 5749.34      33 5771.82   36.84 6041.47   39.56 6086.41   36.77 6161.31   25.43
 6341.08    39.5 6700.61   41.69 9831.53   44.82 9966.35   41.7610071.21   43.94
10206.04   41.4110550.59   44.4510700.39   41.9310715.38    44.210805.26   44.47
#Mann= 10 ,-1 , 0
       0     .12       0  179.58     .07       0 4489.44     .12       0
 5088.03     .07       0 5469.34    .015       0 5529.34    .025       0
 5649.34    .015       0 5749.34     .07       0 5771.82     .12       0
 6041.47     .07       0
#XS Ineff= 2 , 0
       0 5469.34    41.7 5749.34       0      42
Permanent Ineff=
       F       F
#Block Obstruct= 2 , 0
       0                 6041.47       0   39.56
Bank Sta=5462.15,5771.82
XS Rating Curve= 0
Exp/Cntr=.5,.3

Type RM Length L Ch R = 1 ,167166.6,670.22,540.79,409.76
BEGIN DESCRIPTION:
added x-section
END DESCRIPTION:
XS GIS Cut Line= 4
 3162770.298018813776833.9871784 3157695.169798513775004.6673931
 3157486.010297213774846.1324844 3153047.091352613772565.8782782
#Sta/Elev= 30
       0   41.54  659.36   42.32 2382.68   43.01 2442.62   41.02 2487.58   43.32
 2652.42   43.95  3386.7   41.93 4390.72   43.41 4645.47   40.42 5274.86   38.24
 5364.77   40.63  5423.9   40.22 5453.06   36.475493.217  36.3475537.108  24.494
5539.054  20.592 5555.13  18.8285574.088  22.133 5613.45   36.08 5657.19   42.72
 5702.15   43.74  5747.1   38.37 5792.06   36.89 6121.75   40.23 6226.65   38.77
 6361.52   28.69  6391.5   29.26 6511.38   39.74 6766.14   42.1610647.55   44.15
#Mann= 8 ,-1 , 0
       0     .12       0  659.36     .07       0 4390.72     .12       0
 5364.77     .07       05493.217     .04       0 5613.45     .07       0
 5702.15     .12       0 6121.75     .07       0
#Block Obstruct= 2 , 0
       0                    6151       0   40.32
Bank Sta=5493.217,5613.45
XS Rating Curve= 0
Exp/Cntr=.3,.1

Type RM Length L Ch R = 1 ,166625.9,399.95,641.98,766.32
XS GIS Cut Line= 6
     3162989.701     13776572.74     3157740.191    13774334.614
     3157537.837    13774424.549     3157417.924    13774467.018
     3156743.533    13774166.279     3153200.689    13772316.853
#Sta/Elev= 30
       0   41.24 3684.33   44.06 5712.34   39.45 5783.45   34.96 5812.24   32.18
 5846.57   18.83 5847.14   19.51 5871.38   20.11 5918.66   35.94 5957.67   43.08
 5988.12   41.91 6003.08   37.27 6238.63   36.45 6298.06   40.57 6678.32   39.29
 7100.75   43.85 7206.85   26.07  7228.3   30.92 7281.29   29.09 7335.39   37.18
 7486.54   41.77 7510.71   38.59 7622.07   41.75 9456.01   43.18 9488.47    38.1
 9509.02   43.18 9589.08   43.7810061.96   41.24 10168.7   44.5610790.29   43.96
#Mann= 10 ,-1 , 0
       0     .12       0  735.25     .07       0 4958.89     .12       0
 5520.53     .07       0 5847.14    .041       0 5868.19     .07       0
 5997.46     .12       0 6332.28     .07       0 9477.22     .15       0
10228.33     .07       0
#Block Obstruct= 3 ,-1
 -154.58  943.47   41.76 6961.83 7786.26   41.31 7481.2311481.23   41.74
Bank Sta=5783.45,5918.66
XS Rating Curve= 0
Exp/Cntr=.3,.1

Type RM Length L Ch R = 1 ,165983.9,627.43,747.79,682.17
XS GIS Cut Line= 6
     3163012.368    13776459.406     3157995.007    13773982.368
     3157790.155    13773822.483     3157695.224    13773732.548
     3157062.708     13773510.86     3153435.792    13771996.259
#Sta/Elev= 30
       0   41.39 1624.21   43.95 2585.85   41.27 3860.72      43 4810.76   39.55
    5383   40.18 5621.59   40.26 5662.38   39.38 5686.39   35.46 5720.91    32.6
 5770.05   19.03 5787.21   19.06 5803.43   23.36 5832.27   36.58 5844.01   35.75
 5879.62   42.98 5935.46   37.12 6033.94   35.38 6501.54   39.69 8069.37   41.38
 8366.04   44.23 8417.74   42.67 8552.53   31.09 8570.39   26.07 8654.84   37.18
 8753.34    42.7 9963.75   44.1810052.96   41.2410190.75   44.2710587.29   44.71
#Mann= 12 ,-1 , 0
       0     .12       0   639.9     .07       0 3744.83     .12       0
 4810.76     .07       0 5068.03     .12       0    5383     .07       0
 5766.47    .041       0 5791.99     .07       0 5906.33     .12       0
 6175.57     .07       0 8778.88     .15       010280.69     .07       0
#Block Obstruct= 2 ,-1
   -91.6 1648.85   43.43  8354.2 8830.53   42.25
Bank Sta=5686.39,5832.27
XS Rating Curve= 0
Exp/Cntr=.3,.1