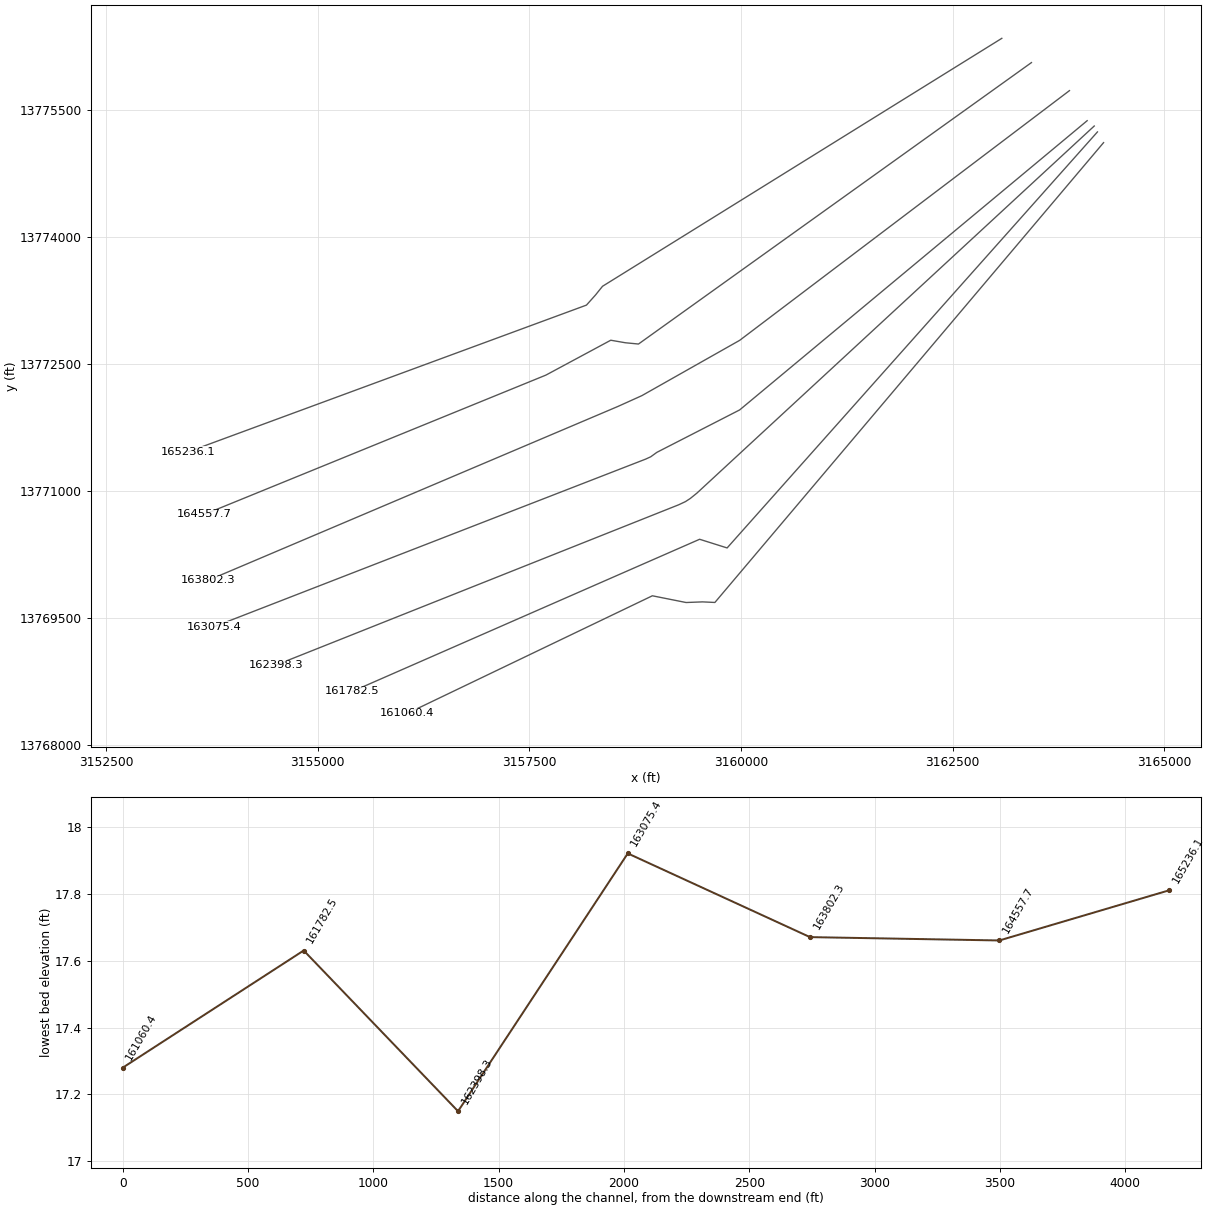
HEC-RAS study A100-00-00.prj: A100-00-00

--- A100-00-00.g01 (geometry) --- (continued)

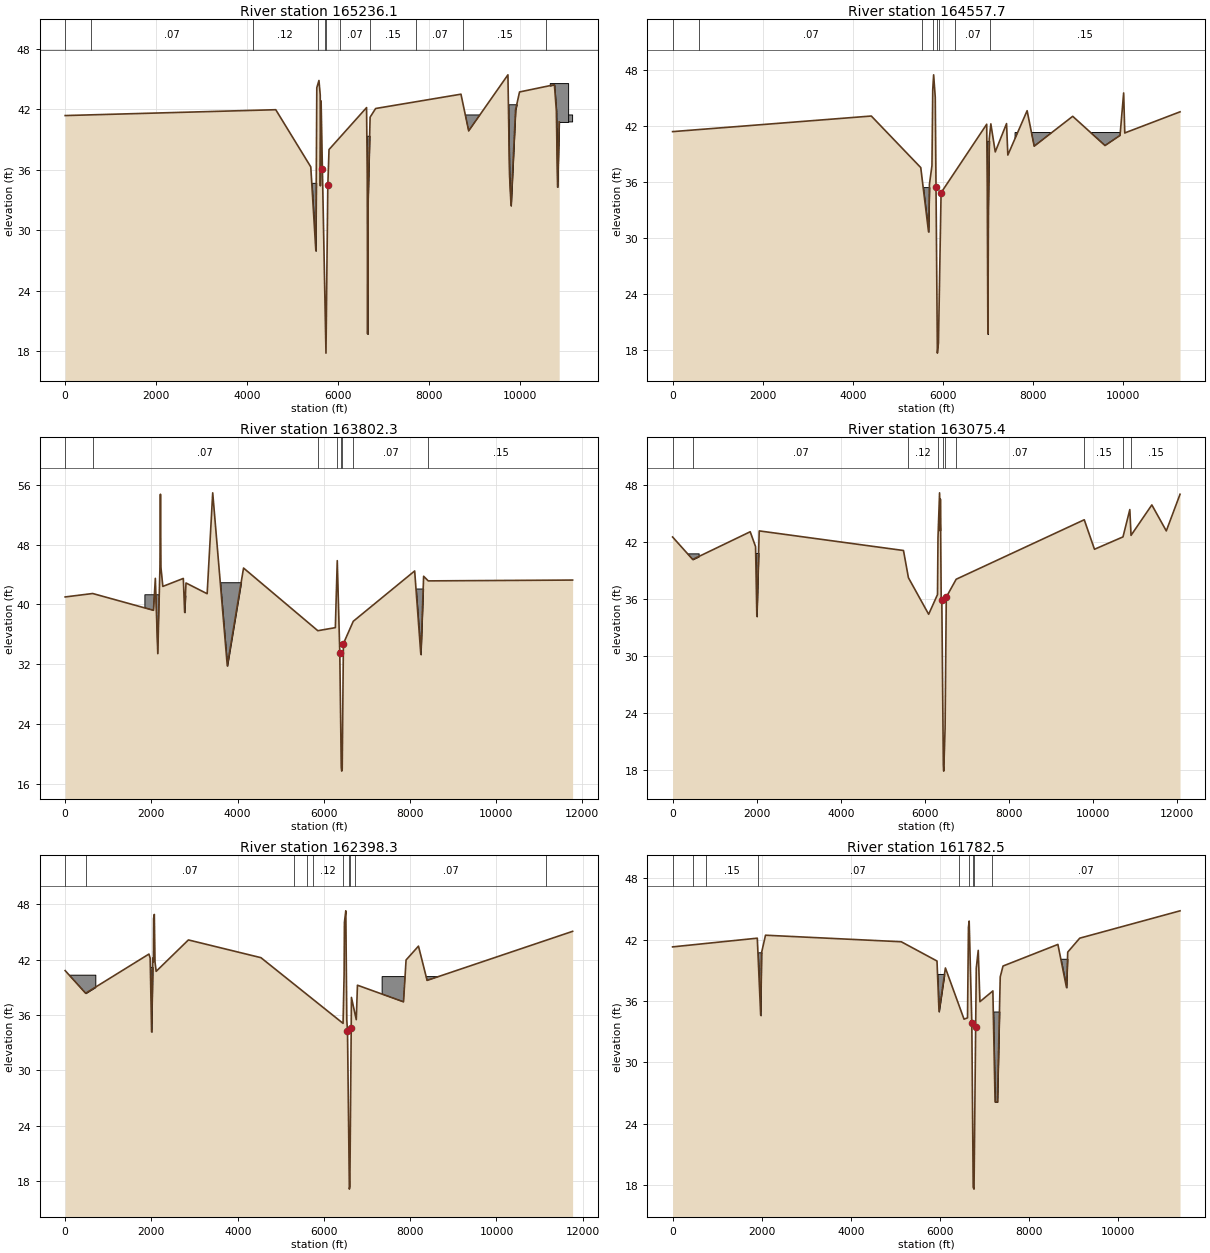
Type RM Length L Ch R = 1 ,165236.1,766.09,678.48,607.96
XS GIS Cut Line= 6
     3163080.368    13776346.072     3158364.741    13773417.775
     3158312.279    13773352.822       3158282.3    13773315.349
     3158174.878    13773195.436     3153475.448     13771463.92
#Sta/Elev= 30
       0   41.37 4625.81   41.95 5395.03   36.28 5506.34   27.95 5527.29   44.13
 5574.45   44.85 5602.67    43.4  5605.6    34.4 5621.69   42.82 5649.85   36.11
 5728.73   17.81 5769.17   34.46  5795.7      38 6620.22   42.16 6635.11   35.32
  6642.8   19.71 6653.14   33.13 6698.15   41.21 6819.13   42.07 8693.88   43.49
 8863.23   39.85 9725.42   45.41 9760.18   35.52 9793.85   32.43 9892.94   41.93
 9980.34   43.71 10746.4   44.4310788.82   41.8710815.87   34.2810851.61   40.74
#Mann= 11 ,-1 , 0
       0     .12       0  574.38     .07       0 4127.95     .12       0
  5545.5     .07       0 5710.88    .041       0 5730.08     .12       0
 6027.09     .07       0 6700.76     .15       0 7715.06     .07       0
 8746.62     .15       010559.27     .07       0
#Block Obstruct= 5 ,-1
  5331.3 5551.15    34.7  6485.5 6723.66   39.37 7276.1711146.04   41.43
 9654.96 9966.41   42.4910644.2711047.33   44.59
Bank Sta=5649.85,5769.17
XS Rating Curve= 0
Exp/Cntr=.3,.1

Type RM Length L Ch R = 1 ,164557.7,642.27,755.36,717.91
XS GIS Cut Line= 6
     3163430.506    13776059.692     3158789.434    13772735.767
     3158634.546    13772750.756     3158462.171    13772780.735
      3157695.86    13772368.653      3153660.68    13770722.995
#Sta/Elev= 30
       0   41.37 4412.41   43.04 5510.42   37.52 5683.18   30.64 5703.41   35.74
 5758.99   37.73 5776.54   45.88 5796.06   47.45 5832.18   45.05 5849.11   35.44
 5879.35   17.66 5903.38   18.77 5961.56   34.83 6974.47   42.16 6986.85   35.32
 7000.45   19.71 7008.56   33.13 7031.86   40.59 7066.48    42.2 7164.26    39.2
 7414.96   42.23  7443.7   38.86 7871.89   43.61 8029.13   39.81 8884.37   43.01
 9601.69   39.88 9935.04   40.9610015.29   45.5110040.21   41.23 11267.4   43.49
#Mann= 8 ,-1 , 0
       0     .12       0  576.67     .07       0 5546.71     .12       0
 5786.71     .07       0 5877.53    .041       0 5905.58     .12       0
 6276.73     .07       0 7056.88     .15       0
#Block Obstruct= 4 ,-1
 1214.09 2526.67   41.19 5441.22 5752.67   35.43 6906.87 7071.76   40.38
 7604.2411601.44   41.27
Bank Sta=5849.11,5961.56
XS Rating Curve= 0
Exp/Cntr=.3,.1

Type RM Length L Ch R = 1 ,163802.3,777.92,726.91,730.04
XS GIS Cut Line= 5
     3163879.456    13775728.601     3159984.672    13772779.465
     3158829.406    13772126.207     3158547.109    13771998.799
     3153710.376    13769945.926
#Sta/Elev= 30
       0   40.99  639.05   41.45 2050.39    39.2 2092.79   43.48 2149.58    33.4
 2199.76   44.98 2211.19   54.74 2222.58   44.98 2266.45    42.4 2742.12   43.47
 2772.71   38.92 2804.35   42.86 3295.29   41.42 3424.28   54.93 3762.71   31.76
 4139.83   44.86 5863.54   36.47 6270.28   36.88 6314.78   45.85 6373.27   33.55
 6407.54   18.17 6418.29   17.67 6429.39   17.95 6457.49   34.74 6686.01   37.73
 8111.11   44.47 8254.32   33.29 8319.13   43.76 8425.96   43.1411776.61   43.25
#Mann= 8 ,-1 , 0
       0     .12       0  639.05     .07       0 5863.54     .12       0
 6314.78     .07       0 6407.54    .041       0 6429.39     .12       0
 6686.01     .07       0 8425.96     .15       0
#Block Obstruct= 6 ,-1
 1850.38 2198.47   41.28 2375.43 3126.28   41.19  3462.6  4177.1   42.96
 8134.35 8335.88   42.12 8798.4210734.79   41.04       0    1000    40.8
Bank Sta=6373.27,6457.49
XS Rating Curve= 0
Exp/Cntr=.3,.1

Type RM Length L Ch R = 1 ,163075.4,617.44,677.11,660.45
XS GIS Cut Line= 6
     3164088.416    13775373.368     3159984.672     13771957.84
     3159006.778     13771456.69      3158934.33    13771404.228
     3158874.373    13771376.747     3153773.626    13769395.879
#Sta/Elev= 30
       0   42.52  478.05   40.16 1845.42   43.07 1972.91   41.51 2003.36   34.17
 2059.88   43.16 5489.93    41.1 5607.52   38.24 6088.65    34.4 6298.79   36.47
 6310.52   42.46 6348.04   47.16 6365.62   43.16 6367.31    46.5 6387.61   35.67
 6401.49    35.9 6437.88   18.52 6446.58   17.92 6466.74   20.64 6479.33   22.44
 6507.42    36.2 6742.88   38.08 9788.32   44.3310031.32   41.23 10709.3   42.53
10871.64    45.410900.57   42.6911395.09   45.8911739.14   43.1612065.84   47.01
#Mann= 10 ,-1 , 0
       0     .12       0  478.05     .07       0 5607.52     .12       0
 6310.52     .07       0 6437.88    .041       0 6466.74     .12       0
 6742.88     .07       0 9788.32     .15       0 10709.3     .07       0
10900.57     .15       0
#Block Obstruct= 3 ,-1
       0  619.85    40.8  1731.3 2051.91   40.84 3143.35 5141.75   40.34
Bank Sta=6401.49,6507.42
XS Rating Curve= 0
Exp/Cntr=.3,.1

Type RM Length L Ch R = 1 ,162398.3,809.79,615.76,493.04
XS GIS Cut Line= 6
        3164172.     13775310.68     3159478.937    13770974.538
     3159401.493    13770912.083     3159344.034     13770874.61
     3159264.092    13770837.137     3154507.774    13768944.095
#Sta/Elev= 30
       0    40.8  474.41   38.35 1941.94   42.59 1971.09   42.15 2004.08   34.17
 2032.06   42.15 2046.01   41.76 2050.52   46.44 2067.18   46.88 2082.41   41.76
 2109.56   40.72 2857.48   44.12  4539.1    42.2 6443.16   35.09 6467.36   40.33
 6474.47   46.01 6506.62   47.27 6529.69   35.43 6545.91   34.31 6589.12   17.15
 6600.82   17.43 6631.84   34.54 6636.98    37.9 6749.34   35.49 6776.58   39.22
 7844.56   37.42 7903.85   41.95 8191.59   43.45 8391.59   39.7411765.18   45.05
#Mann= 10 ,-1 , 0
       0     .12       0   481.9     .07       0 5313.62     .12       0
 5605.28     .07       0 5736.58     .12       0 6433.32     .07       0
 6579.44    .041       0 6603.09     .12       0 6730.74     .07       0
11138.56     .15       0
#Block Obstruct= 3 ,-1
   75.95  699.23   40.36 1905.34 2088.55    41.2 7349.15 8904.69   40.15
Bank Sta=6545.91,6631.84
XS Rating Curve= 0
Exp/Cntr=.3,.1

Type RM Length L Ch R = 1 ,161782.5,631.9,722.09,602.74
XS GIS Cut Line= 4
     3164209.834    13775240.834     3159836.179    13770327.504
     3159511.414     13770429.93     3155411.342    13768633.494
#Sta/Elev= 30
       0   41.28 1901.98   42.13 1978.54   34.59 1995.24   40.66 2086.46   42.42
 5134.63   41.78 5937.22    39.9 5982.94   34.96 6126.22   39.22 6544.51   34.22
 6622.51   34.35  6643.5   43.18 6659.65    43.8 6719.18   33.84 6750.32   17.81
 6768.76   17.63 6805.49   33.49 6819.24    39.2 6863.38   40.94  6900.9   35.93
 7192.03   36.98 7241.49   26.14 7293.83   26.14 7357.24   38.35  7419.7   39.41
 8652.26   41.52 8845.46   37.31 8873.14   40.77 9142.28   42.1311394.86    44.8
#Mann= 9 ,-1 , 0
       0     .12       0  450.78     .07       0  749.33     .15       0
 1915.25     .07       0 6422.71     .12       0 6648.79     .07       0
 6749.63    .041       0 6770.83     .12       0 7180.93     .07       0
#Block Obstruct= 4 ,-1
 1832.06 2088.55   40.75 5917.56 6100.76   38.64 7035.11 7419.85   34.97
  8489.7 9126.82   40.12
Bank Sta=6719.18,6805.49
XS Rating Curve= 0
Exp/Cntr=.3,.1

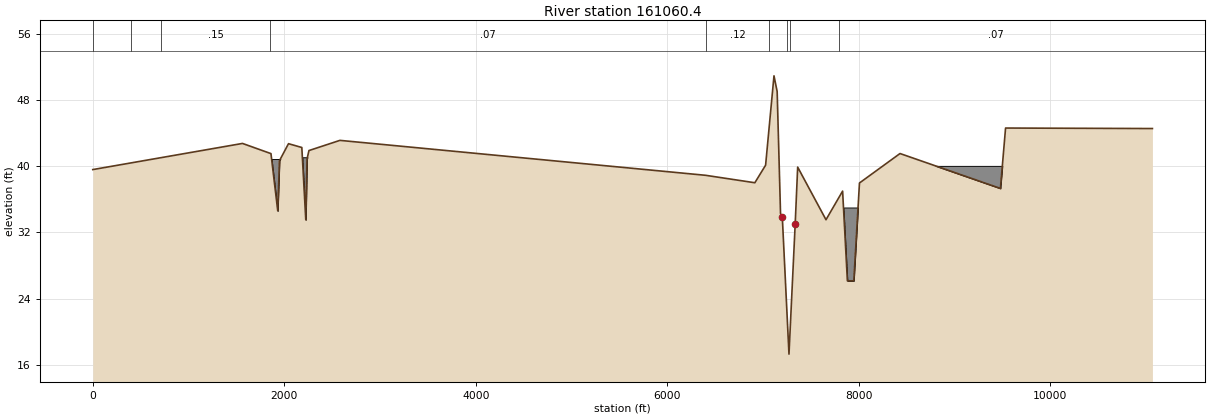
Type RM Length L Ch R = 1 ,161060.4,336.43,476.71,290.71
XS GIS Cut Line= 6
     3164282.119    13775114.334     3159691.802    13769683.619
     3159546.388    13769690.464     3159351.529    13769682.969
     3158953.401    13769762.481     3156059.652    13768373.718
#Sta/Elev= 30
       0   39.58 1563.89   42.74 1861.28   41.51 1932.15   34.59 1950.27   40.66
 2044.37   42.71 2183.53   42.25 2224.98   33.51 2237.82   40.85 2258.01   41.88
 2581.43   43.11 6400.37   38.89  6915.4   37.99  7027.7   40.11 7115.28   50.91
 7148.39   49.01 7183.68   34.27 7202.28   33.83 7271.91   17.28 7336.78      33
 7362.68   39.88 7658.51   33.52 7832.05   36.98 7881.97   26.14 7949.15   26.14
 8008.12   37.96 8431.64   41.52 9480.38    37.3 9534.14    44.611068.14   44.54
#Mann= 9 ,-1 , 0
       0     .12       0  402.33     .07       0  712.12     .15       0
  1853.8     .07       0 6400.37     .12       0 7067.01     .07       0
 7251.29    .041       0 7279.29     .12       0 7789.65     .07       0
#Block Obstruct= 5 ,-1
   395.9  1788.4   40.27 1813.74 2033.59   40.86 2143.51 2326.72   41.07
 7749.62 8061.07      35 8437.84 9722.76   40.03
Bank Sta=7202.28,7336.78
XS Rating Curve= 0
Exp/Cntr=.5,.3