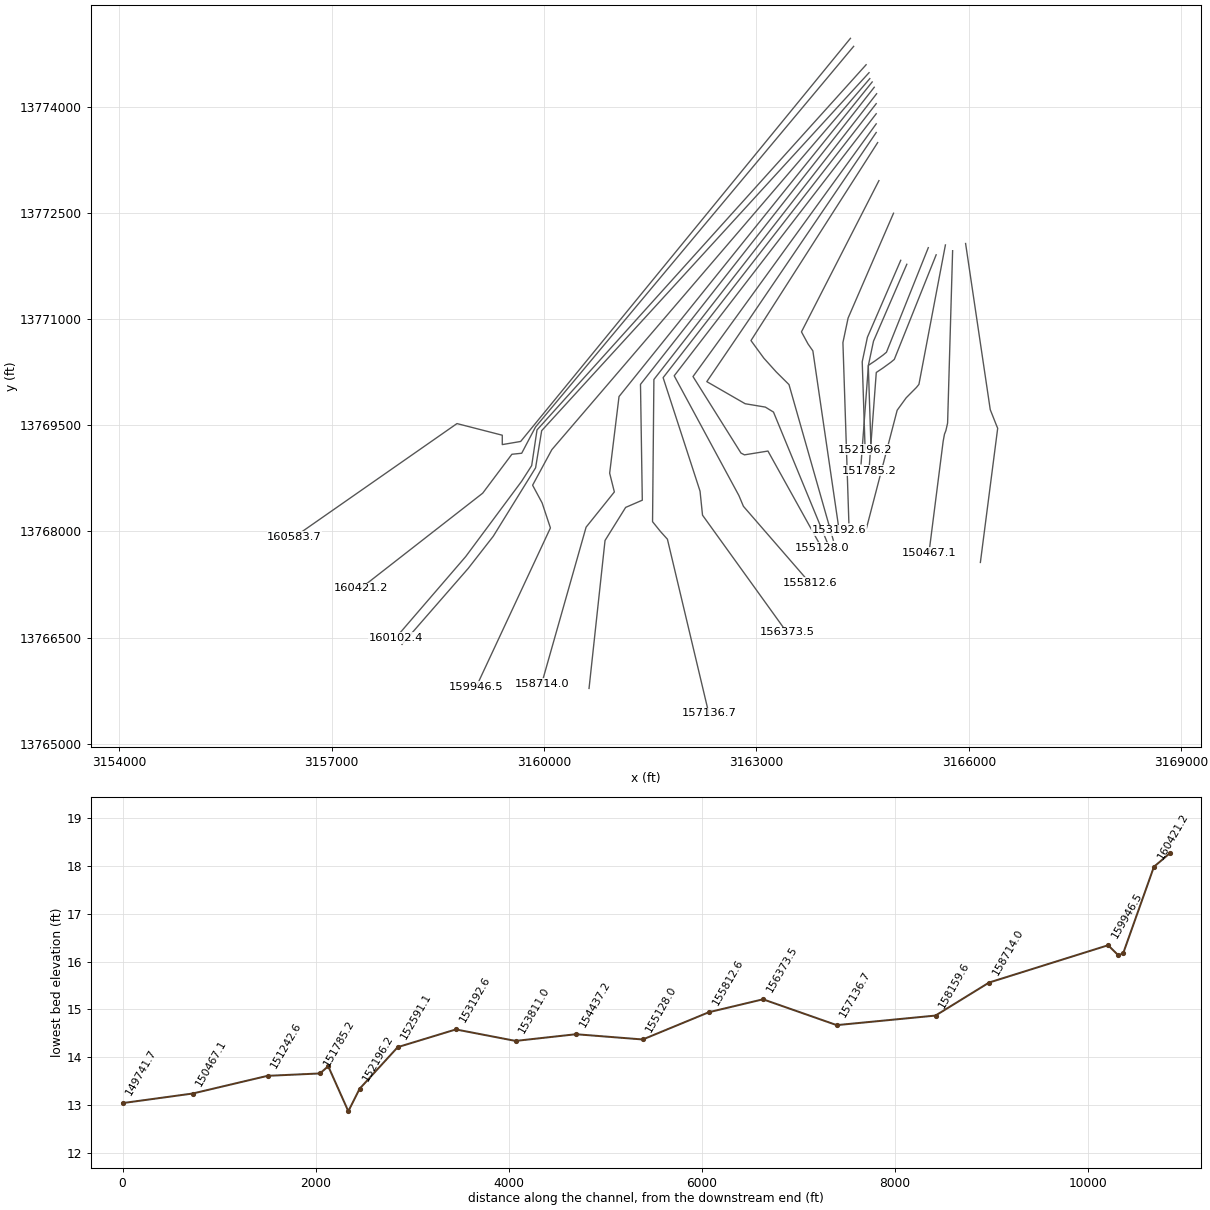
HEC-RAS study A100-00-00.prj: A100-00-00

--- A100-00-00.g01 (geometry) --- (continued)

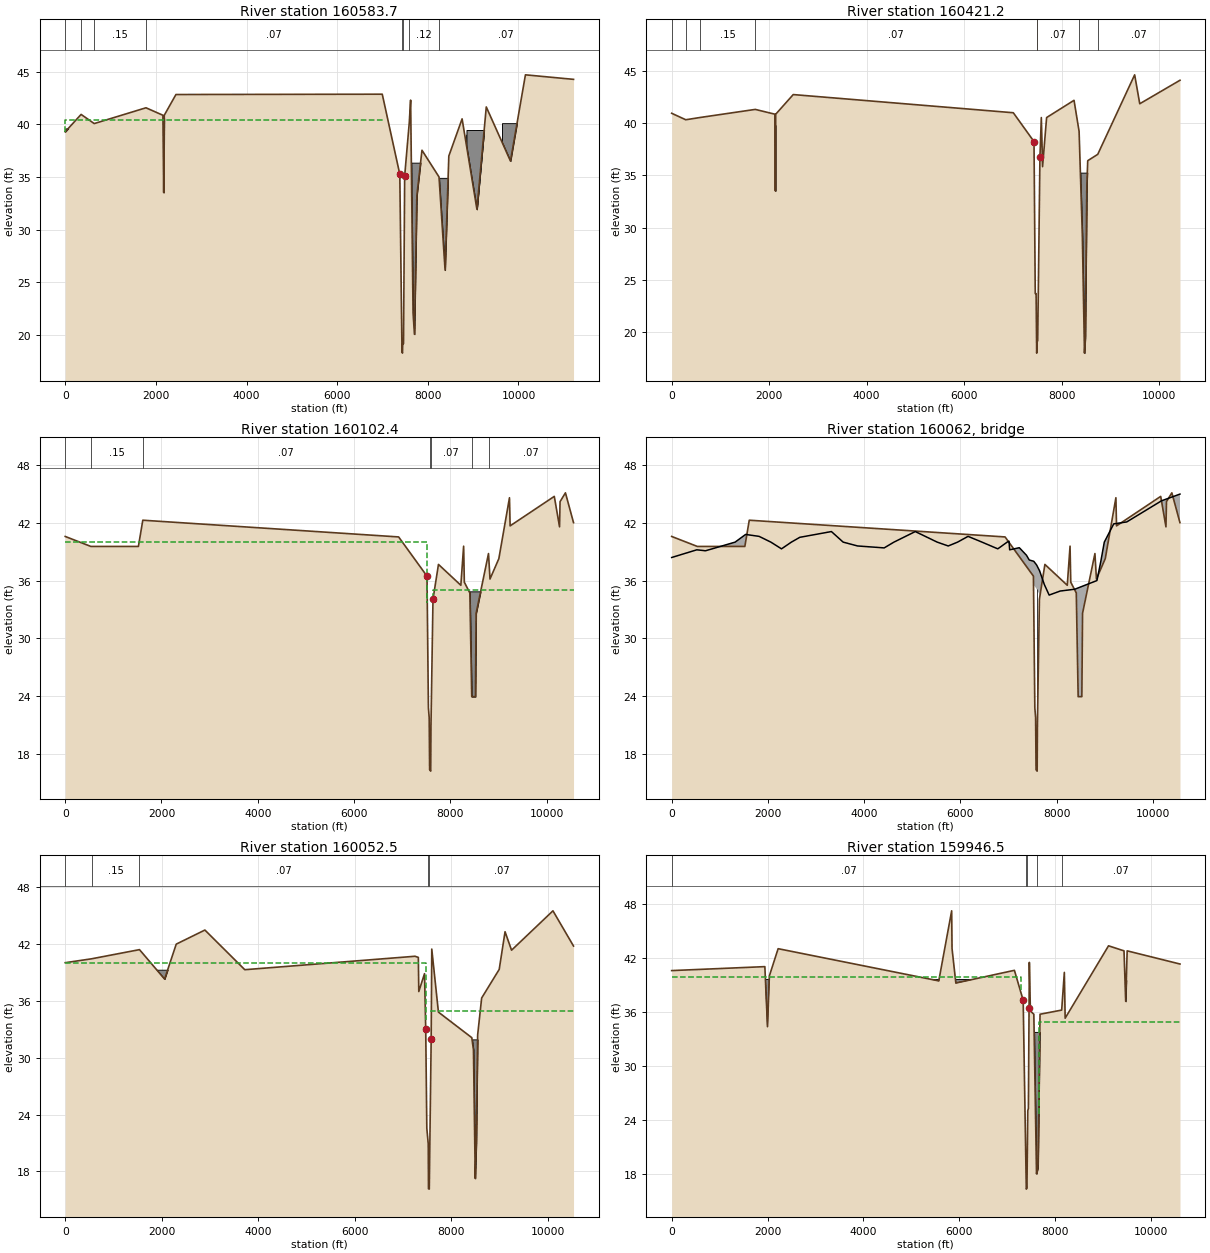
Type RM Length L Ch R = 1 ,160583.7,200.45,162.54,1252.37
XS GIS Cut Line= 6
     3164327.043    13774963.396     3159669.385    13769269.806
     3159409.675    13769225.445     3159409.675    13769357.996
     3158769.782    13769522.364     3156475.293    13767921.934
#Sta/Elev= 30
       0   39.28  350.71   40.93  640.44   40.06 1782.14   41.56 2155.84   40.85
 2173.28   33.51 2185.46   40.85 2443.24   42.82 6995.01   42.85 7381.69   35.25
  7430.5    18.4 7440.98   18.26 7446.69   19.16 7463.91   19.16 7489.43   35.08
 7591.01   40.16 7620.69   42.29 7674.22   22.13 7704.96   20.05 7757.94    33.2
 7871.08   37.53 8247.33   34.99 8381.19   26.14 8463.56   36.98 8756.42   40.51
 9083.51   31.92  9289.9   41.64 9823.94    36.510153.71   44.6911214.87   44.26
#Mann= 8 ,-1 , 0
       0     .12       0  350.71     .07       0  640.44     .15       0
 1782.14     .07       0  7430.5    .041       0 7446.69     .07       0
 7591.01     .12       0 8247.33     .07       0
#XS Ineff= 2 ,-1
       0 7055.05   40.39  8467.911214.87   35.17
Permanent Ineff=
       F       F
#Block Obstruct= 7 ,-1
 2051.91 2363.36   40.56 7548.09 7969.47   36.35 8244.27 8482.44   34.88
 8848.85 9251.91   39.01 8852.76 9477.97   39.45 9636.6410039.69    40.1
       0    2000    39.6
Bank Sta=7381.69,7489.43
XS Rating Curve= 0
Exp/Cntr=.5,.3

Type RM Length L Ch R = 1 ,160421.2,237.95,318.74,439.11
XS GIS Cut Line= 6
     3164372.377    13774850.062     3159878.559    13769472.928
     3159683.942    13769103.279      3159545.39    13769088.946
      3159133.21    13768539.363     3157415.004     13767199.08
#Sta/Elev= 30
       0   40.94  288.98   40.32  589.41   40.54 1715.06   41.31 2119.95   40.85
 2127.88   33.51  2135.1   40.85 2494.77   42.73 7010.56   40.99 7435.08   38.23
 7460.62   23.68 7478.06   23.68 7490.25   17.98 7501.45   19.16 7510.95   19.16
 7556.92   36.74 7585.36   40.53 7610.83   35.83 7693.78   40.53 8256.54   42.18
 8360.37   39.21 8427.37   29.18 8471.03   17.98 8488.49    19.5  8519.3      34
 8537.74    36.4 8743.25   37.01 9500.66   44.62 9605.28   41.8510430.93    44.1
#Mann= 8 ,-1 , 0
       0     .12       0  288.98     .07       0  589.41     .15       0
 1715.06     .07       0 7490.25    .041       0 7501.45     .07       0
 8360.37     .12       0 8743.25     .07       0
#XS Ineff= 2 ,-1
       0 7114.21    40.1 7718.1610430.93   35.09
Permanent Ineff=
       F       F
#Block Obstruct= 2 ,-1
  300.34 2703.07   39.79 8280.92 8574.05   35.26
Bank Sta=7435.08,7556.92
XS Rating Curve= 0
Exp/Cntr=.5,.3

Type RM Length L Ch R = 1 ,160102.4,71.89,49.9,146.9
XS GIS Cut Line= 6
     3164548.514     13774590.42     3159900.305    13769432.588
     3159825.048    13768928.946     3159683.441    13768708.081
      3158893.02    13767643.789      3157902.93    13766494.297
#Sta/Elev= 30
       0   40.59  533.55   39.55 1520.73   39.55 1612.15   42.28 6927.53   40.54
 7516.57   36.46 7545.77   22.75 7562.02   21.74 7571.03   16.32 7593.98   16.17
 7599.48   20.95 7640.96   34.05 7754.92   37.68  8219.9   35.51 8277.54   39.58
 8292.33   35.83 8406.86   34.71 8446.05   23.92  8522.8   23.92 8537.17   32.59
 8794.42   38.81 8825.58   36.16 9009.38   38.28 9230.23   44.62 9243.33   41.69
10161.23   44.7610270.33   41.5910281.07   44.2110392.69   45.1310560.92   42.03
#Mann= 7 ,-1 , 0
       0     .07       0  533.55     .15       0 1612.15     .07       0
 7571.03    .041       0 7593.98     .07       0 8446.05     .12       0
 8794.42     .07       0
#XS Ineff= 2 ,-1
       0 7522.54      40    764210560.92      35
Permanent Ineff=
       F       F
#Block Obstruct= 1 ,-1
  8262.6 8629.01   34.88
Bank Sta=7516.57,7640.96
XS Rating Curve= 0
Exp/Cntr=.5,.3

Type RM Length L Ch R = 3 ,160062  ,,,
BEGIN DESCRIPTION:
Country Club Dr.
END DESCRIPTION:
Bridge Culvert--1,0,-1,-1, 0
Deck Dist Width WeirC Skew NumUp NumDn MinLoCord MaxHiCord MaxSubmerge Is_Ogee
5,38,2.6,0, 44, 44, , , .95, 0, 0,0,,
       0     522     703    1318    1536    1816    2061    2282    2487    2662
    3319    3563    3863    4416    4618    5062    5517    5746    5941    6158
    6448    6776    6971    7009    7023    7223    7371    7430    7522    7523
    7583    7643    7644    7743    7843    8073    8376    8836    8917    8989
    9185    9455   10178   10562
    38.4    39.2    39.1      40    40.8    40.6      40    39.3      40    40.5
    41.1      40    39.6    39.4      40    41.1      40    39.6      40    40.6
      40    39.3      40    40.1    39.2   39.42   38.64   38.14   38.01   38.01
   37.62   37.03   37.03   35.59   34.49   34.91    35.1      36      38      40
    41.9    42.1    44.3      45
                                                                                
                                                                                
                                                                           35.56
   35.12   34.56
                                
       0     462     643    1258    1476    1756    2001    2222    2427    2602
    3259    3503    3803    4356    4558    5002    5457    5686    5881    6098
    6388    6716    6911    6949    6963    7163    7311    7370    7462    7463
    7523    7583    7584    7683    7783    8013    8316    8776    8857    8929
    9125    9395   10118   10502
    38.4    39.2    39.1      40    40.8    40.6      40    39.3      40    40.5
    41.1      40    39.6    39.4      40    41.1      40    39.6      40    40.6
      40    39.3      40    40.1    39.2   39.42   38.64   38.14   38.01   38.01
   37.62   37.03   37.03   35.59   34.49   34.91    35.1      36      38      40
    41.9    42.1    44.3      45
                                                                                
                                                                                
                                                                           35.56
   35.12   34.56
                                
Pier Skew, UpSta & Num, DnSta & Num=  ,7583, 2 ,7523, 2 , 0 , 0 , 0 ,,
    1.33    1.33
       0      36
    1.33    1.33
       0      36
BR Coef=-1 , 1 , 1 ,1.25, 0 ,,,.8,-1,2,0,
WSPro=,,,, 1 ,,,, 0 ,,,, 0 ,,,,-1 ,-1 ,-1 , 0 , 0 , 0 , 0 , 0
BC Design=,, 0 ,, 0 ,,,,,,
BC HTab HWMax=45.13

Type RM Length L Ch R = 1 ,160052.5,106.34,106.05,858.74
XS GIS Cut Line= 6
     3164590.093     13774478.36     3159966.124    13769422.044
     3159880.209    13768897.794     3159282.204    13767930.483
     3158927.754    13767475.908     3157993.287     13766403.94
#Sta/Elev= 30
       0   40.05  544.61   40.46 1538.76   41.43 2058.76   38.32 2299.67   42.01
 2893.38    43.5 3719.79   39.31 7245.43   40.73  7314.5   40.61 7323.85      37
 7442.61   38.89 7467.41   33.02 7490.12   22.55 7519.77    20.9 7524.52   16.17
 7541.12   16.13 7580.34   31.95 7592.72   41.49 7730.51   34.83 8421.89   32.13
 8456.14   30.85 8493.58   17.26 8515.44   21.03 8543.22   32.43 8625.94   36.32
 8989.49   39.34 9110.56   43.32 9245.19   41.3710102.76   45.5310529.02   41.81
#Mann= 5 ,-1 , 0
       0     .07       0  544.61     .15       0 1538.76     .07       0
 7524.52    .041       0 7541.12     .07       0
#XS Ineff= 2 ,-1
       0 7463.19   39.99 7584.1610529.02   34.97
Permanent Ineff=
       F       F
#Block Obstruct= 2 ,-1
 1255.97  2894.2   39.31 8299.24 8610.69   31.95
Bank Sta=7467.41,7580.34
XS Rating Curve= 0
Exp/Cntr=.5,.3

Type RM Length L Ch R = 1 ,159946.5,948.02,1232.47,555.85
XS GIS Cut Line= 6
     3164600.771    13774394.459     3160109.734    13769153.933
     3159838.053    13768651.838     3159972.331    13768402.018
     3160089.565    13768048.434     3159040.647    13765801.869
#Sta/Elev= 30
       0   40.58 1944.71   41.02 1999.51   34.36 2039.05      40 2221.58   43.01
 5574.28   39.44 5842.96   47.21 5850.92   43.02 5930.54    39.2 7152.64   40.61
 7335.34   37.29 7400.45   16.34  7414.1   16.45 7431.44   25.03 7444.15    25.3
 7458.18   36.45 7464.27   41.49 7486.09    36.1 7557.81   35.74 7613.72   18.04
 7644.97   18.76 7687.25   35.74  8138.8    36.2 8194.44   40.38 8211.29    35.3
 9116.64   43.33 9439.73   42.77  9474.7   37.17 9505.56   42.7710608.02   41.31
#Mann= 5 ,-1 , 0
       0     .07       0 7400.45    .041       0  7414.1     .07       0
 7613.72     .12       0  8138.8     .07       0
#XS Ineff= 2 ,-1
       0 7286.12   39.87 7659.7310608.02   34.89
Permanent Ineff=
       F       F
#Block Obstruct= 3 ,-1
  436.86 7085.32    39.6 7548.09 7749.62   33.78 9242.3210102.39   39.53
Bank Sta=7335.34,7458.18
XS Rating Curve= 0
Exp/Cntr=.5,.3

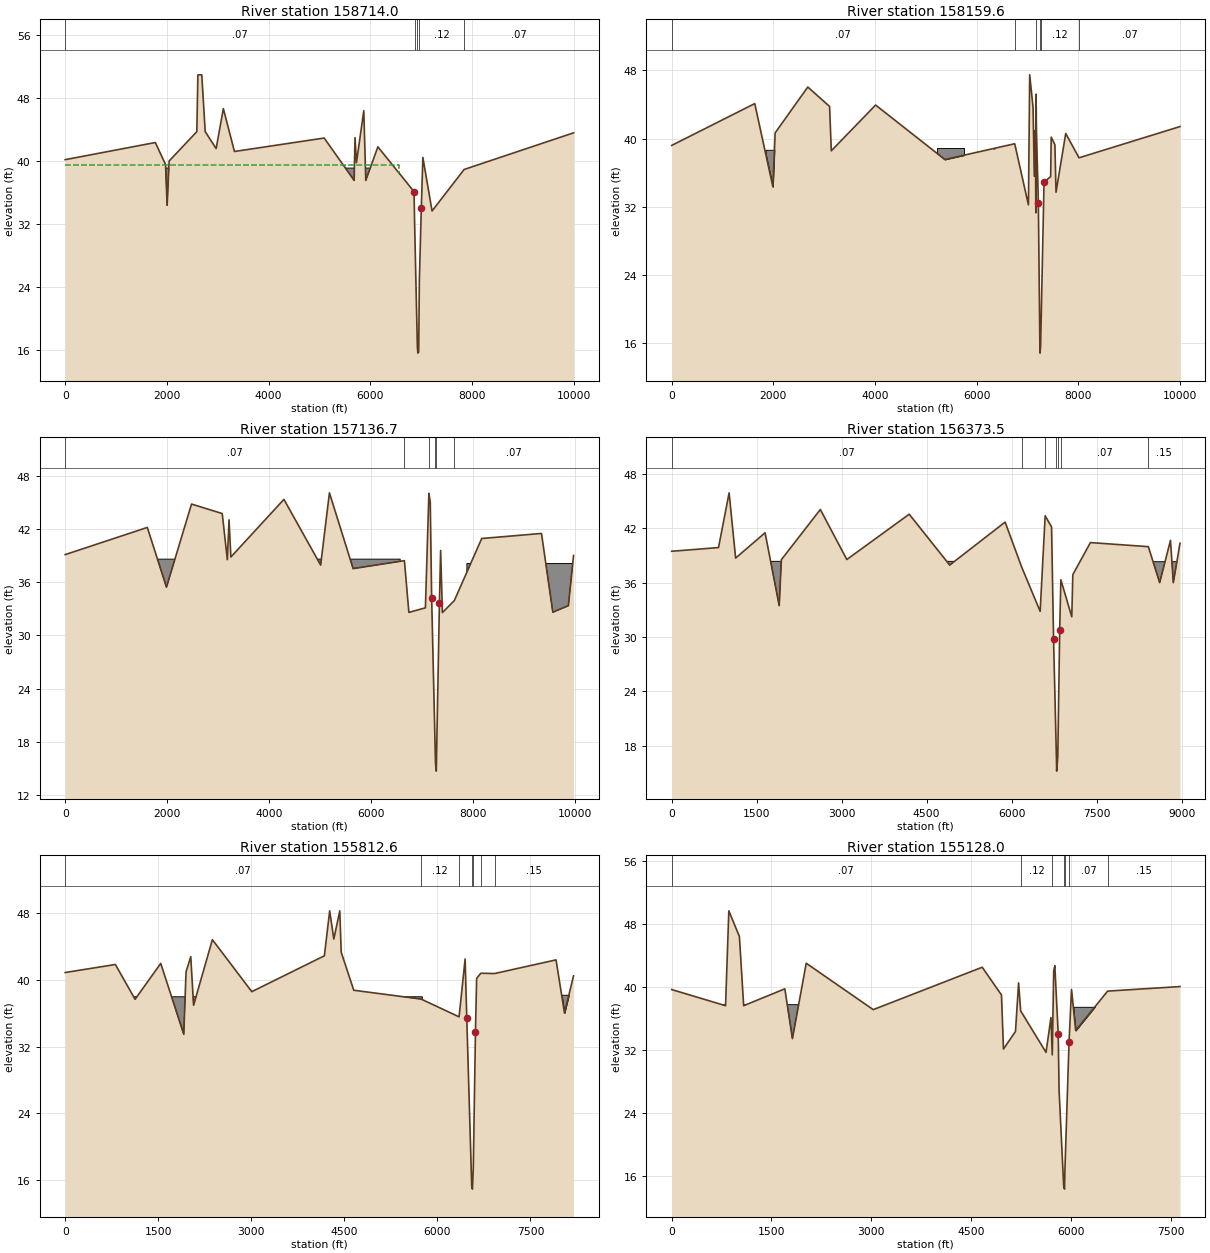
Type RM Length L Ch R = 1 ,158714.0,531.69,554.43,389.2
XS GIS Cut Line= 6
     3164634.332    13774347.169     3161058.641    13769904.136
     3160926.331    13768822.028     3160992.689    13768556.594
     3160593.482    13768059.147     3159966.524    13765850.599
#Sta/Elev= 30
       0   40.17 1773.11   42.35 1974.68   39.54    2005   34.36 2044.75      40
 2589.57   43.73 2610.04   50.95  2686.9   50.96  2754.5   43.73 2969.49   41.58
 3111.28   46.66 3329.44   41.21    5095   42.92 5684.57   37.53 5701.19   42.97
 5730.37   39.79 5874.36    46.4 5913.28   37.53 6151.52    41.8 6862.87    36.1
 6873.25   32.38 6928.18   16.35 6938.17   15.56 6953.94    15.7 6967.56   24.86
 7005.91      34 7036.35   40.45  7217.4   33.64 7847.95   38.9210000.57   43.58
#Mann= 5 ,-1 , 0
       0     .07       0 6873.25     .12       0 6928.18    .041       0
 6953.94     .12       0 7847.95     .07       0
#XS Ineff= 2 ,-1
       0 6566.27   39.45 7668.4410000.57   34.33
Permanent Ineff=
       F       F
#Block Obstruct= 1 ,-1
 1051.19  6211.6    39.1
Bank Sta=6862.87,7005.91
XS Rating Curve= 0
Exp/Cntr=.5,.3

Type RM Length L Ch R = 1 ,158159.6,282.31,1022.88,1141.85
XS GIS Cut Line= 6
     3164663.316    13774272.421     3161361.776    13770076.215
     3161387.336    13768440.347     3161152.118    13768338.419
     3160860.986    13767871.109     3160635.094    13765781.608
#Sta/Elev= 30
       0    39.2 1635.04    44.1 1991.22   34.36 2036.53   40.67 2678.53   46.04
 3107.26   43.77  3141.3   38.57 4013.28   43.93 5375.85   37.55 6750.3739.39677
 7020.41   32.24  7045.1   47.47 7111.58   43.63 7135.73   35.61 7156.41   40.95
 7166.02   31.31  7170.5    45.2 7178.0940.98443 7215.54   32.51 7244.3116.54882
  7248.9   14.87 7260.1115.70365 7327.33   34.92 7457.51   35.54 7468.25   40.17
 7541.25   39.28 7563.61   33.72 7754.36    40.6 8015.63 37.750810002.91   41.41
#Mann= 6 ,-1 , 0
       0     .07       0 6750.37     .12       0 7178.09     .07       0
 7244.31    .041       0 7260.11     .12       0 8015.63     .07       0
#Block Obstruct= 3 ,-1
 1850.38 2161.83   38.69 5221.37 5752.67    38.9 6334.47 6730.38   38.87
Bank Sta=7215.54,7327.33
XS Rating Curve= 0
Exp/Cntr=.3,.1

Type RM Length L Ch R = 1 ,157136.7,713.56,763.24,689.41
XS GIS Cut Line= 6
     3164696.877    13774180.892     3161551.087    13770144.867
     3161532.128    13768137.126     3161642.316    13767999.875
     3161742.148    13767889.107     3162326.556    13765429.349
#Sta/Elev= 30
       0   39.13 1611.99    42.2 1987.92   35.45 2479.56   44.84 3082.33   43.77
 3182.75   38.56 3215.84   43.06 3252.26   38.86 4293.47   45.37  5014.2   37.95
 5186.74   46.11 5651.95   37.55 6658.5638.44737 6746.34    32.6 7070.55   33.12
 7139.2246.05661 7166.27   45.03 7193.28   34.24 7268.64 15.6038 7283.38   14.67
    7287 15.5032  7345.6   33.66  7369.5   39.59 7404.29   32.58 7638.4433.93687
 8176.28   40.95 9349.42   41.52 9571.85   32.62 9877.39   33.36 9978.36   39.03
#Mann= 6 ,-1 , 0
       0     .07       0 6658.56     .12       0 7139.22     .07       0
 7268.64    .041       0    7287     .12       0 7638.44     .07       0
#Block Obstruct= 2 ,-1
  546.08 6575.65   38.62 7884.93 10165.1   38.12
Bank Sta=7193.28,7345.6
XS Rating Curve= 0
Exp/Cntr=.3,.1

Type RM Length L Ch R = 1 ,156373.5,444.13,560.88,550.64
XS GIS Cut Line= 5
     3164691.044    13774040.663     3161681.446    13770170.939
     3162202.754    13768568.305     3162237.884    13768228.706
     3163430.506     13766572.23
#Sta/Elev= 30
       0   39.47  826.67   39.88 1013.61   45.92 1128.59   38.72 1648.43   41.51
 1897.91   33.47 1935.48   38.54 2623.52   44.08 3090.93   38.56  4191.4   43.56
 4906.64   37.95 5884.19   42.69 6177.7337.70678 6502.55   32.84 6590.8143.38647
 6703.85   42.15 6739.16   29.75 6790.6616.32808 6793.76   15.21 6813.4516.75795
 6847.39   30.83 6867.8136.32335 7060.62   32.24 7078.84   36.89 7389.11   40.43
 8411.4839.98037 8611.46   36.01 8802.28   40.67 8852.54   36.01 8970.14   40.36
#Mann= 7 ,-1 , 0
       0     .07       0 6177.73     .12       0 6590.81     .07       0
 6790.66    .041       0 6813.45     .12       0 6867.81     .07       0
 8411.48     .15       0
#Block Obstruct= 2 ,-1
  784.98 5915.81   38.36 8355.41 9210.95   38.32
Bank Sta=6739.16,6847.39
XS Rating Curve= 0
Exp/Cntr=.3,.1

Type RM Length L Ch R = 1 ,155812.6,325.5,684.59,832.99
XS GIS Cut Line= 6
     3164691.044    13773898.133     3161837.878    13770197.011
     3162654.576    13768685.408     3162752.162    13768504.874
     3162815.593    13768353.616     3163755.441    13767270.413
#Sta/Elev= 30
       0   40.85  808.81   41.81 1126.37   37.65 1540.08   41.94 1911.19   33.47
 1948.17   40.93 2024.12   42.74  2069.6   36.94 2372.82   44.78 3007.87   38.56
 4177.94   42.85 4263.55   48.23 4330.43   44.85 4426.49   48.23 4449.44   43.28
  4651.8   38.73 5736.3537.67604  6349.835.54882 6446.92   42.47 6473.36   35.45
 6553.2715.28154 6564.76   14.94  6578.617.42198 6613.67   33.76 6632.63   40.15
 6700.5340.76534 6922.3640.72925 7912.81   42.36 8048.97   36.01 8194.67   40.45
#Mann= 7 ,-1 , 0
       0     .07       0 5736.35     .12       0  6349.8     .07       0
 6553.27    .041       0  6578.6     .12       0 6700.53     .07       0
 6922.36     .15       0
#Block Obstruct= 2 ,-1
  204.78 5756.54   37.95 7893.08 8333.57   38.19
Bank Sta=6473.36,6613.67
XS Rating Curve= 0
Exp/Cntr=.3,.1

Type RM Length L Ch R = 1 ,155128.0,834.62,690.8,593.9
XS GIS Cut Line= 6
     3164691.044    13773755.604     3162103.391    13770186.501
     3162781.156     13769105.69     3162830.231     13769080.63
     3163162.023    13769134.303     3163921.248    13767767.214
#Sta/Elev= 30
       0    39.7  809.62   37.65  859.02   49.69 1017.85   46.43  1081.9   37.65
 1700.79   39.79 1814.74   33.47 2022.23   43.04 3028.93   37.15 4666.75   42.53
 4956.45   39.01 4986.34   32.15 5166.78   34.38 5213.58   40.54 5245.1336.98446
 5625.92   31.73 5700.22   36.15  5719.631.41691 5740.98   42.03 5757.95   42.73
 5808.92   34.11 5821.91   26.97 5890.7914.81479 5903.51   14.37 5909.8916.84936
 5971.84   33.06 6008.84   39.71 6071.77    34.5 6551.4339.50054 7639.17   40.08
#Mann= 7 ,-1 , 0
       0     .07       0 5245.13     .12       0  5719.6     .07       0
 5890.79    .041       0 5909.89     .12       0 5971.84     .07       0
 6551.43     .15       0
#Block Obstruct= 2 ,-1
  227.53  2147.9   37.78 6036.02 6559.36   37.51
Bank Sta=5808.92,5971.84
XS Rating Curve= 0
Exp/Cntr=.3,.1

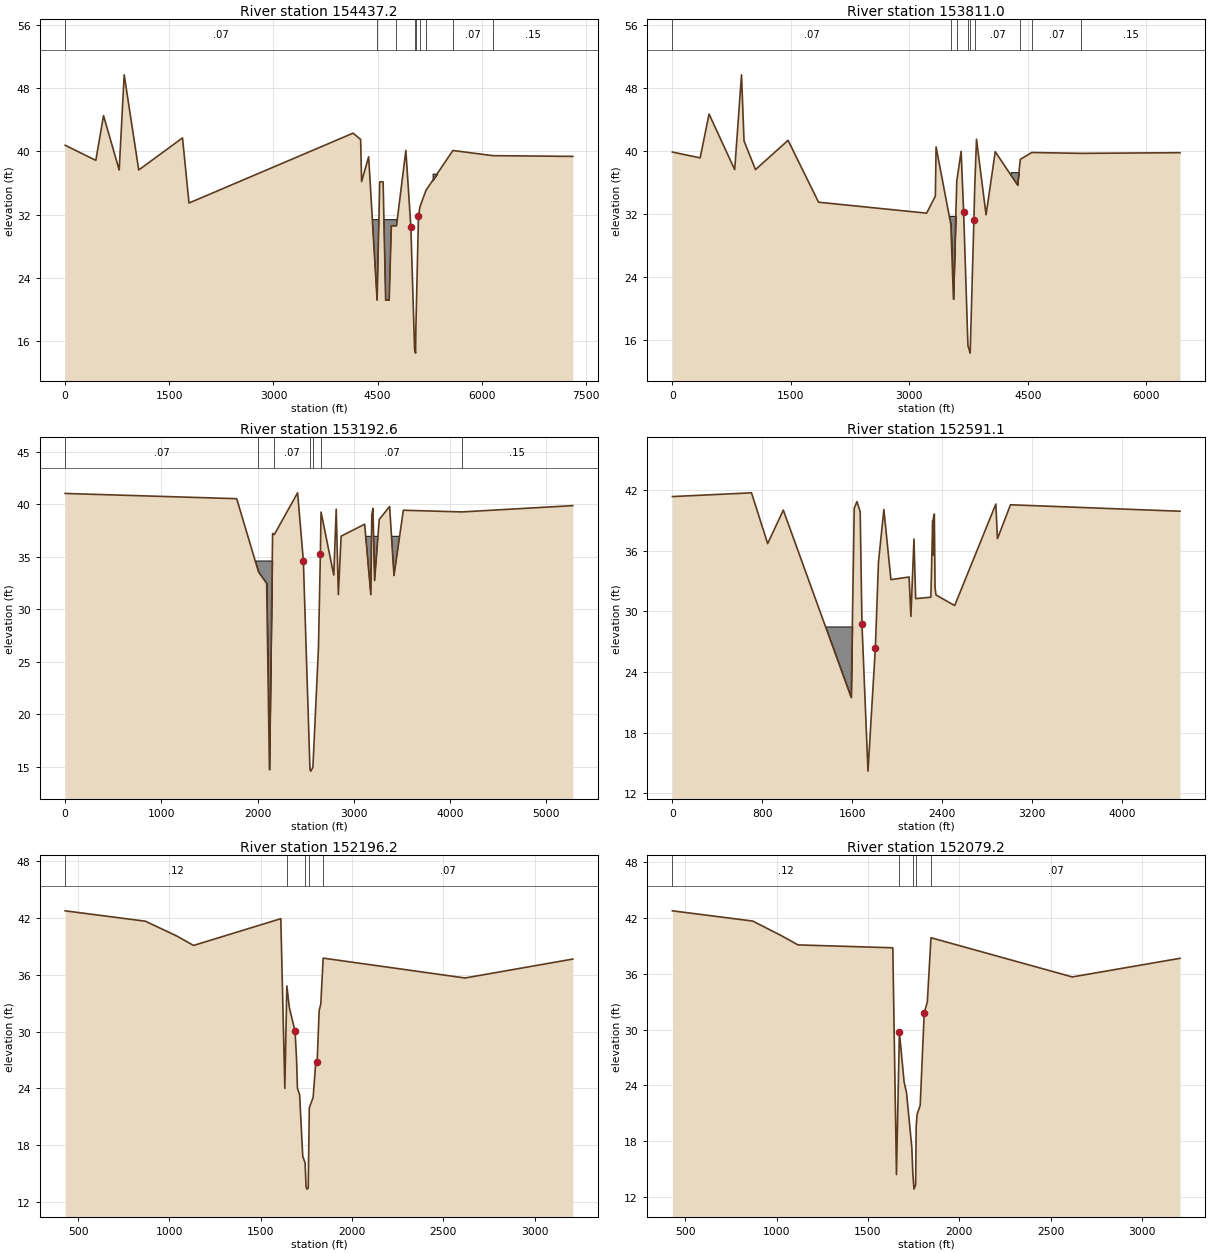
Type RM Length L Ch R = 1 ,154437.2,860.33,626.18,489.97
XS GIS Cut Line= 6
     3164691.044    13773633.435     3162298.399    13770114.799
     3162839.989    13769802.766     3163125.016    13769755.144
     3163240.204    13769684.796     3164004.832    13767829.902
#Sta/Elev= 30
       0   40.78  441.54   38.87  552.41   44.53     778   37.65  849.86   49.69
 1059.52   37.65 1689.84   41.71  1783.2   33.47 4146.33   42.31 4255.09   41.51
 4269.14   36.19 4370.62   39.32 4492.33   21.19 4530.25   36.15 4579.02   36.15
  4615.4   21.19 4666.37   21.19 4697.37   30.59 4771.59   30.59 4906.57   40.12
 4978.44   30.46 5032.4314.86431  5046.7   14.48 5050.4117.47886 5088.01    31.8
 5110.3633.01531 5195.8935.07022 5584.1540.11802 6157.3639.46497 7310.43   39.37
#Mann= 9 ,-1 , 0
       0     .07       0 4492.33     .12       0 4771.59     .07       0
 5032.43    .041       0 5050.41     .12       0 5110.36     .07       0
 5195.89     .12       0 5584.15     .07       0 6157.36     .15       0
#Block Obstruct= 3 ,-1
 4335.88 4873.28   31.36 5291.24 5647.87   37.19 6260.45 6910.39    37.7
Bank Sta=4978.44,5088.01
XS Rating Curve= 0
Exp/Cntr=.3,.1

Type RM Length L Ch R = 1 ,153811.0,1044.35,618.4,423.52
XS GIS Cut Line= 6
     3164711.405    13773490.906      3162922.25    13770694.758
     3163103.471    13770446.832     3163279.126    13770251.661
     3163459.135    13770073.222     3164085.184    13767874.942
#Sta/Elev= 30
       0   39.88  351.07   39.14  464.04   44.71  788.61   37.65  875.09   49.69
  906.99    41.3 1051.93   37.65 1464.77   41.37 1850.66   33.51 3218.87   32.12
 3329.79   34.28 3339.07   40.54 3526.0430.68806 3559.13   21.19 3601.1236.17601
 3656.38   39.97 3687.89   32.28 3742.5515.28711 3768.5214.43331 3770.77   14.34
 3818.01   31.28 3828.2435.27913 3851.02   41.51  3971.9   31.91 4088.41   39.93
 4370.89   35.69 4405.97   38.96 4551.0739.82491 5176.9539.71503 6428.51    39.8
#Mann= 9 ,-1 , 0
       0     .07       0 3526.04     .12       0 3601.12     .07       0
 3742.55    .041       0 3768.52     .12       0 3828.24     .07       0
 4405.97     .12       0 4551.07     .07       0 5176.95     .15       0
#Block Obstruct= 2 ,-1
 3419.85 3612.21   31.78 4282.58 6547.11   37.32
Bank Sta=3687.89,3818.01
XS Rating Curve= 0
Exp/Cntr=.3,.1

Type RM Length L Ch R = 1 ,153192.6,506.74,601.51,400.16
XS GIS Cut Line= 5
     3164729.385    13772953.678     3163635.314    13770817.659
     3163728.021    13770646.883     3163796.331    13770549.297
      3164167.62    13768012.335
#Sta/Elev= 30
       0   41.04 1783.13   40.54 2009.87   33.57 2094.56   32.47 2123.77   14.73
 2156.63   37.22 2173.92   37.12 2416.42    41.1 2476.25   34.64 2545.21   14.72
 2554.17   14.58 2575.44   14.94 2633.04   26.28 2653.34   35.26 2660.07   39.27
 2792.69   33.26 2817.88   39.54    2840    31.4    2869   36.97 3113.55   38.11
 3177.61    31.4 3187.63   38.97  3199.5   39.62 3217.09   32.74 3265.13   38.56
 3373.03    39.8 3418.55   33.22 3515.64   39.44 4124.73   39.28 5277.33   39.88
#Mann= 7 ,-1 , 0
       0     .07       0 2009.87     .12       0 2173.92     .07       0
 2545.21    .041       0 2575.44     .12       0 2660.07     .07       0
 4124.73     .15       0
#Block Obstruct= 2 ,-1
 1859.54 2198.47   34.65 3089.42  3700.4   36.96
Bank Sta=2476.25,2653.34
XS Rating Curve= 0
Exp/Cntr=.3,.1

Type RM Length L Ch R = 1 ,152591.1,354.9,394.9,363.9
XS GIS Cut Line= 4
      3164935.38    13772493.198     3164294.018     13771012.83
     3164220.829      13770666.4     3164305.013    13768122.249
#Sta/Elev= 30
       0   41.35  703.18   41.72  846.93    36.7   985.8   40.01  1589.3   21.49
 1616.44    40.2 1640.59   40.85 1669.43   39.84 1685.11   28.77 1738.72   14.21
 1804.48   26.43 1831.88   34.86 1879.94   40.07 1942.46   33.14 2104.17    33.4
 2120.16    29.5  2147.5   37.15 2162.45   31.26 2297.76    31.4  2313.7   38.97
 2319.79   35.57 2319.86   39.23 2328.62   39.62 2334.96   32.34 2343.27   31.62
 2509.57   30.58 2875.43   40.61 2889.76   37.19 3005.55   40.54 4512.95    39.9
#Mann= 0 ,-1 , 0
#Block Obstruct= 1 ,-1
 1358.78 1625.95   28.51
Bank Sta=1685.11,1804.48
XS Rating Curve= 0
Vertical n Elevations= 2
      32      38
Vertical n for Station=0
     .07      .1
Vertical n for Station=660.74
     .12     .24
Vertical n for Station=1640.59
     .07      .1
Vertical n for Station=1738.72
    .041    .041
Vertical n for Station=1755.14
     .12     .24
Vertical n for Station=2012.82
     .07      .1
Vertical n for Station=3297.79
     .15     .15
Vertical n Flow= 0
Exp/Cntr=.3,.1

Type RM Length L Ch R = 1 ,152196.2,105,117,108
BEGIN DESCRIPTION:
BBI Survey Data
END DESCRIPTION:
XS GIS Cut Line= 5
 3165037.366816513771828.4033075 3164566.672360613770741.9638079
 3164493.483360613770395.5338079 3164520.356737413769583.3850804
 3164534.554506713769154.3098542
#Sta/Elev= 27
  429.31   42.76  869.31   41.66 1041.31   40.09 1132.31    39.1 1610.31   41.93
 1632.31      24 1643.31   34.82 1657.31    32.5 1688.31   30.04 1696.31   27.17
 1701.31      24 1713.31   23.33 1730.31   16.82 1743.31   16.11 1748.31   13.67
 1752.31   13.34 1760.31   13.44 1766.31   21.92 1768.31   22.04 1787.31   23.04
 1801.31   26.62 1809.31   26.78 1820.31   32.21 1829.31   32.91 1842.31   37.76
 2619.31   35.66 3209.31   37.66
#Mann= 5 ,-1 , 0
  429.31     .12       0 1643.31     .07       0 1743.31    .041       0
 1766.31     .12       0 1842.31     .07       0
Bank Sta=1688.31,1809.31
XS Rating Curve= 0
Exp/Cntr=.3,.1

Type RM Length L Ch R = 1 ,152079.2,187,208,192
BEGIN DESCRIPTION:
BBI Survey Data
END DESCRIPTION:
XS GIS Cut Line= 5
 3165123.232166713771772.2160888 3164652.537710813770685.7765892
 3164579.348710813770339.3465892 3164606.222087613769527.1978617
 3164620.419856913769098.1226355
#Sta/Elev= 21
  429.31   42.76  869.31   41.66 1026.31   40.09 1117.31    39.1 1636.31   38.79
 1656.31   14.43 1672.31   29.71 1698.31   24.36 1711.31   23.24 1740.31   17.36
 1746.31   14.43 1752.31   12.87 1761.31   13.31 1764.31   19.64 1769.31    20.9
 1786.31   21.87 1808.31   31.81 1825.31   32.97 1845.31   39.87 2619.31   35.66
 3209.31   37.66
#Mann= 5 ,-1 , 0
  429.31     .12       0 1672.31     .07       0 1746.31    .041       0
 1764.31     .12       0 1845.31     .07       0
Bank Sta=1672.31,1808.31
XS Rating Curve= 0
Exp/Cntr=.3,.1

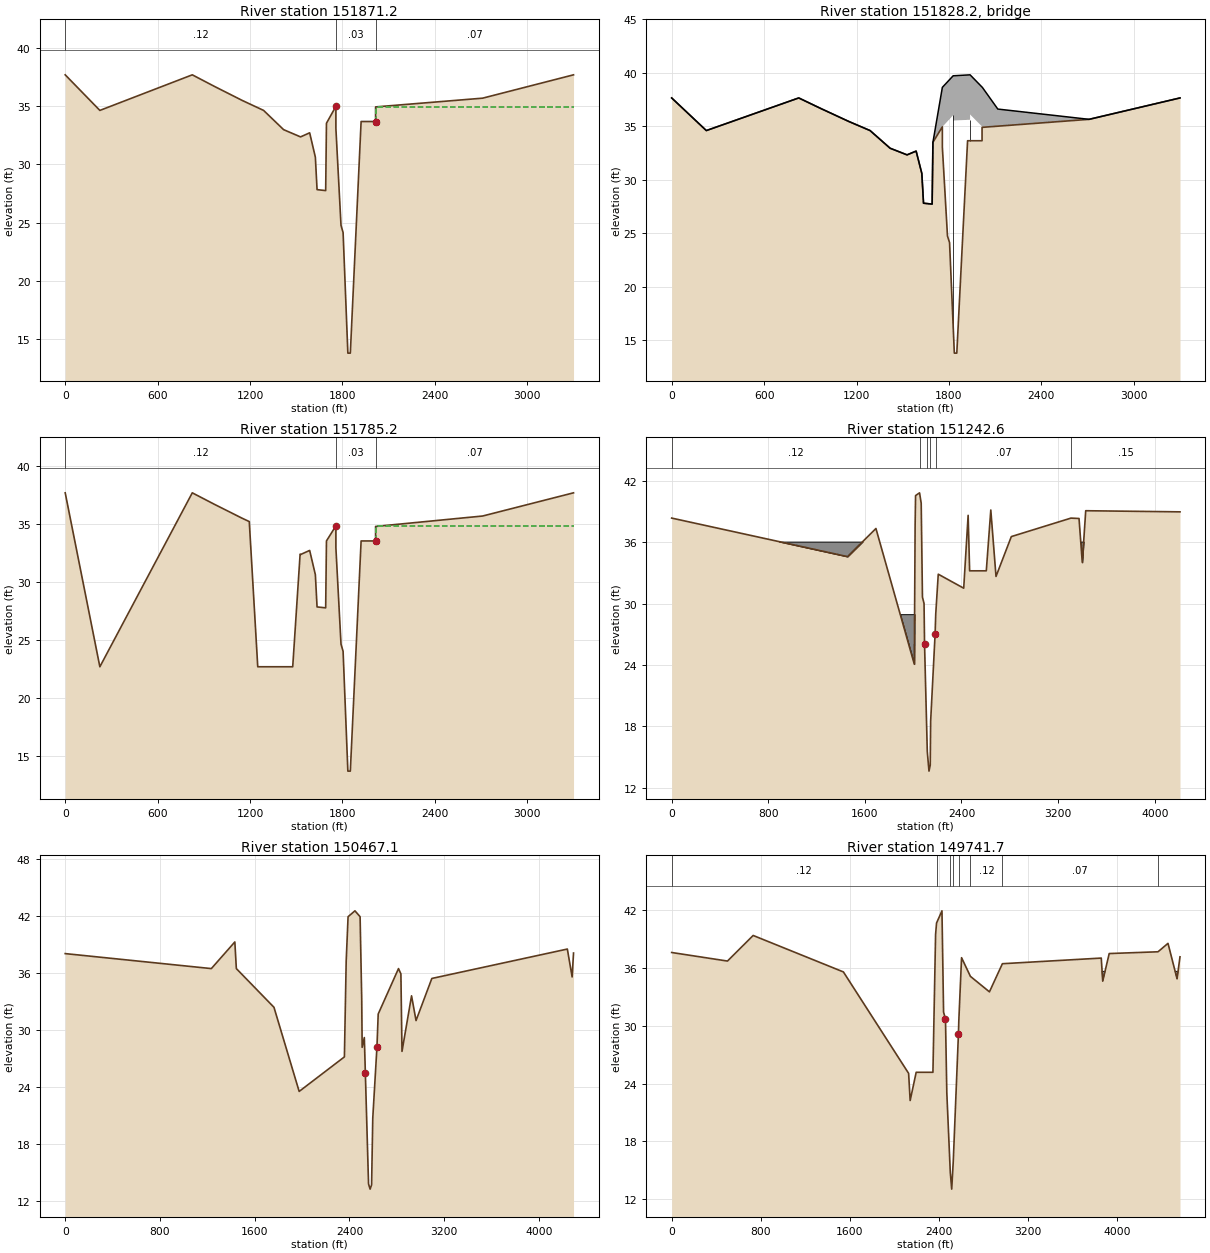
Type RM Length L Ch R = 1 ,151871.2,86,86,86
XS GIS Cut Line= 6
     3165426.638     13772006.72      3164835.62     13770529.78
      3164786.88    13770489.236      3164675.52    13770408.385
      3164580.99    13770345.057 3164477.105572513768954.5296907
#Sta/Elev= 26
       0   37.66     225   34.61     825   37.66     970   36.66    1150   35.46
    1280   34.66    1288   34.61    1418   32.96    1528   32.34    1585   32.68
    1587   32.69    1624    30.6    1635   27.82    1691   27.74    1696   33.51
 1757.25   34.96 1757.25   33.07  1790.5   24.76    1804   24.14    1835   13.81
    1851   13.81    1921   33.66    2015   33.66    2015   34.91    2710   35.66
    3300   37.66
#Mann= 3 ,-1 , 0
       0     .12       0 1757.25     .03       0    2015     .07       0
#XS Ineff= 2 , 0
       0 1757.25   34.96    2015       0   34.91
Permanent Ineff=
       F       F
Bank Sta=1757.25,2015
XS Rating Curve= 0
Exp/Cntr=.3,.1

Type RM Length L Ch R = 3 ,151828.2,,,
BEGIN DESCRIPTION:
Scarsdale Bridge
END DESCRIPTION:
Bridge Culvert--1,0,-1,-1, 0
Deck Dist Width WeirC Skew NumUp NumDn MinLoCord MaxHiCord MaxSubmerge Is_Ogee
5,76,2.6,0, 24, 25, , , .95, 0, 0,0,,
       0     225     825     970    1150    1280    1288    1418    1528    1585
    1587    1624    1635    1691    1696 1757.25 1827.25 1827.25 1937.25 1937.25
 2017.25 2117.25    2710    3300
   37.66   34.61   37.66   36.66   35.46   34.66   34.61   32.96   32.34   32.68
   32.69    30.6   27.82   27.74   33.51   38.65   39.73   39.73   39.82   39.82
   38.64   36.62   35.66   37.66
   37.66   34.61   37.66   36.66   35.46   34.66   34.61   32.96   32.34   32.68
   32.69    30.6   27.82   27.74   33.51   34.96   36.04   35.55   35.62   36.12
   34.95   32.93   35.66   37.66
       0     225     825     970    1150    1195    1250    1477    1525    1528
    1585    1587    1624    1635    1691    1696 1757.25 1827.25 1827.25 1937.25
 1937.25 2017.25 2117.25    2710    3300
   37.66   22.66   37.66   36.66   35.46   35.18   22.66   22.66   32.37   32.34
   32.68   32.69    30.6   27.82   27.74   33.51    38.5   39.58   39.58   39.67
   39.67   38.49   36.47   35.66   37.66
   37.66   22.66   37.66   36.66   35.46   35.18   22.66   22.66   32.37   32.34
   32.68   32.69    30.6   27.82   27.74   33.51   34.81   35.89    35.4   35.47
   35.97    34.8   32.78   35.66   37.66
Pier Skew, UpSta & Num, DnSta & Num=  ,1827.25, 2 ,1827.25, 2 , 0 , 0 , 0 ,,
       3       3
       0   36.04
       3       3
       0   35.89
Pier Skew, UpSta & Num, DnSta & Num=  ,1937.25, 2 ,1937.25, 2 , 0 , 0 , 0 ,,
       3       3
       0   36.12
       3       3
       0   35.97
Pier Skew, UpSta & Num, DnSta & Num=  ,2017.25, 2 ,2017.25, 2 , 0 , 0 , 0 ,,
       3       3
       0   34.95
       3       3
       0    34.8
Pier Skew, UpSta & Num, DnSta & Num=  ,2117.25, 2 ,2117.25, 2 , 0 , 0 , 0 ,,
       3       3
       0   32.96
       3       3
       0   32.81
BR Coef=-1 , 0 , 0 ,, 0 ,,,.8,-1,,0,
WSPro=,,,, 1 ,,,, 0 ,,,, 0 ,,,,-1 ,-1 ,-1 , 0 , 0 , 0 , 0 , 0
BC Design=,, 0 ,, 0 ,,,,,,
BC HTab HWMax=37.66

Type RM Length L Ch R = 1 ,151785.2,494.6,542.6,506.6
XS GIS Cut Line= 6
 3165537.706189113771905.8611872 3164946.688189113770428.9211871
 3164897.948189113770388.3771871 3164786.588189113770307.5261871
 3164692.058189113770244.1981872 3164588.173761613768853.6708779
#Sta/Elev= 27
       0   37.66     225   22.66     825   37.66     970   36.66    1150   35.46
    1195   35.18    1250   22.66    1477   22.66    1525   32.37    1528   32.34
    1585   32.68    1587   32.69    1624    30.6    1635   27.82    1691   27.74
    1696   33.51 1757.25   34.81 1757.25   32.92  1790.5   24.61    1804   23.99
    1835   13.66    1851   13.66    1921   33.51    2015   33.51    2015   34.76
    2710   35.66    3300   37.66
#Mann= 3 ,-1 , 0
       0     .12       0 1757.25     .03       0    2015     .07       0
#XS Ineff= 2 , 0
       0 1757.25   34.81    2015       0   34.76
Permanent Ineff=
       F       F
Bank Sta=1757.25,2015
XS Rating Curve= 0
Exp/Cntr=.3,.1

Type RM Length L Ch R = 1 ,151242.6,422.87,775.44,865.04
XS GIS Cut Line= 6
     3165668.389    13772045.248     3165294.274    13770076.006
     3165258.252    13770031.592      3165113.74    13769885.714
     3164986.945    13769710.544      3164552.32    13768039.813
#Sta/Elev= 30
       0   38.37 1456.31    34.6 1691.53   37.35 2009.23   24.08 2016.08   37.67
 2019.78   40.57 2052.8440.84153 2066.41   39.82 2076.76   30.63 2089.94   30.02
 2094.16   26.01 2116.8715.50771 2130.92   13.61  2141.214.18607 2144.67    18.5
 2181.53   27.02 2186.7528.96298 2207.65   32.88 2418.45   31.51 2455.08   38.64
 2467.46   33.21 2605.51   33.21  2642.8   39.16 2685.92   32.66 2812.85   36.56
 3306.6238.36774 3373.42   38.33 3400.34   34.03 3428.85   39.09 4209.57   38.98
#Mann= 6 ,-1 , 0
       0     .12       0 2052.84     .07       0 2116.87    .051       0
  2141.2     .12       0 2186.75     .07       0 3306.62     .15       0
#Block Obstruct= 3 ,-1
  813.42  1649.6   36.07 1816.79 2030.53   28.97 2986.35 3924.91   36.07
Bank Sta=2094.16,2181.53
XS Rating Curve= 0
Vertical n Elevations= 2
      32      38
Vertical n for Station=0
     .12     .24
Vertical n for Station=2055.91
     .07      .1
Vertical n for Station=2118.78
    .041    .041
Vertical n for Station=2141.27
     .12     .24
Vertical n for Station=2189.16
     .07      .1
Vertical n for Station=3333.98
     .15     .15
Vertical n Flow= 0
Exp/Cntr=.3,.1

Type RM Length L Ch R = 1 ,150467.1,537.5,725.46,799.12
XS GIS Cut Line= 6
     3165770.196    13771963.803     3165699.255    13769529.525
     3165674.858    13769422.181     3165655.341    13769373.388
     3165636.571    13769271.904     3165435.811    13767694.101
#Sta/Elev= 30
       0   38.07 1233.71   36.49  1432.2    39.3 1444.87   36.49  1762.5   32.41
 1975.26   23.54 2357.17   27.18 2372.23   37.26  2388.2   41.96 2446.18   42.58
  2489.7   41.96 2503.37   33.32 2507.08   28.19 2525.45   29.22 2534.05   25.48
 2560.96   13.79  2574.2   13.24 2586.79   13.69 2596.63   20.72 2632.02   28.23
 2642.55    31.7 2813.88   36.49 2834.21   35.93 2843.47   27.76 2924.05   33.62
    2962   31.01 3095.42   35.45 4239.44   38.55  4279.8   35.61 4291.67   38.13
#Mann= 0 ,-1 , 0
Bank Sta=2534.05,2632.02
XS Rating Curve= 0
Vertical n Elevations= 2
      32      38
Vertical n for Station=0
     .12     .24
Vertical n for Station=2446.18
     .07      .1
Vertical n for Station=2555.91
    .041    .041
Vertical n for Station=2596.63
     .12     .24
Vertical n for Station=2612.73
     .07      .1
Vertical n for Station=3683.9
     .15     .15
Vertical n Flow= 0
Exp/Cntr=.3,.1

Type RM Length L Ch R = 1 ,149741.7,644.35,759.87,579.83
XS GIS Cut Line= 5
     3165953.449     13772065.61     3166301.679    13769718.869
     3166392.114    13769490.491     3166406.752    13769456.336
     3166162.229    13767560.889
#Sta/Elev= 30
       0   37.63   501.2   36.74  732.06    39.4 1542.77   35.61 2128.55   25.07
 2142.42   22.25 2196.46   25.18 2346.94   25.18  2370.8    39.5 2379.3640.69031
 2428.12   41.96 2442.55   31.43 2459.66   30.72 2471.68   23.03 2502.9714.76262
 2515.61   13.04 2529.55 15.9246 2576.17   29.21 2579.4130.51025 2604.13   37.09
 2683.7135.14945 2854.51   33.54 2970.9436.46339 3859.06   37.05  3872.2   34.66
  3930.6   37.52 4368.9337.70423 4458.55   38.58 4539.92    34.9 4566.38   37.18
#Mann= 8 ,-1 , 0
       0     .12       0 2379.36     .07       0 2502.97    .051       0
 2529.55     .12       0 2579.41     .07       0 2683.71     .12       0
 2970.94     .07       0 4368.93     .15       0
#Block Obstruct= 1 ,-1
 3084.52 4805.01   35.67
Bank Sta=2459.66,2576.17
XS Rating Curve= 0
Vertical n Elevations= 2
      32      38
Vertical n for Station=0
     .12     .24
Vertical n for Station=2385.75
     .07      .1
Vertical n for Station=2503.65
    .041    .041
Vertical n for Station=2537.94
     .12     .24
Vertical n for Station=2589.9
     .07      .1
Vertical n for Station=2720.64
     .12     .24
Vertical n for Station=2972.72
     .07      .1
Vertical n for Station=4384.79
     .15     .15
Vertical n Flow= 0
Exp/Cntr=.3,.1