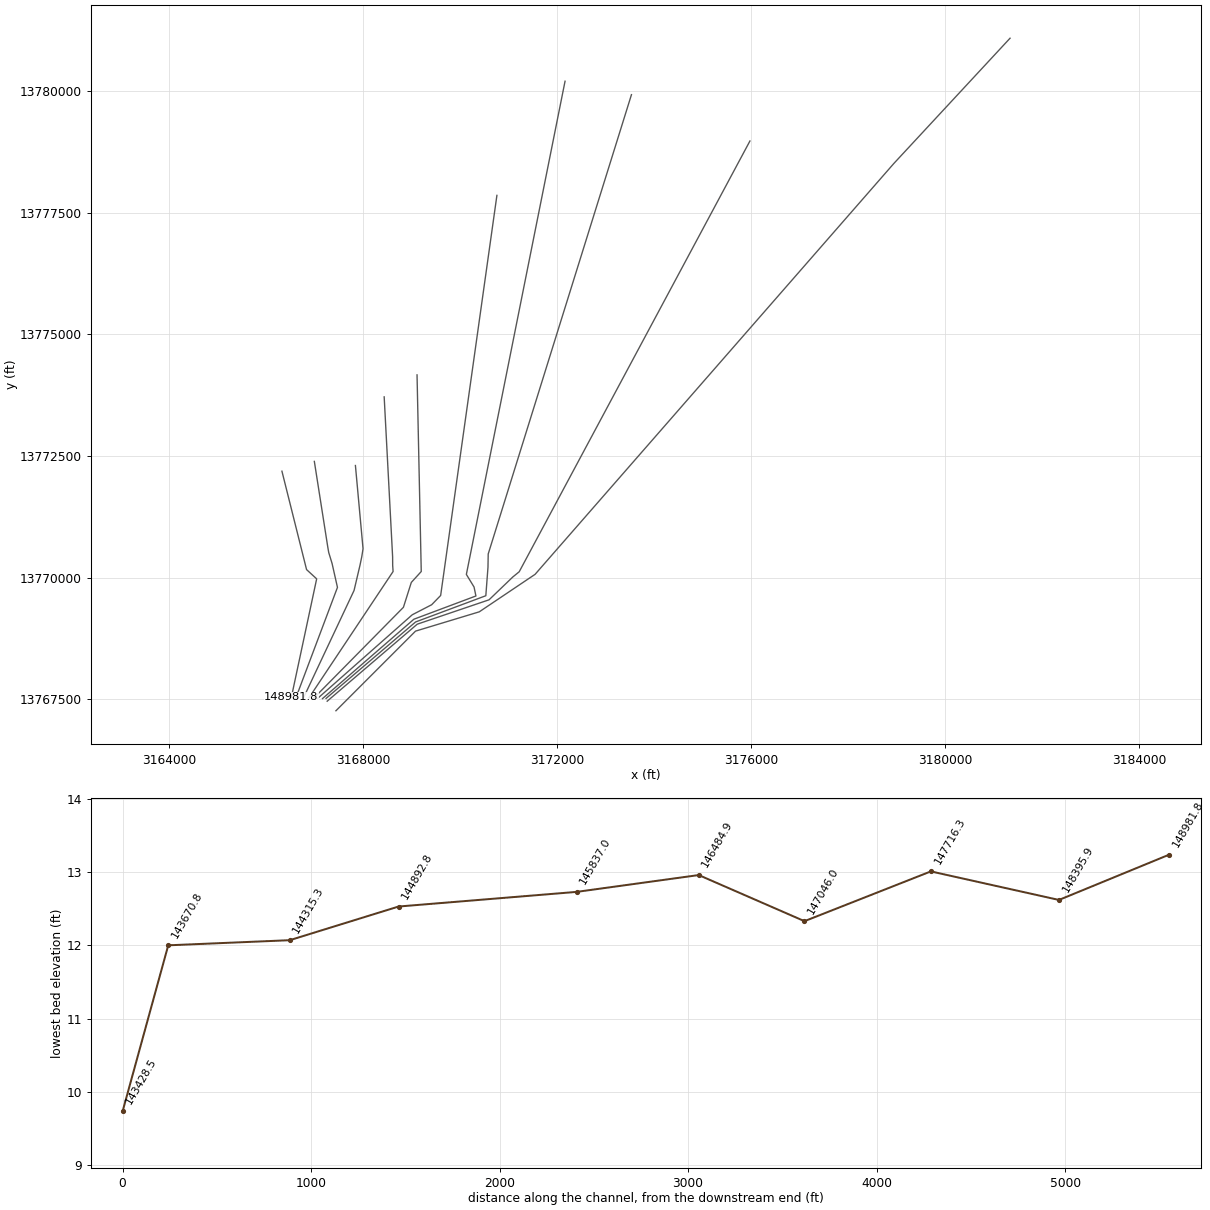
HEC-RAS study A100-00-00.prj: A100-00-00

--- A100-00-00.g01 (geometry) --- (continued)

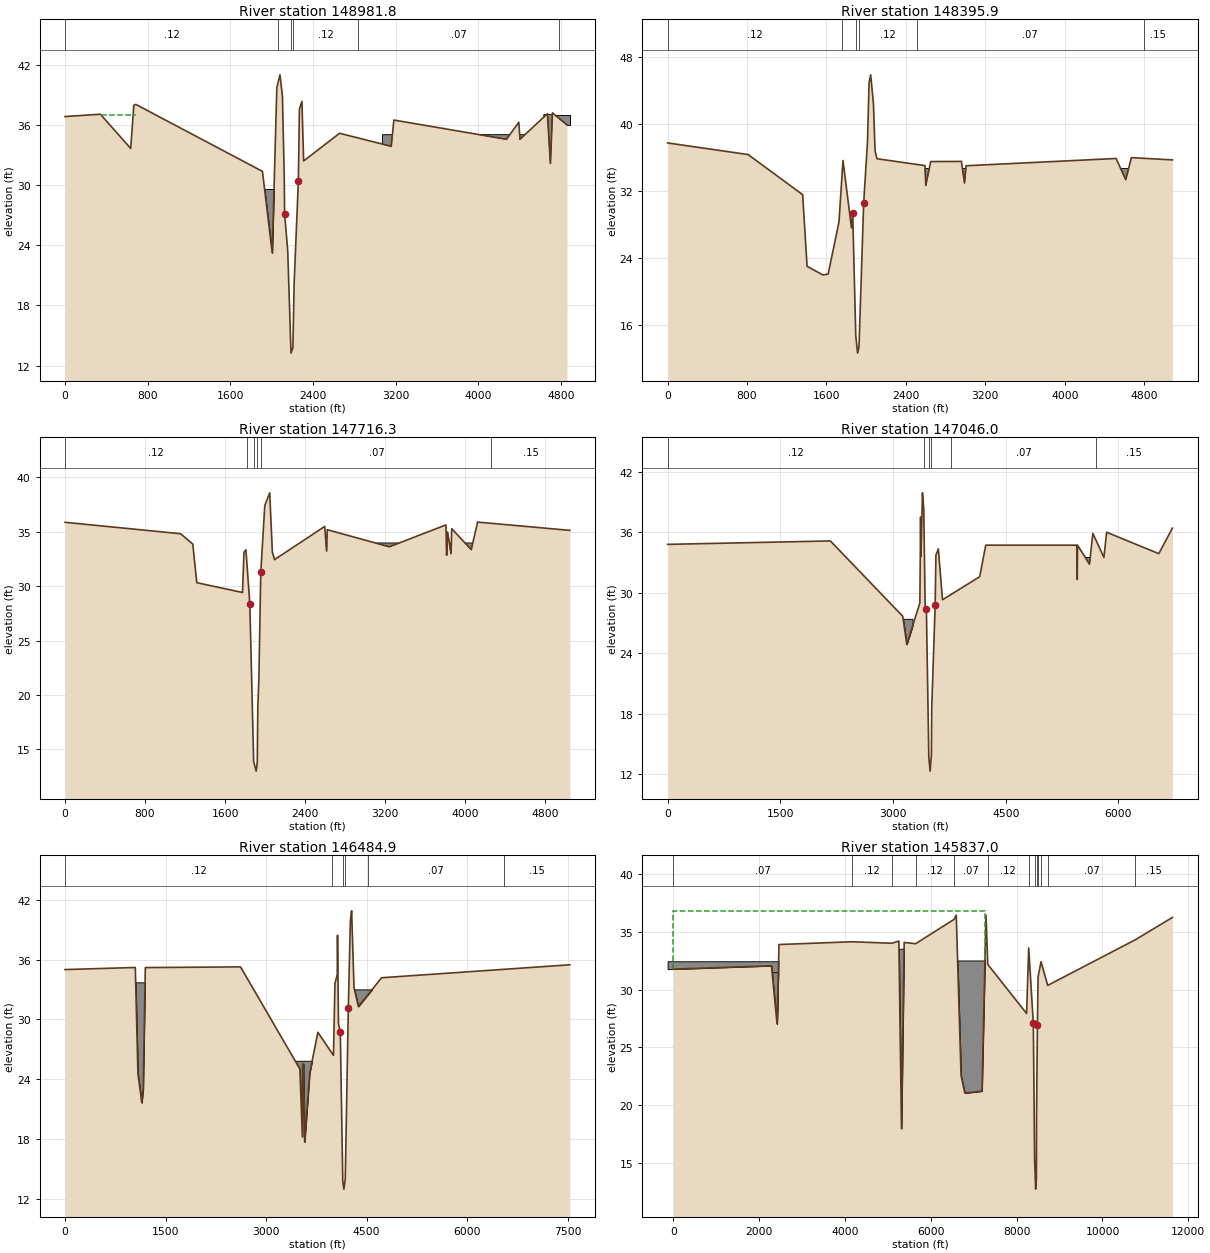
Type RM Length L Ch R = 1 ,148981.8,617.23,585.91,570.33
XS GIS Cut Line= 4
     3166319.953    13772187.778     3166827.969    13770164.309
     3167036.181    13769973.541     3166514.779    13767539.522
#Sta/Elev= 30
       0   36.84  342.18   37.07  635.39   33.66  665.79   37.96  685.18   38.05
 1910.65   31.37 2005.32   23.24 2049.88   39.73 2080.29      41 2104.06   38.86
 2121.32   30.98 2125.28    27.1 2155.39   23.44 2187.09   13.24 2205.34   13.79
 2217.44   20.23 2258.05   30.38 2268.49   37.59 2292.53   38.35  2309.2   32.41
 2657.15   35.17 3156.73   33.87 3182.38   36.49 4272.61   34.57  4391.7   36.27
 4402.82   34.57 4668.55   37.12 4697.62   32.15 4717.35   37.21  4857.9   36.01
#Mann= 6 ,-1 , 0
       0     .12       0 2058.83     .07       0 2183.53    .051       0
 2207.96     .12       0 2836.43     .07       0 4782.65     .15       0
#XS Ineff= 1 ,-1
  358.36  682.59   36.95
Permanent Ineff=
       F
#Block Obstruct= 3 ,-1
  1862.6 2076.34   29.61 3072.25 4605.02   35.03 4633.59  4885.5   37.03
Bank Sta=2125.28,2258.05
XS Rating Curve= 0
Vertical n Elevations= 2
      32      38
Vertical n for Station=0
     .12     .24
Vertical n for Station=2065.61
     .07      .1
Vertical n for Station=2186.14
    .041    .041
Vertical n for Station=2210.6
     .12     .24
Vertical n for Station=2841.98
     .07      .1
Vertical n for Station=4857.9
     .15     .15
Vertical n Flow= 0
Exp/Cntr=.3,.1

Type RM Length L Ch R = 1 ,148395.9,789.51,679.61,369.38
XS GIS Cut Line= 6
     3166988.305    13772388.948     3167265.508    13770627.366
     3167285.025    13770515.142     3167354.259    13770289.398
     3167465.049    13769798.442     3166600.246    13767507.472
#Sta/Elev= 30
       0   37.77  810.91   36.38 1360.21   31.58 1404.76   23.01 1564.96   21.97
 1617.11   22.08 1726.35   28.33 1766.52   35.67 1852.17   27.61 1864.26   29.43
 1895.34    14.7 1913.67   12.62 1928.02   13.39 1974.89   30.57 2013.61   37.99
 2029.21   44.97 2045.46   45.92 2073.25    42.5  2089.5   36.85 2108.83   35.88
  2592.5   35.06  2600.7   32.69 2650.06   35.54 2959.39   35.56 2991.04   32.98
 3005.99   35.04 4517.68   35.91 4615.15   33.37 4671.82   36.01 5085.35   35.74
#Mann= 6 ,-1 , 0
       0     .12       0 1752.77     .07       0 1899.79    .051       0
 1932.59     .12       0 2510.08     .07       0 4795.89     .15       0
#Block Obstruct= 1 ,-1
 2150.47 5152.08   34.71
Bank Sta=1864.26,1974.89
XS Rating Curve= 0
Vertical n Elevations= 2
      30      36
Vertical n for Station=0
     .12     .24
Vertical n for Station=1764.05
     .07      .1
Vertical n for Station=1913.67
    .041    .041
Vertical n for Station=1940.92
     .12     .24
Vertical n for Station=2559.97
     .07      .1
Vertical n for Station=4797.51
     .15     .15
Vertical n Flow= 0
Exp/Cntr=.3,.1

Type RM Length L Ch R = 1 ,147716.3,618.34,670.29,484.28
XS GIS Cut Line= 6
       3167835.4    13772304.238     3167992.522    13770593.211
     3167965.976    13770426.691     3167929.092    13770251.661
     3167807.163    13769734.717     3166760.496    13767518.156
#Sta/Elev= 30
       0   35.88 1155.55   34.83 1277.47   33.88 1317.69   30.33 1774.73   29.43
 1789.44   33.13 1809.13   33.35 1847.95   28.38 1886.28    13.9 1911.41   13.01
 1922.47   13.83 1927.82   18.87 1938.43   21.44 1957.52   31.29 1997.52   37.42
 2046.89   38.59 2073.16   33.16 2095.02   32.45 2596.85    35.5 2615.93   33.24
 2622.34    35.2 3243.14   33.63 3809.21   35.64 3815.92   32.85 3826.01   34.99
 3859.92      33 3867.15   35.29 4062.25   33.37  4125.6    35.9 5048.11   35.14
#Mann= 6 ,-1 , 0
       0     .12       0 1823.43     .07       0 1885.67    .051       0
 1922.32     .12       0 1963.81     .07       0 4263.88     .15       0
#Block Obstruct= 1 ,-1
 2551.57 5506.04   33.98
Bank Sta=1847.95,1957.52
XS Rating Curve= 0
Vertical n Elevations= 2
      30      36
Vertical n for Station=0
     .12     .24
Vertical n for Station=1829.06
     .07      .1
Vertical n for Station=1886.28
    .041    .041
Vertical n for Station=1922.47
     .12     .24
Vertical n for Station=1997.52
     .07      .1
Vertical n for Station=4303.52
     .15     .15
Vertical n Flow= 0
Exp/Cntr=.3,.1

Type RM Length L Ch R = 1 ,147046.0,596.91,561.1,594.02
XS GIS Cut Line= 5
     3168428.366    13773716.063     3168602.434    13770427.315
     3168603.625    13770249.736     3168612.193    13770124.799
     3166878.012    13767528.839
#Sta/Elev= 30
       0   34.81 2166.01   35.15 3129.22   27.68 3182.83   24.89 3356.87   29.01
 3366.57   37.52 3371.12   33.61 3391.31   39.92  3408.4   38.34 3427.71   28.38
 3443.85    28.4  3476.1   13.72  3493.2   12.33 3510.51   13.98 3514.39   18.54
 3560.39   28.78 3570.33   33.74 3602.65   34.36  3658.2   29.32 4152.49    31.6
 4233.67   34.73 5444.49   34.73 5451.08   31.33 5455.22   34.73 5614.07   32.85
 5658.99    35.9 5806.15   33.52 5842.65   36.01 6536.68   33.89 6718.09   36.42
#Mann= 6 ,-1 , 0
       0     .12       0 3415.21     .07       0 3477.55    .051       0
 3511.34     .12       0 3776.84     .07       0 5697.41     .15       0
#Block Obstruct= 2 ,-1
 3109.92 3259.54   27.43 5360.97 6786.21   33.51
Bank Sta=3443.85,3560.39
XS Rating Curve= 0
Vertical n Elevations= 2
      30      36
Vertical n for Station=0
     .12     .24
Vertical n for Station=3420.75
     .07      .1
Vertical n for Station=3493.2
    .041    .041
Vertical n for Station=3513.03
     .12     .24
Vertical n for Station=3838.63
     .07      .1
Vertical n for Station=5702.67
     .15     .15
Vertical n Flow= 0
Exp/Cntr=.3,.1

Type RM Length L Ch R = 1 ,146484.9,599.9,647.87,323.72
XS GIS Cut Line= 5
     3169106.042    13774167.847     3169192.829    13770124.799
     3168987.898    13769900.351     3168825.168    13769388.779
     3166963.479    13767507.472
#Sta/Elev= 30
       0   35.01 1048.38   35.22  1087.6    24.6 1145.21   21.64 1165.85   22.92
 1197.92   35.21  2618.5   35.28 3503.67   25.03  3541.4   18.21 3545.46   25.52
  3558.4   25.52 3575.24   17.69    3650   24.59 3772.48   28.71 4004.96   26.39
 4027.16   33.61 4061.54   34.52 4065.18   38.45 4079.74   29.58 4106.86   28.76
  4143.9   13.73 4160.29   12.96 4180.84   13.99 4226.86   31.17 4256.68   39.86
 4275.66   40.91 4311.34   33.21 4376.38    31.3 4723.58   34.19 7531.47   35.49
#Mann= 6 ,-1 , 0
       0     .12       0 3986.18     .07       0 4142.31    .051       0
 4177.41     .12       0 4513.61     .07       0 6546.73     .15       0
#Block Obstruct= 3 ,-1
   977.1 1319.08   33.73 3358.78 3761.83   25.85 4299.88 7137.72   33.02
Bank Sta=4106.86,4226.86
XS Rating Curve= 0
Vertical n Elevations= 2
      30      36
Vertical n for Station=0
     .12     .24
Vertical n for Station=3999.43
     .07      .1
Vertical n for Station=4143.9
    .041    .041
Vertical n for Station=4180.84
     .12     .24
Vertical n for Station=4534.82
     .07      .1
Vertical n for Station=6582.18
     .15     .15
Vertical n Flow= 0
Exp/Cntr=.3,.1

Type RM Length L Ch R = 1 ,145837.0,531.75,944.22,144.04
BEGIN DESCRIPTION:
Large detention basin on left overbank coded as block
END DESCRIPTION:
XS GIS Cut Line= 5
      3170752.96    13777859.104     3169592.931     13769631.99
     3169407.517    13769441.698     3169007.378    13769235.401
     3167052.273    13767511.597
#Sta/Elev= 30
       0   31.79 2285.09   32.08 2415.32   27.05 2460.27   33.92 4166.03   34.16
 5089.39   34.03 5254.53   34.22 5315.95   17.98 5378.21    34.1 5644.93   33.99
 6540.82    36.1  6591.8   36.47 6704.16   22.58 6792.42   21.05 7192.13   21.22
 7285.57   36.47 7326.32    32.2 8231.12   27.95  8281.1   33.62  8388.6   27.09
 8418.06   15.31 8443.36   12.73 8459.74   13.62 8463.74   19.18 8483.51   26.92
 8499.65   31.13 8568.16   32.43 8723.71   30.3810764.56   34.3311630.88   36.27
#Mann= 13 ,-1 , 0
       0     .07       0 4166.03     .12       0 5089.39     .07       0
 5644.93     .12       0 6540.82     .07       0 7326.32     .12       0
  8281.1     .07       0 8418.06    .051       0 8463.74     .12       0
 8499.65     .07       0 8568.16     .12       0 8723.71     .07       0
10764.56     .15       0
#XS Ineff= 1 ,-1
       0  7262.8   36.84
Permanent Ineff=
       F
#Block Obstruct= 4 ,-1
  -135.4 2680.89   32.47 2216.79 2473.28   31.52 5111.45 5477.86   33.56
  6485.5  7291.6   32.54
Bank Sta=8388.6,8483.51
XS Rating Curve= 0
Vertical n Elevations= 2
      30      36
Vertical n for Station=0
     .07      .1
Vertical n for Station=4166.03
     .12     .24
Vertical n for Station=5089.39
     .07      .1
Vertical n for Station=5644.93
     .12     .24
Vertical n for Station=6540.82
     .07      .1
Vertical n for Station=7326.32
     .12     .24
Vertical n for Station=8281.1
     .07      .1
Vertical n for Station=8418.06
    .041    .041
Vertical n for Station=8463.74
     .12     .24
Vertical n for Station=8499.65
     .07      .1
Vertical n for Station=8568.16
     .12     .24
Vertical n for Station=8723.71
     .07      .1
Vertical n for Station=10764.56
     .15     .15
Vertical n Flow= 0
Exp/Cntr=.3,.1

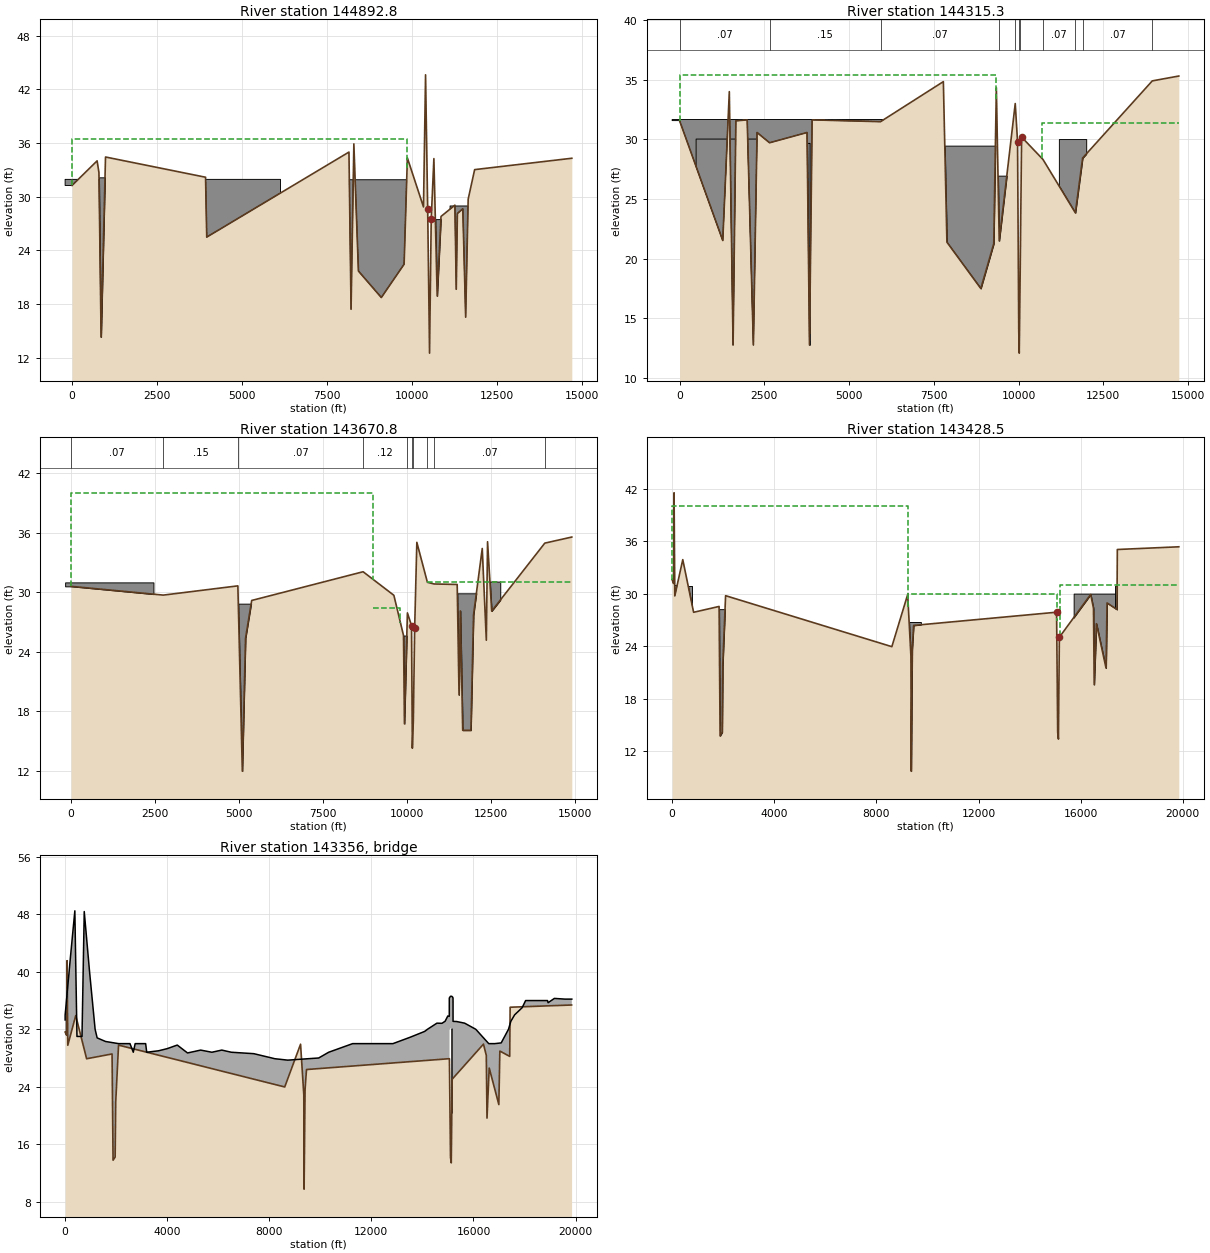
Type RM Length L Ch R = 1 ,144892.8,501.82,577.47,83.78
BEGIN DESCRIPTION:
Large detention basin on left overbank coded as block
END DESCRIPTION:
XS GIS Cut Line= 6
      3172158.03    13780206.033     3170123.001    13770065.153
     3170281.651    13769805.822     3170320.211    13769621.771
     3169041.553    13769144.267     3167156.561    13767511.597
#Sta/Elev= 30
       0   31.26  737.06   34.01   790.8   32.71  854.64   14.33  984.17   34.44
 3925.64   32.18 3960.56   25.49 8141.83   34.99 8203.69   17.44 8286.12    35.9
 8420.42    21.7 9093.56   18.74 9763.57   22.46  9859.5   34.34 10333.5   28.86
10394.07   43.6210456.19   28.6810511.66   12.53 10560.5   27.4810638.93   34.26
   10736   18.9110848.42    27.811256.88   29.0611296.76   19.6711329.84   28.12
11489.45   28.6511573.19   16.5511647.08   29.7311837.03   33.0314694.06    34.3
#Mann= 0 ,-1 , 0
#XS Ineff= 1 ,-1
       0    9850   36.41
Permanent Ineff=
       F
#Block Obstruct= 5 ,-1
 -203.29 6128.45   31.94   537.4   977.1   32.17  7914.5 9844.27    31.9
10601.5310919.08    27.5 11114.511749.62   28.97
Bank Sta=10456.19,10560.5
XS Rating Curve= 0
Vertical n Elevations= 2
      30      36
Vertical n for Station=0
     .07      .1
Vertical n for Station=4464.32
     .15     .15
Vertical n for Station=5555.01
     .07      .1
Vertical n for Station=10182.12
     .12     .24
Vertical n for Station=10424.6
     .07      .1
Vertical n for Station=10489.75
    .041    .041
Vertical n for Station=10526.22
     .12     .24
Vertical n for Station=11043.17
     .07      .1
Vertical n for Station=11401.25
     .12     .24
Vertical n for Station=11711.06
     .07      .1
Vertical n for Station=13867.65
     .15     .15
Vertical n Flow= 0
Exp/Cntr=.5,.3

Type RM Length L Ch R = 1 ,144315.3,824.23,644.55,80.81
BEGIN DESCRIPTION:
Large detention basin on left overbank coded as block
END DESCRIPTION:
XS GIS Cut Line= 6
     3173527.325    13779929.525     3170573.668    13770485.867
     3170568.789    13770212.626     3170524.393     13769626.96
     3169075.729    13769087.308     3167230.256    13767515.238
#Sta/Elev= 30
       0   31.58 1274.71   21.52 1468.21   34.01  1579.1   12.76 1661.62   31.56
  1995.1   31.64 2178.05   12.76 2286.72   30.58 2654.91   29.72 3760.11   30.58
 3832.82   12.76 3911.02   31.64 5927.77   31.49 7781.06   34.85 7885.78   21.38
 8885.95   17.49 9267.23   21.25 9343.94   34.34  9428.5   21.49 9900.98   33.01
 9968.92   29.8210004.45   13.9610018.95   12.0710039.31   16.8410088.56    30.2
10718.87   28.3211674.84   23.84 11888.5   28.4413942.27   34.9114725.61   35.32
#Mann= 11 ,-1 , 0
       0     .07       0 2654.91     .15       0 5927.77     .07       0
  9428.5     .12       0 9900.98     .07       010004.45    .051       0
10039.31     .12       010718.87     .07       011674.84     .12       0
 11888.5     .07       013942.27     .15       0
#XS Ineff= 2 ,-1
       0 9337.88   35.4210676.9514725.61    31.4
Permanent Ineff=
       F       F
#Block Obstruct= 6 ,-1
 -218.37 6364.42   31.67  488.55 2418.32   30.03 3419.85 3835.11   29.71
  7645.8 9355.73   29.48 9355.73 9917.56   26.9611187.7911993.89   30.03
Bank Sta=9968.92,10088.56
XS Rating Curve= 0
Vertical n Elevations= 2
      29      35
Vertical n for Station=0
     .07      .1
Vertical n for Station=2654.91
     .15     .15
Vertical n for Station=5927.77
     .07      .1
Vertical n for Station=9428.5
     .12     .24
Vertical n for Station=9900.98
     .07      .1
Vertical n for Station=10004.45
    .041    .041
Vertical n for Station=10039.31
     .12     .24
Vertical n for Station=10718.87
     .07      .1
Vertical n for Station=11674.84
     .12     .24
Vertical n for Station=11888.5
     .07      .1
Vertical n for Station=13942.27
     .15     .15
Vertical n Flow= 0
Exp/Cntr=.5,.3

Type RM Length L Ch R = 1 ,143670.8,402.78,242.24,226.97
XS GIS Cut Line= 6
     3175970.422    13778977.132     3171212.856     13770119.92
     3171081.115    13770012.575     3170590.839     13769542.98
     3169109.904     13769041.74     3167253.039    13767458.279
#Sta/Elev= 30
       0   30.59 2747.95   29.71 4966.48   30.64 5099.31      12 5195.26   25.37
  5377.9   29.17 8694.66   32.06 9610.39   29.69 9897.05   25.65 9924.74   16.77
10013.27   27.9210135.83   26.6510160.16   14.3110189.48   17.0710229.27   26.39
10293.81   35.0210607.92      3110806.18   30.83 11494.8   30.7811550.17   19.67
11590.12   28.1211658.86   16.1111903.19   16.1111981.57   27.72 12240.9    34.4
12362.29   25.1712398.85   35.0812522.06    28.114102.93   34.9414906.75   35.55
#Mann= 10 ,-1 , 0
       0     .07       0 2747.95     .15       0 4966.48     .07       0
 8694.66     .12       010013.27     .07       010160.16    .051       0
10189.48     .07       010607.92     .12       010806.18     .07       0
14102.93     .15       0
#XS Ineff= 3 ,-1
       0    9000      40    9000  9804.6   28.3710608.3914906.75      31
Permanent Ineff=
       T       F       F
#Block Obstruct= 5 ,-1
  -175.5 2453.11   30.99 4958.78 5374.05   28.85 9851.6610004.12   25.64
11392.57 12160.3   29.8912419.0812777.25   31.07
Bank Sta=10135.83,10229.27
XS Rating Curve= 0
Vertical n Elevations= 2
      28      34
Vertical n for Station=0
     .07      .1
Vertical n for Station=2747.95
     .15     .15
Vertical n for Station=4966.48
     .07      .1
Vertical n for Station=8694.66
     .12     .24
Vertical n for Station=10013.27
     .07      .1
Vertical n for Station=10160.16
    .041    .041
Vertical n for Station=10189.48
     .07      .1
Vertical n for Station=10607.92
     .12     .24
Vertical n for Station=10806.18
     .07      .1
Vertical n for Station=14102.93
     .15     .15
Vertical n Flow= 0
Exp/Cntr=.5,.3

Type RM Length L Ch R = 1 ,143428.5,102.64,82.25,204.05
XS GIS Cut Line= 6
     3181334.116    13781090.381     3178937.775    13778514.591
     3171540.465    13770066.997     3170389.525    13769295.967
     3169074.961    13768899.285     3167433.546    13767261.756
#Sta/Elev= 30
       0   31.61   57.06   31.18   75.45   41.55   104.5   29.77  416.59   33.91
  841.12   27.89 1838.84   28.56 1878.44   13.76 1959.84   14.19 1982.45   21.83
 2093.45   29.79 8604.77   23.96 9225.05   29.92 9352.01   22.86 9363.31    9.73
 9402.39   23.64 9457.95   26.3915056.84    27.915099.89   14.1715129.12   13.39
 15165.7   25.0416392.17   29.9316502.19   28.3616530.04   19.6216617.28   26.59
16994.11   21.5117033.79   28.9617420.96   28.2217436.22   35.0719844.19   35.38
#Mann= 0 ,-1 , 0
#XS Ineff= 3 ,-1
       0    9250      40    9250   15060      3015191.9219844.19      31
Permanent Ineff=
       T       F       F
#Block Obstruct= 5 ,-1
     -73  786.42   30.95 1618.32  2137.4   28.25 8916.03 9740.46   26.78
15725.1917587.79   30.0317346.7417615.27   30.91
Bank Sta=15056.84,15165.7
XS Rating Curve= 0
Vertical n Elevations= 2
      26      32
Vertical n for Station=0
     .07      .1
Vertical n for Station=13405.15
     .12     .24
Vertical n for Station=15056.84
     .07      .1
Vertical n for Station=15129.12
    .041    .041
Vertical n for Station=15143.81
     .07      .1
Vertical n for Station=15688.4
     .07      .1
Vertical n for Station=19469.34
     .15     .15
Vertical n Flow= 0
Exp/Cntr=.5,.3

Type RM Length L Ch R = 3 ,143356  ,,,
BEGIN DESCRIPTION:
Dixie Farm Rd
END DESCRIPTION:
Bridge Culvert--1,0,-1,-1, 0
Deck Dist Width WeirC Skew NumUp NumDn MinLoCord MaxHiCord MaxSubmerge Is_Ogee
5,71,2.6,0, 69, 69, , , .95, 0, 0,0,,
       0       1     207     381     464     661     749     958    1175    1255
    1583    2092    2541    2671    2744    3155    3197    3656    3998    4394
    4796    5311    5748    6139    6512    7394    8098    8213    8721    9935
   10327   11265   11393   11622   12305   12845   13526   14086   14198   14567
   14765   14889   14995   15052   15053   15060   15061   15101   15151   15191
   15192   15199   15200   15337   15655   16090   16598   16831   17086   17372
   17463   17610   17906   18043   18901   18923   19170   19584   19853
    33.3      34      42    48.5      31      31    48.4      40      32    30.8
    30.3      30      30    28.8      30      30    28.8      29    29.3    29.8
    28.7    29.1    28.8    29.1    28.8    28.6      28    27.9    27.7      28
    28.8      30      30      30      30      30    30.9    31.7      32   32.85
   32.83   33.12   33.85    33.8   36.34    36.4    36.4    36.6   36.59   36.44
   36.44   36.31    33.1   33.08   32.85      32      30      30    30.1      32
    33.1      34      35      36      36    35.7    36.3    36.2    36.2
                                                                                
                                                                                
                                                                                
                                                                                
                                                   31.95   32.12   32.16   32.02
                                                                                
                                                                        
       0      59     265     439     522     719     807    1016    1233    1313
    1641    2150    2599    2729    2802    3213    3255    3714    4056    4452
    4854    5369    5806    6197    6570    7452    8156    8271    8779    9993
   10385   11323   11451   11680   12363   12903   13584   14144   14256   14625
   14823   14947   15053   15110   15111   15118   15119   15159   15209   15249
   15250   15257   15258   15395   15713   16148   16656   16889   17144   17430
   17521   17668   17964   18101   18959   18981   19228   19642   19911
    33.3      34      42    48.5      31      31    48.4      40      32    30.8
    30.3      30      30    28.8      30      30    28.8      29    29.3    29.8
    28.7    29.1    28.8    29.1    28.8    28.6      28    27.9    27.7      28
    28.8      30      30      30      30      30    30.9    31.7      32   32.85
   32.83   33.12   33.85    33.8   36.34    36.4    36.4    36.6   36.59   36.44
   36.44   36.31    33.1   33.08   32.85      32      30      30    30.1      32
    33.1      34      35      36      36    35.7    36.3    36.2    36.2
                                                                                
                                                                                
                                                                                
                                                                                
                                                   31.95   32.12   32.16   32.02
                                                                                
                                                                        
Pier Skew, UpSta & Num, DnSta & Num=  ,15101, 2 ,15159, 2 , 0 , 0 , 0 ,,
    1.33    1.33
     -30      34
    1.33    1.33
     -30      34
Pier Skew, UpSta & Num, DnSta & Num=  ,15151, 2 ,15209, 2 , 0 , 0 , 0 ,,
    1.33    1.33
       0      34
    1.33    1.33
       0      34
Abutment Skew #Up #Dn= , 2 , 2
   15060   15090
      30      17
   15119   15120
      30      17
BR Coef=-1 , 1 , 1 ,1.25, 0 ,,,.8,-1,2,0,
WSPro=,,,, 1 ,,,, 0 ,,,, 0 ,,,,-1 ,-1 ,-1 , 0 , 0 , 0 , 0 , 0
BC Design=,, 0 ,, 0 ,,,,,,
BC HTab HWMax=41.55