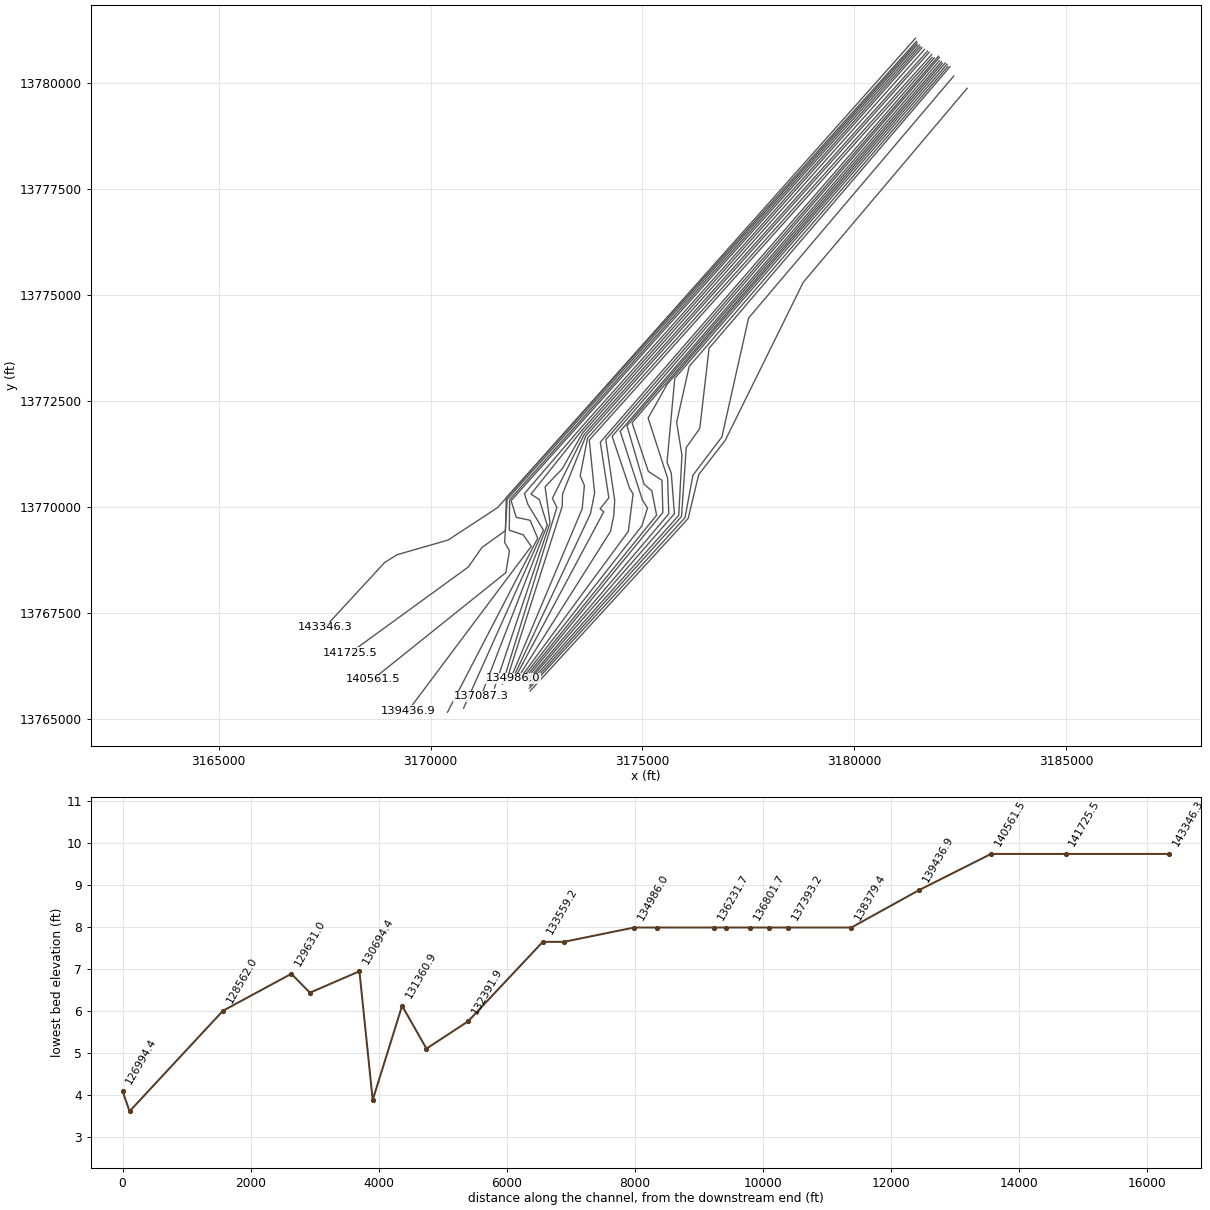
HEC-RAS study A100-00-00.prj: A100-00-00

--- A100-00-00.g01 (geometry) --- (continued)

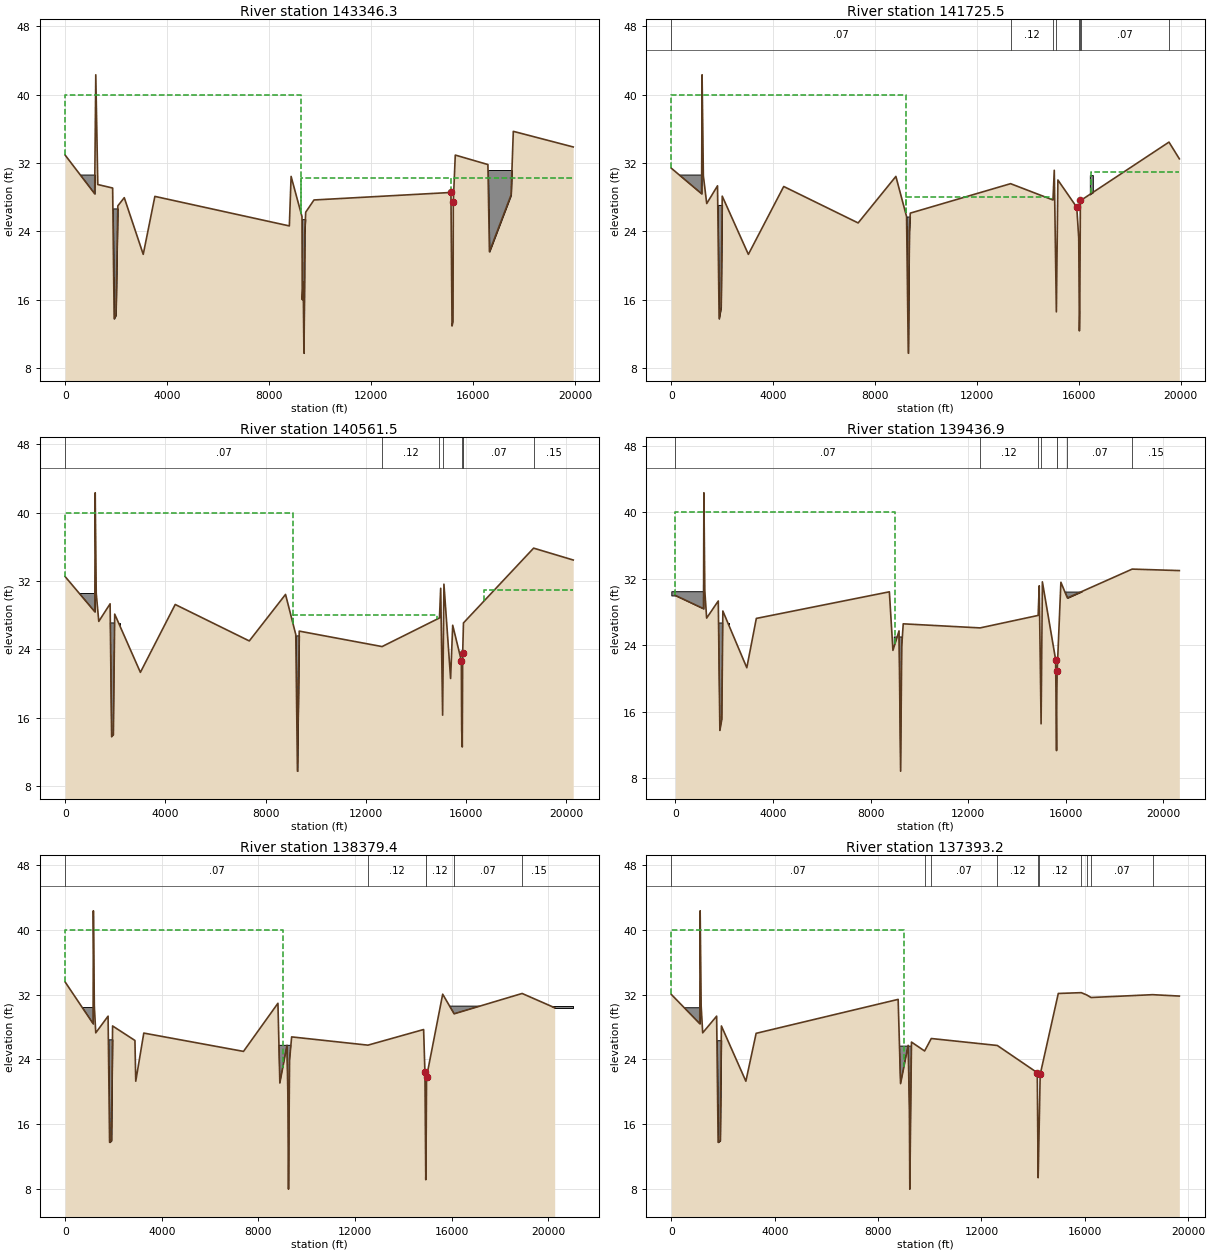
Type RM Length L Ch R = 1 ,143346.3,78.46,1620.78,1342.6
XS GIS Cut Line= 6
     3181439.025    13781051.731     3171582.891    13769982.146
     3170416.208    13769217.698      3169212.43    13768870.863
     3168918.422    13768687.603     3167506.021    13767156.019
#Sta/Elev= 30
       0   32.92 1155.71    28.4 1199.03   42.33 1277.72   29.48 1860.14   29.07
 1919.88   13.76 1989.63   14.19 2062.99   26.98 2316.09   27.94 3059.49    21.3
 3515.98   28.09 8787.21   24.63 8856.11   30.43 9283.02   25.72 9293.09   15.99
 9331.08   18.05 9358.11    9.73 9390.56   23.93 9428.78   26.24 9752.74   27.67
15121.73   28.5515164.53   12.9115204.07   13.3915213.93   27.4215292.15   32.93
16570.75   31.8216630.63   21.6117478.68   28.25 17566.8   35.7119914.91   33.88
#Mann= 0 ,-1 , 0
#XS Ineff= 3 ,-1
       0    9250      40    9250   15118    30.315251.6319914.91    30.3
Permanent Ineff=
       T       F       F
#Block Obstruct= 4 ,-1
 -156.63  1230.3   30.65 1679.39 2167.94   26.68 9099.24 9435.11   25.42
16458.0217679.39   31.18
Bank Sta=15121.73,15213.93
XS Rating Curve= 0
Vertical n Elevations= 2
      26      31
Vertical n for Station=0
     .07      .1
Vertical n for Station=13564.72
     .12     .24
Vertical n for Station=15080.45
     .07      .1
Vertical n for Station=15158.72
    .041    .041
Vertical n for Station=15204.07
     .07      .1
Vertical n for Station=16699.31
     .12     .24
Vertical n for Station=17146.14
     .07      .1
Vertical n for Station=17624.15
     .15     .15
Vertical n for Station=17912.5
     .07      .1
Vertical n for Station=18778.86
     .15     .15
Vertical n Flow= 0
Exp/Cntr=.5,.3

Type RM Length L Ch R = 1 ,141725.5,78.27,1163.99,829.34
XS GIS Cut Line= 6
     3181461.845    13780978.215     3171786.979    13770215.097
      3171767.48    13769439.296     3171212.856    13769041.596
     3170893.102    13768582.589      3168102.82    13766554.602
#Sta/Elev= 30
       0   31.39 1188.76    28.4 1207.52   42.33 1257.33   30.51 1389.87   27.25
 1813.89   29.33 1876.15   13.76 1953.27   15.12 1998.25   28.12  3024.4    21.3
 4412.36   29.25 7333.66   24.98 8815.13   30.43 9234.38   25.73 9301.65    9.73
 9342.41   23.93 9381.09   26.1313317.25   29.5814982.21   27.6715032.96   31.15
15115.04   14.5715175.03   30.0115915.16   26.8215993.37    23.216018.94   12.34
16034.57   14.3416058.05   27.7116074.95   27.6219535.99   34.4519942.51   32.49
#Mann= 8 ,-1 , 0
       0     .07       013317.25     .12       014982.21    .042       0
15115.04     .12       016018.94    .081       016034.57     .12       0
16074.95     .07       019535.99     .15       0
#XS Ineff= 3 ,-1
       0    9200      40    920014921.05      2816491.6619942.51      31
Permanent Ineff=
       T       F       F
#Block Obstruct= 4 ,-1
 -211.95 1216.87   30.65 1618.32 2106.87   27.09 9038.17 9435.11   25.73
16428.0216546.03   30.58
Bank Sta=15915.16,16058.05
XS Rating Curve= 0
Vertical n Elevations= 2
      26      31
Vertical n for Station=0
     .07      .1
Vertical n for Station=13317.25
     .12     .24
Vertical n for Station=14982.21
    .042    .042
Vertical n for Station=15115.04
     .12     .24
Vertical n for Station=16018.94
    .041    .041
Vertical n for Station=16034.57
     .12     .24
Vertical n for Station=16074.95
     .07      .1
Vertical n for Station=19535.99
     .15     .15
Vertical n Flow= 0
Exp/Cntr=.5,.3

Type RM Length L Ch R = 1 ,140561.5,97.87,1124.61,315.41
XS GIS Cut Line= 6
     3181474.915    13780944.061     3171809.763    13770180.921
     3171748.157     13769162.54     3171861.802    13768963.527
     3171777.898    13768448.755      3168641.13    13765933.476
#Sta/Elev= 30
       0   32.51 1182.24    28.4 1198.06   42.33 1239.13   30.56 1341.33   27.27
 1793.25   29.33 1854.66   13.76 1924.13   13.97 1977.06   28.12 3002.48    21.3
 4392.87   29.25 7350.41   24.98 8797.81   30.43 9206.69   25.73 9273.08    9.73
 9344.03   26.1312652.23   24.3214943.37   27.6714992.81   31.1515070.05   16.29
15121.92   31.6315388.47   20.5815472.19   26.8215816.33   22.6815831.29    14.5
15854.21   12.5615871.09   23.57 15901.9   27.0918702.92   35.8520283.78   34.46
#Mann= 8 ,-1 , 0
       0     .07       012652.23     .12       014943.37    .042       0
15070.05     .12       015831.29    .081       015871.09     .12       0
 15901.9     .07       018702.92     .15       0
#XS Ineff= 3 ,-1
       0    9100      40    910014859.08      2816705.7220283.78      31
Permanent Ineff=
       F       F       T
#Block Obstruct= 4 ,-1
 -189.87  1215.7    30.6 1603.05 2175.57   27.09 9007.63 9503.82   25.63
17831.5419056.15   30.86
Bank Sta=15816.33,15871.09
XS Rating Curve= 0
Vertical n Elevations= 2
      26      31
Vertical n for Station=0
     .07      .1
Vertical n for Station=12652.23
     .12     .24
Vertical n for Station=14943.37
    .042    .042
Vertical n for Station=15070.05
     .12     .24
Vertical n for Station=15831.29
    .041    .041
Vertical n for Station=15871.09
     .12     .24
Vertical n for Station=15901.9
     .07      .1
Vertical n for Station=18702.92
     .15     .15
Vertical n Flow= 0
Exp/Cntr=.5,.3

Type RM Length L Ch R = 1 ,139436.9,84.43,1057.48,412.33
XS GIS Cut Line= 6
      3181481.81    13780898.352     3171866.722    13770169.529
      3171858.84     13769447.24     3172186.091    13769341.043
     3172377.602    13769069.632     3169469.299    13765188.124
#Sta/Elev= 30
       0   29.99 1150.99    28.4 1165.59   42.33 1202.71   30.56 1278.31   27.27
 1755.59   29.33 1820.97   13.76 1901.07   15.12 1942.64   28.12 2924.53    21.3
 3315.54   27.23 8768.81   30.43  8914.9   23.39 9165.21   25.73 9229.45    8.87
 9275.72   23.93 9337.21   26.58 12488.2   26.0914867.57   27.5914912.28   31.15
14988.17   14.5615040.97   31.6315583.99   22.2815621.93   11.34 15633.4      18
15647.87   20.9115800.03   31.5816065.76   29.69 18723.2   33.1620655.59   32.98
#Mann= 8 ,-1 , 0
       0     .07       0 12488.2     .12       014867.57    .042       0
14988.17     .12       015621.93    .081       0 15633.4     .12       0
16065.76     .07       0 18723.2     .15       0
#XS Ineff= 1 ,-1
       0    9000      40
Permanent Ineff=
       T
#Block Obstruct= 4 ,-1
 -169.45 1183.38    30.5 1488.55 2175.57   26.68 8969.47 9503.82      25
 15870.7 20481.7   30.46
Bank Sta=15583.99,15647.87
XS Rating Curve= 0
Vertical n Elevations= 2
      26      31
Vertical n for Station=0
     .07      .1
Vertical n for Station=12488.2
     .12     .24
Vertical n for Station=14867.57
    .042    .042
Vertical n for Station=14988.17
     .12     .24
Vertical n for Station=15621.93
    .041    .041
Vertical n for Station=15633.4
     .12     .24
Vertical n for Station=16065.76
     .07      .1
Vertical n for Station=18723.2
     .15     .15
Vertical n Flow= 0
Exp/Cntr=.3,.1

Type RM Length L Ch R = 1 ,138379.4,822.97,986.18,369.51
XS GIS Cut Line= 6
     3181531.725    13780888.369     3171900.897    13770146.746
     3172022.534    13769751.872     3172349.402    13769683.584
      3172528.86    13769259.198     3170400.764    13765156.151
#Sta/Elev= 30
       0   33.54 1155.27    28.4 1166.64   42.33 1206.26   30.56 1265.32   27.27
 1775.49   29.33 1837.96   13.76 1913.65   13.97  1962.2   28.12 2887.05   26.33
 2921.22    21.3 3254.01   27.24 7381.29   24.98 8807.09   30.92 8886.45   21.09
 9180.77   25.73 9227.92   18.05 9244.27    7.98 9288.34   23.92 9374.16   26.77
 12532.4   25.7514837.56   27.6814892.01   22.4314927.05    9.1414946.12   15.46
14958.77   21.8115627.39   32.0416101.14   29.62 18915.6   32.1320263.53   30.37
#Mann= 6 ,-1 , 0
       0     .07       0 12532.4     .12       014927.05    .081       0
14946.12     .12       016101.14     .07       0 18915.6     .15       0
#XS Ineff= 1 ,-1
       0    9000      40
Permanent Ineff=
       T
#Block Obstruct= 4 ,-1
 -195.85 1184.64   30.45 1603.05 2099.24   26.47 8664.12 9503.82   25.73
15699.5621030.43   30.57
Bank Sta=14892.01,14958.77
XS Rating Curve= 0
Vertical n Elevations= 2
      25      30
Vertical n for Station=0
     .07      .1
Vertical n for Station=12532.4
     .12     .24
Vertical n for Station=14927.05
    .041    .041
Vertical n for Station=14946.12
     .12     .24
Vertical n for Station=16101.14
     .07      .1
Vertical n for Station=18915.6
     .15     .15
Vertical n Flow= 0
Exp/Cntr=.3,.1

Type RM Length L Ch R = 1 ,137393.2,223.31,305.94,304.65
XS GIS Cut Line= 6
      3181551.69    13780848.438     3173495.524    13771803.969
     3172215.786    13770313.184     3172295.857    13770059.626
     3172662.694    13769452.515     3170780.166    13765251.001
#Sta/Elev= 30
       0   32.01 1101.13    28.4 1115.55   42.33 1154.35   30.56 1213.69   27.27
 1753.42   29.33 1811.01   13.76 1890.85   13.97 1937.47   28.12 2884.33    21.3
 3281.59   27.21 8776.34    31.4 8869.56      21 9163.56   25.73 9211.19   18.05
 9227.65    7.98  9291.8   26.13 9800.18   25.0310057.98   26.5712612.88   25.71
 14158.6   22.3514192.75    9.3914216.49   13.0314271.86   22.1314972.46   32.13
15861.58   32.2316069.54   31.9516239.71   31.6318620.04   31.9819656.09   31.81
#Mann= 10 ,-1 , 0
       0     .07       0 9800.18     .12       010057.98     .07       0
12612.88     .12       014192.75    .081       014216.49     .12       0
15861.58     .07       016069.54     .12       016239.71     .07       0
18620.04     .15       0
#XS Ineff= 1 ,-1
       0    9000      40
Permanent Ineff=
       T
#Block Obstruct= 4 ,-1
  -75.02 1141.07   30.43 1648.85 2015.27   26.36 8732.82 9435.11   25.63
15252.8319876.19   30.42
Bank Sta=14158.6,14271.86
XS Rating Curve= 0
Vertical n Elevations= 2
      25      30
Vertical n for Station=0
     .07      .1
Vertical n for Station=9800.18
     .12     .24
Vertical n for Station=10057.98
     .07      .1
Vertical n for Station=12612.88
     .12     .24
Vertical n for Station=14192.75
    .041    .041
Vertical n for Station=14216.49
     .12     .24
Vertical n for Station=15861.58
     .07      .1
Vertical n for Station=16069.54
     .12     .24
Vertical n for Station=16239.71
     .07      .1
Vertical n for Station=18620.04
     .15     .15
Vertical n Flow= 0
Exp/Cntr=.3,.1

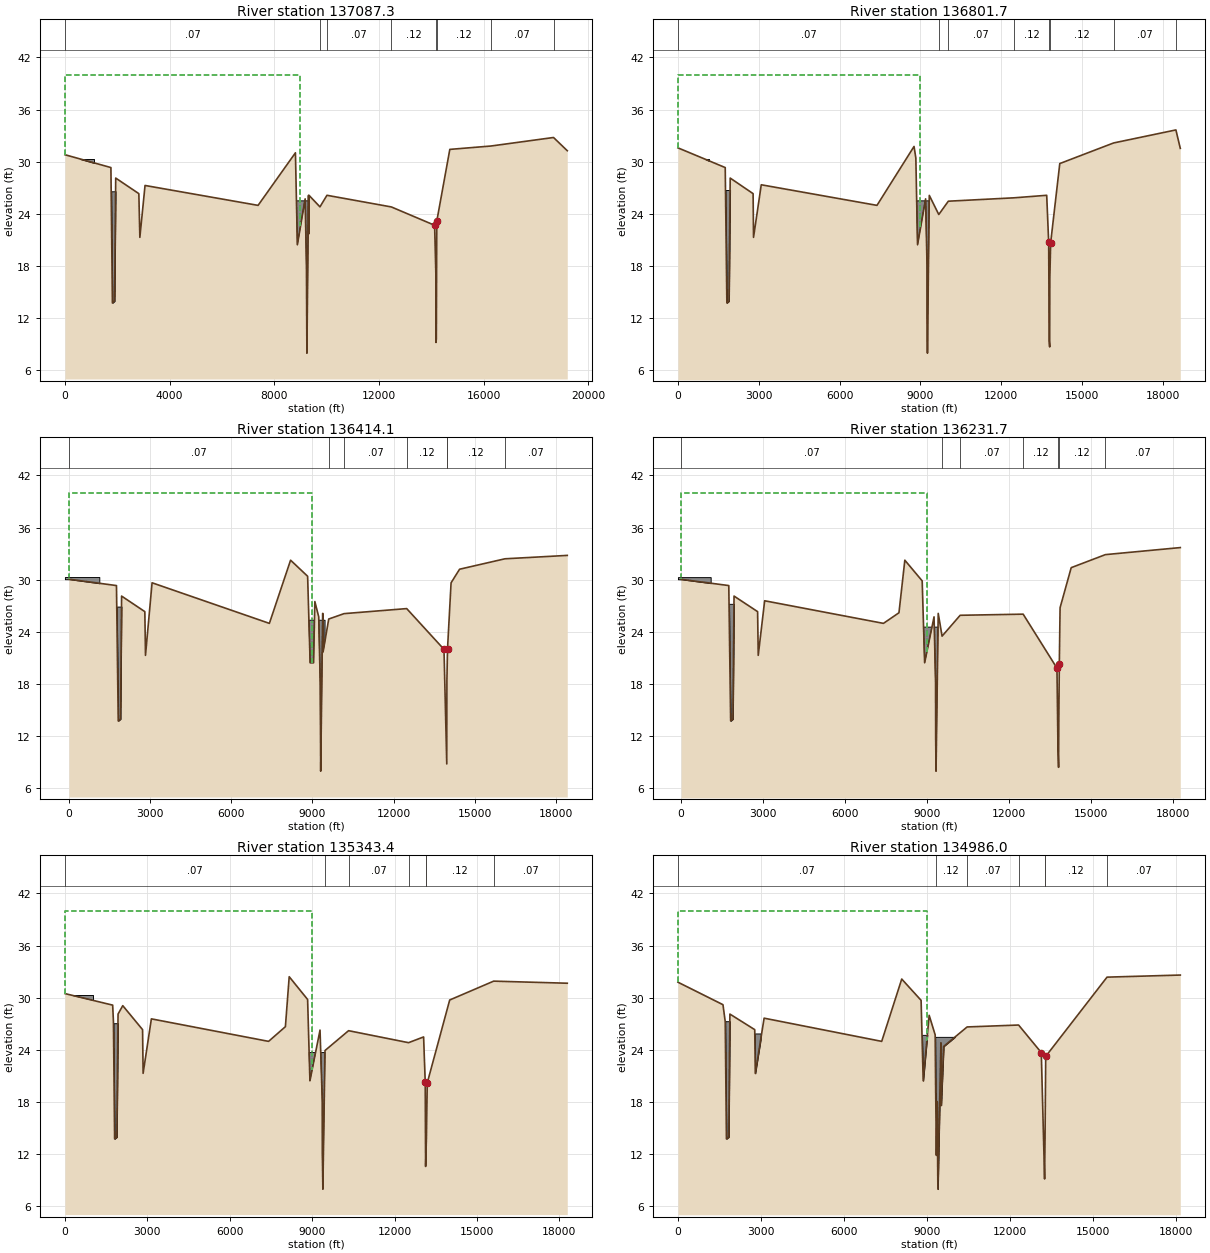
Type RM Length L Ch R = 1 ,137087.3,242.76,285.58,166.28
XS GIS Cut Line= 6
     3181591.622    13780828.472     3173545.438     13771774.02
     3172369.255    13770299.839     3172566.036    13770173.735
     3172753.844    13769569.355     3171191.185    13765535.553
#Sta/Elev= 30
       0   30.81 1757.73   29.33 1815.17   13.76 1897.42   13.97 1941.37   28.12
 2824.77   26.33 2863.74    21.3 3061.48   27.27 7380.08   24.98 8807.52   31.03
 8881.52   20.45 9179.05   25.73 9228.13   18.05 9245.44    7.98 9307.08   26.13
 9316.94    21.7  9328.1   26.13 9744.38   24.8110011.51   26.1412472.05    24.8
14125.25   22.6914172.24   17.1714177.17    9.2114190.58    9.58 14204.6   20.06
14208.64   23.1714706.13   31.4216280.44   31.8118668.17   32.7919193.62   31.27
#Mann= 8 ,-1 , 0
       0     .07       0 9744.38     .12       010011.51     .07       0
12472.05     .12       014177.17    .081       0 14204.6     .12       0
16280.44     .07       018668.17     .15       0
#XS Ineff= 1 ,-1
       0    9000      40
Permanent Ineff=
       T
#Block Obstruct= 4 ,-1
 -131.01 1115.08   30.32 1679.39  1954.2    26.6 8610.69 9465.65    25.5
15369.1815772.21   30.29
Bank Sta=14125.25,14208.64
XS Rating Curve= 0
Vertical n Elevations= 2
      25      30
Vertical n for Station=0
     .07      .1
Vertical n for Station=9744.38
     .12     .24
Vertical n for Station=10011.51
     .07      .1
Vertical n for Station=12472.05
     .12     .24
Vertical n for Station=14177.17
    .041    .041
Vertical n for Station=14204.6
     .12     .24
Vertical n for Station=16280.44
     .07      .1
Vertical n for Station=18668.17
     .15     .15
Vertical n Flow= 0
Exp/Cntr=.3,.1

Type RM Length L Ch R = 1 ,136801.7,108.08,387.65,105.58
XS GIS Cut Line= 6
     3181651.519    13780788.541     3173595.353    13771754.054
     3173108.429    13770898.605     3172702.884    13770473.325
     3172818.835    13769623.526     3171507.354    13765725.254
#Sta/Elev= 30
       0    31.6    1756   29.33 1817.18   13.76 1896.26   13.97 1941.15   28.12
 2791.25   26.33 2806.98    21.3 3094.25   27.35 7390.82   24.98 8767.38   31.76
 8834.33   30.43 8897.17   20.45 9197.14   25.73 9249.75   18.05 9252.13      12
 9265.65    7.98 9333.33   26.13 9685.91   23.9310040.98   25.46 12484.9   25.85
13693.34   26.14 13766.8   20.7513786.24    9.3713803.84    8.6913810.48   16.61
13838.97   20.64 14179.2   29.7916176.01   32.1618491.18   33.6618654.13   31.54
#Mann= 8 ,-1 , 0
       0     .07       0 9685.91     .12       010040.98     .07       0
 12484.9     .12       013786.24    .081       013810.48     .12       0
16176.01     .07       018491.18     .15       0
#XS Ineff= 1 ,-1
       0    9000      40
Permanent Ineff=
       T
#Block Obstruct= 4 ,-1
  -47.45 1169.11   30.31 1618.32 2015.27   26.75 8763.36 9374.05    25.5
 14979.516232.66   30.33
Bank Sta=13766.8,13838.97
XS Rating Curve= 0
Vertical n Elevations= 2
      25      30
Vertical n for Station=0
     .07      .1
Vertical n for Station=9685.91
     .12     .24
Vertical n for Station=10040.98
     .07      .1
Vertical n for Station=12484.9
     .12     .24
Vertical n for Station=13786.24
    .041    .041
Vertical n for Station=13810.48
     .12     .24
Vertical n for Station=16176.01
     .07      .1
Vertical n for Station=18491.18
     .15     .15
Vertical n Flow= 0
Exp/Cntr=.3,.1

Type RM Length L Ch R = 1 ,136414.1,111.57,182.32,152.74
XS GIS Cut Line= 5
     3181721.399    13780748.609     3173625.301     13771704.14
     3172874.699     13770200.78      3172981.22    13769985.203
     3171697.055    13765820.105
#Sta/Elev= 30
       0   30.06 1755.77   29.33 1821.09   13.76  1904.8   13.97  1945.2   28.12
  2804.3   26.33 2828.28    21.3 3071.81   29.65 7407.48   24.98 8190.97   32.25
 8821.38    30.4 8914.08   20.45 9040.28   20.45 9088.29   27.49 9231.68   25.73
  9287.6   18.05 9304.02    7.98 9379.25   26.13 9393.09    21.7 9601.16   25.48
10167.04    26.112483.07   26.6813861.45   21.9913963.96    8.8113969.06   18.38
13991.77   22.0514123.54   29.6514437.48   31.2116115.08   32.41 18418.1    32.8
#Mann= 7 ,-1 , 0
       0     .07       0 9601.16     .12       010167.04     .07       0
12483.07     .12       013963.96    .081       013969.06     .12       0
16115.08     .07       0
#XS Ineff= 1 ,-1
       0    9000      40
Permanent Ineff=
       T
#Block Obstruct= 4 ,-1
 -150.06 1121.63   30.31 1465.65 1984.73   26.91 8732.82 9465.65   25.34
14804.9115558.64   30.68
Bank Sta=13861.45,13991.77
XS Rating Curve= 0
Vertical n Elevations= 2
      25      30
Vertical n for Station=0
     .07      .1
Vertical n for Station=9601.16
     .12     .24
Vertical n for Station=10167.04
     .07      .1
Vertical n for Station=12483.07
     .12     .24
Vertical n for Station=13963.96
    .041    .041
Vertical n for Station=13969.06
     .12     .24
Vertical n for Station=16115.08
     .07      .1
Vertical n Flow= 0
Exp/Cntr=.3,.1

Type RM Length L Ch R = 1 ,136231.7,153.34,888.31,440.64
XS GIS Cut Line= 5
      3181761.33    13780718.661     3173665.233    13771674.191
     3173114.381    13770301.904     3173105.494    13770008.029
     3171776.243    13765850.043
#Sta/Elev= 30
       0   30.05 1749.25   29.33  1817.5   13.76  1900.5   13.97 1941.88   28.12
 2804.21   26.33  2827.2    21.3 3062.14   27.58 7411.17   24.98 7978.66    26.2
  8193.4   32.25  8828.5   29.87  8918.1   20.45 9262.73   25.73 9319.01   18.05
    9322      12 9335.46    7.98 9415.58   26.13 9556.81   23.5110218.73   25.91
12524.61   26.0413762.11   19.8313799.66   10.5113821.37    8.4213830.69   13.75
 13848.4    20.313876.26   26.7814283.78   31.3915535.44   32.8918276.77    33.7
#Mann= 7 ,-1 , 0
       0     .07       0 9556.81     .12       010218.73     .07       0
12524.61     .12       013799.66    .081       013830.69     .12       0
15535.44     .07       0
#XS Ineff= 1 ,-1
       0    9000      40
Permanent Ineff=
       T
#Block Obstruct= 4 ,-1
 -112.29 1085.78    30.3 1557.25 1984.73   27.23 8824.43 9465.65   24.55
14610.8515300.43   30.35
Bank Sta=13762.11,13848.4
XS Rating Curve= 0
Vertical n Elevations= 2
      25      30
Vertical n for Station=0
     .07      .1
Vertical n for Station=9556.81
     .12     .24
Vertical n for Station=10218.73
     .07      .1
Vertical n for Station=12524.61
     .12     .24
Vertical n for Station=13799.66
    .041    .041
Vertical n for Station=13830.69
     .12     .24
Vertical n for Station=15535.44
     .07      .1
Vertical n Flow= 0
Exp/Cntr=.3,.1

Type RM Length L Ch R = 1 ,135343.4,137.35,357.48,213.43
XS GIS Cut Line= 6
     3181821.228    13780668.746     3173705.164    13771624.277
     3173530.282    13770733.555     3173630.097    13770502.762
      3173576.99    13769952.865     3171859.428    13765877.771
#Sta/Elev= 30
       0   30.48 1738.47   29.15 1766.67   27.25 1809.67   13.76 1889.98   13.97
 1934.67   28.12 2106.22   29.09 2826.94   26.33 2846.87    21.3 3147.64   27.57
 7414.28   24.98 8026.41   26.67 8164.67   32.42    8835    29.8  8919.1   20.45
  9286.8   26.28 9369.74   18.05 9372.45      12 9389.99    7.98 9468.83   23.93
10326.17   26.2112509.08   24.8313057.27   25.4913115.77   20.3413130.21   10.59
   13160   13.9513190.88   20.2114007.23   29.7415608.54   31.9118286.93   31.67
#Mann= 7 ,-1 , 0
       0     .07       0 9468.83     .12       010326.17     .07       0
12509.08     .12       013130.21    .081       0   13160     .12       0
15608.54     .07       0
#XS Ineff= 1 ,-1
       0    9000      40
Permanent Ineff=
       T
#Block Obstruct= 3 ,-1
  -67.66 1020.24   30.28 1496.18  1954.2   27.07 8824.43 9679.39   23.69
Bank Sta=13115.77,13190.88
XS Rating Curve= 0
Vertical n Elevations= 2
      25      30
Vertical n for Station=0
     .07      .1
Vertical n for Station=9468.83
     .12     .24
Vertical n for Station=10326.17
     .07      .1
Vertical n for Station=12509.08
     .12     .24
Vertical n for Station=13130.21
    .041    .041
Vertical n for Station=13160
     .12     .24
Vertical n for Station=15608.54
     .07      .1
Vertical n Flow= 0
Exp/Cntr=.3,.1

Type RM Length L Ch R = 1 ,134986.0,267.17,1095.9,253.68
XS GIS Cut Line= 5
      3181831.21    13780598.866     3173745.095    13771574.363
     3173870.583    13770326.529     3173773.765    13769839.574
     3171942.613    13765951.714
#Sta/Elev= 30
       0   31.79 1628.93    29.2 1710.14   27.25 1753.93   13.76 1837.98   13.97
 1879.46   28.12  2777.2   26.33 2797.23    21.3  3116.6   27.65 7368.34   24.98
  8092.9   32.15 8792.87    29.7 8868.54   20.45  9084.6   27.98  9301.7   25.73
 9315.92   20.52 9345.17   11.87 9372.76   18.05 9399.81    7.98 9509.57   24.81
 9520.13   17.62 9609.16    24.410457.19   26.6412318.57   26.8613139.11   23.69
13258.25    9.1513274.23   13.6813298.81   23.2515515.98   32.3718165.32   32.61
#Mann= 7 ,-1 , 0
       0     .07       0 9315.92     .12       010457.19     .07       0
12318.57     .12       013258.25    .081       013274.23     .12       0
15515.98     .07       0
#XS Ineff= 1 ,-1
       0    9000      40
Permanent Ineff=
       T
#Block Obstruct= 5 ,-1
   22.44   921.7   30.24 1526.72 2015.27    27.3 2473.28 2992.37   25.89
 8549.62 9129.77   25.73 9160.3110412.21    25.5
Bank Sta=13139.11,13298.81
XS Rating Curve= 0
Vertical n Elevations= 2
      25      30
Vertical n for Station=0
     .07      .1
Vertical n for Station=9315.92
     .12     .24
Vertical n for Station=10457.19
     .07      .1
Vertical n for Station=12318.57
     .12     .24
Vertical n for Station=13258.25
    .041    .041
Vertical n for Station=13274.23
     .12     .24
Vertical n for Station=15515.98
     .07      .1
Vertical n Flow= 0
Exp/Cntr=.3,.1

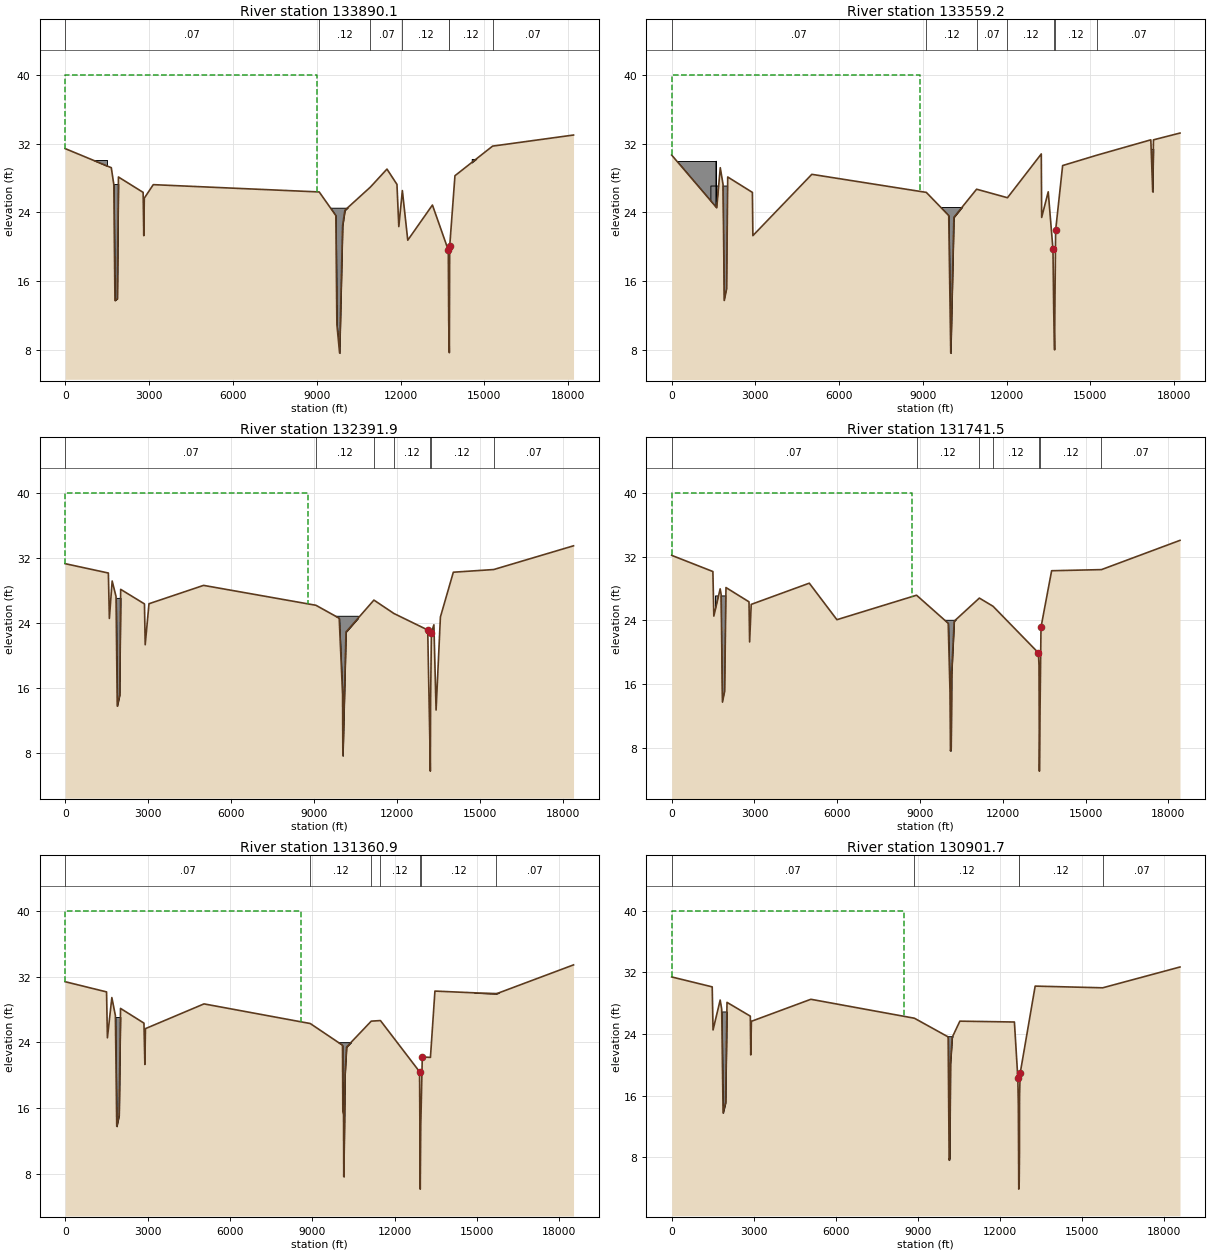
Type RM Length L Ch R = 1 ,133890.1,141.23,330.84,363.75
XS GIS Cut Line= 6
     3181881.125    13780588.884      3174004.65    13771524.449
      3174206.37    13770213.932     3174001.153    13769955.185
     3174085.803     13769881.93     3172007.313    13765988.685
#Sta/Elev= 30
       0   31.42 1649.44    29.2 1739.29   27.25  1779.9   13.76 1862.99   13.97
 1904.64   28.12 2788.64   26.33 2811.69    21.3 2830.35   25.66 3151.29   27.23
 9090.11   26.38 9683.64   23.64 9721.87   10.96 9819.46    7.64 9926.06   22.45
10008.17   24.2510921.61   26.9511514.08   29.0411871.34   27.2611937.66   22.35
12064.95   26.5412257.92   20.7713140.69   24.8613708.71   19.6213723.89   11.29
13746.31    7.6913758.67   20.0513946.87   28.2715293.31   31.7118189.91      33
#Mann= 7 ,-1 , 0
       0     .07       0 9090.11     .12       010921.61     .07       0
12064.95     .12       013723.89    .081       013746.31     .12       0
15293.31     .07       0
#XS Ineff= 1 ,-1
       0    9000      40
Permanent Ineff=
       T
#Block Obstruct= 4 ,-1
   40.59 1493.06   30.09 1496.18  2137.4    27.3 9038.1710473.28   24.55
14546.9214841.54   30.22
Bank Sta=13708.71,13758.67
XS Rating Curve= 0
Vertical n Elevations= 2
      24      30
Vertical n for Station=0
     .07      .1
Vertical n for Station=9090.11
     .12     .24
Vertical n for Station=10921.61
     .07      .1
Vertical n for Station=12064.95
     .12     .24
Vertical n for Station=13723.89
    .041    .041
Vertical n for Station=13746.31
     .12     .24
Vertical n for Station=15293.31
     .07      .1
Vertical n Flow= 0
Exp/Cntr=.3,.1

Type RM Length L Ch R = 1 ,133559.2,184.91,1167.28,425.08
XS GIS Cut Line= 6
     3181980.953    13780628.815     3174134.427    13771584.346
     3174344.336    13770153.042     3174324.318    13769806.068
     3174246.499    13769422.044     3172081.255    13765997.928
#Sta/Elev= 30
       0   30.67 1614.23   24.54 1740.97    29.2 1840.92   27.25 1884.78   13.76
 1969.75   15.12 2008.09   28.12 2891.96   26.33 2909.41    21.3 5020.74   28.43
 9122.71   26.33 9925.34   23.64 9997.83    7.6410110.09   23.4310924.36    26.7
12030.83   25.7113241.89    30.813255.39   23.4213490.47    26.4 13660.7   19.69
13688.37    12.313718.62    8.02 13732.8   14.1113755.36   21.9114006.36   29.45
 15237.9   30.6617165.94   32.4417233.88    26.417260.02   32.4418211.03   33.23
#Mann= 7 ,-1 , 0
       0     .07       0 9122.71     .12       010924.36     .07       0
12030.83     .12       013688.37    .081       0 13732.8     .12       0
 15237.9     .07       0
#XS Ineff= 1 ,-1
       0    8900      40
Permanent Ineff=
       T
#Block Obstruct= 5 ,-1
   -2.67  1576.7   30.01 1404.58 2167.94   27.07 1574.95 1578.59   30.01
 9038.1710595.42   24.6316946.5617312.98   31.39
Bank Sta=13660.7,13755.36
XS Rating Curve= 0
Vertical n Elevations= 2
      24      30
Vertical n for Station=0
     .07      .1
Vertical n for Station=9122.71
     .12     .24
Vertical n for Station=10924.36
     .07      .1
Vertical n for Station=12030.83
     .12     .24
Vertical n for Station=13688.37
    .041    .041
Vertical n for Station=13732.8
     .12     .24
Vertical n for Station=15237.9
     .07      .1
Vertical n Flow= 0
Exp/Cntr=.3,.1

Type RM Length L Ch R = 1 ,132391.9,222.9,650.46,341.65
XS GIS Cut Line= 6
     3182000.919    13780598.866      3174284.17    13771664.209
     3174697.982     13770433.29     3174778.053    13770306.511
     3174666.706     13769422.21     3172145.955    13765997.928
#Sta/Elev= 30
       0   31.28 1562.17   30.13  1598.5   24.54  1699.5   29.15 1839.47   27.25
 1883.57   13.76 1969.84   15.12 2007.62   28.12 2868.64   26.33 2895.33    21.3
 3031.97   26.35 5008.34   28.61 9075.45   26.16 9916.96   24.5710038.98   15.18
10049.26    7.6410162.63   22.8711172.82    26.811897.02   25.1513120.12   23.12
13205.53    8.0413215.08    5.7513224.43   14.39 13254.1   22.8113343.72   23.76
13423.05   13.2713579.65   24.7214047.48   30.2315509.26   30.5618397.67   33.48
#Mann= 7 ,-1 , 0
       0     .07       0 9075.45     .12       011172.82     .07       0
11897.02     .12       013205.53    .081       013224.43     .12       0
15509.26     .07       0
#XS Ineff= 1 ,-1
       0    8800      40
Permanent Ineff=
       T
#Block Obstruct= 5 ,-1
  -45.66 1560.88   30.07 1559.62 1562.05   30.07 1709.92 2106.87   27.07
 9496.1810595.42   24.8714048.2317257.59   29.99
Bank Sta=13120.12,13254.1
XS Rating Curve= 0
Vertical n Elevations= 2
      24      30
Vertical n for Station=0
     .07      .1
Vertical n for Station=9075.45
     .12     .24
Vertical n for Station=11172.82
     .07      .1
Vertical n for Station=11897.02
     .12     .24
Vertical n for Station=13205.53
    .041    .041
Vertical n for Station=13224.43
     .12     .24
Vertical n for Station=15509.26
     .07      .1
Vertical n Flow= 0
Exp/Cntr=.3,.1

Type RM Length L Ch R = 1 ,131741.5,185.73,380.58,402.08
XS GIS Cut Line= 6
     3182000.919    13780519.004     3174473.844    13771784.003
     3174998.247    13770159.715     3175118.354    13769972.883
     3174984.979    13769549.519     3172201.411    13765997.928
#Sta/Elev= 30
       0   32.16 1493.96   30.13 1528.36   24.54  1757.8   27.96 1792.96   27.25
 1841.17   13.76 1920.98   15.12 1968.62   28.12 2803.01   26.33 2825.44    21.3
 2882.88   26.01 4988.24   28.67  5988.9   24.09 8876.28   27.16 10023.6   23.64
10087.54   15.1810105.41    7.6410127.69    7.9810146.89    17.310239.53    23.9
11152.59    26.811646.47   25.7813293.74   19.9313314.55   18.3413328.23     5.1
13359.01   14.8313386.88   23.1513772.02   30.2315578.36   30.3718424.78   34.04
#Mann= 7 ,-1 , 0
       0     .07       0 8876.28     .12       011152.59     .07       0
11646.47     .12       013328.23    .081       013359.01     .12       0
15578.36     .07       0
#XS Ineff= 1 ,-1
       0    8700      40
Permanent Ineff=
       T
#Block Obstruct= 4 ,-1
    29.9 1495.26   29.97 1587.79 1984.73   27.07 9709.9210412.21   24.08
14396.6717003.34   29.91
Bank Sta=13293.74,13386.88
XS Rating Curve= 0
Vertical n Elevations= 2
      24      30
Vertical n for Station=0
     .07      .1
Vertical n for Station=8876.28
     .12     .24
Vertical n for Station=11152.59
     .07      .1
Vertical n for Station=11646.47
     .12     .24
Vertical n for Station=13328.23
    .041    .041
Vertical n for Station=13359.01
     .12     .24
Vertical n for Station=15578.36
     .07      .1
Vertical n Flow= 0
Exp/Cntr=.3,.1

Type RM Length L Ch R = 1 ,131360.9,144.81,459.22,162.51
XS GIS Cut Line= 6
     3182050.833    13780499.038      3174633.57     13771913.78
     3175038.083    13770533.023     3175218.154    13770380.851
     3175332.994     13769803.83     3172247.625    13765988.685
#Sta/Elev= 30
       0   31.37 1506.14   30.13 1537.35   24.54 1698.91   29.44 1827.91   27.25
 1877.51   13.76  1963.4   15.12 2015.22   28.12  2868.2   26.33 2901.61    21.3
 2922.67   25.66 5055.78   28.67 8925.72   26.2810100.36   23.6410112.36   15.58
10138.27   15.1810146.29    7.6410191.66   20.08 10247.3   23.4111147.23   26.57
11482.58   26.6412907.74   20.4112924.76   10.0212931.17    6.1212951.01   13.81
13006.34    22.2 13303.4   22.1613466.73   30.2315704.54    29.918515.08   33.42
#Mann= 7 ,-1 , 0
       0     .07       0 8925.72     .12       011147.23     .07       0
11482.58     .12       012924.76    .081       012951.01     .12       0
15704.54     .07       0
#XS Ineff= 1 ,-1
       0    8600      40
Permanent Ineff=
       T
#Block Obstruct= 5 ,-1
  128.47 1502.09      30 1501.23  1505.9      30 1648.85  2045.8   27.07
 9923.6610412.21   24.0114833.5917076.08   30.02
Bank Sta=12907.74,13006.34
XS Rating Curve= 0
Vertical n Elevations= 2
      24      30
Vertical n for Station=0
     .07      .1
Vertical n for Station=8925.72
     .12     .24
Vertical n for Station=11147.23
     .07      .1
Vertical n for Station=11482.58
     .12     .24
Vertical n for Station=12924.76
    .041    .041
Vertical n for Station=12951.01
     .12     .24
Vertical n for Station=15704.54
     .07      .1
Vertical n Flow= 0
Exp/Cntr=.3,.1

Type RM Length L Ch R = 1 ,130901.7,392.17,207.26,141.06
XS GIS Cut Line= 6
     3182070.799    13780459.106     3174753.364     13771983.66
     3175136.995    13770837.368     3175458.655    13770626.794
     3175480.684    13769866.762     3172284.597    13765970.199
#Sta/Elev= 30
       0   31.42 1482.45   30.13 1513.13   24.54 1774.01   28.42 1829.52   27.25
 1880.53   13.76 1971.63   15.12 2023.82   28.12 2876.54   26.33  2891.8    21.3
 2915.74   25.66 5090.34   28.52 8878.29   26.0610110.88   23.6410147.96    7.64
 10171.9    7.9810193.65   20.0710257.63   23.5610540.24   25.6812534.89   25.57
12659.81   18.2912678.52   14.73 12694.3    3.8812710.27    4.8212719.77    8.54
12722.44   15.7812744.48   18.8913293.93   30.2315763.92   30.0118590.76   32.71
#Mann= 5 ,-1 , 0
       0     .07       0 8878.29     .12       012710.27    .081       0
12719.77     .12       015763.92     .07       0
#XS Ineff= 1 ,-1
       0    8500      40
Permanent Ineff=
       T
#Block Obstruct= 4 ,-1
  182.39 1483.65   29.87 1709.92 2076.34   26.94 9648.8510381.68   23.73
15505.4216670.25   29.96
Bank Sta=12659.81,12744.48
XS Rating Curve= 0
Vertical n Elevations= 2
      24      30
Vertical n for Station=0
     .07      .1
Vertical n for Station=8878.29
     .12     .24
Vertical n for Station=12710.27
    .041    .041
Vertical n for Station=12719.77
     .12     .24
Vertical n for Station=15763.92
     .07      .1
Vertical n Flow= 0
Exp/Cntr=.3,.1

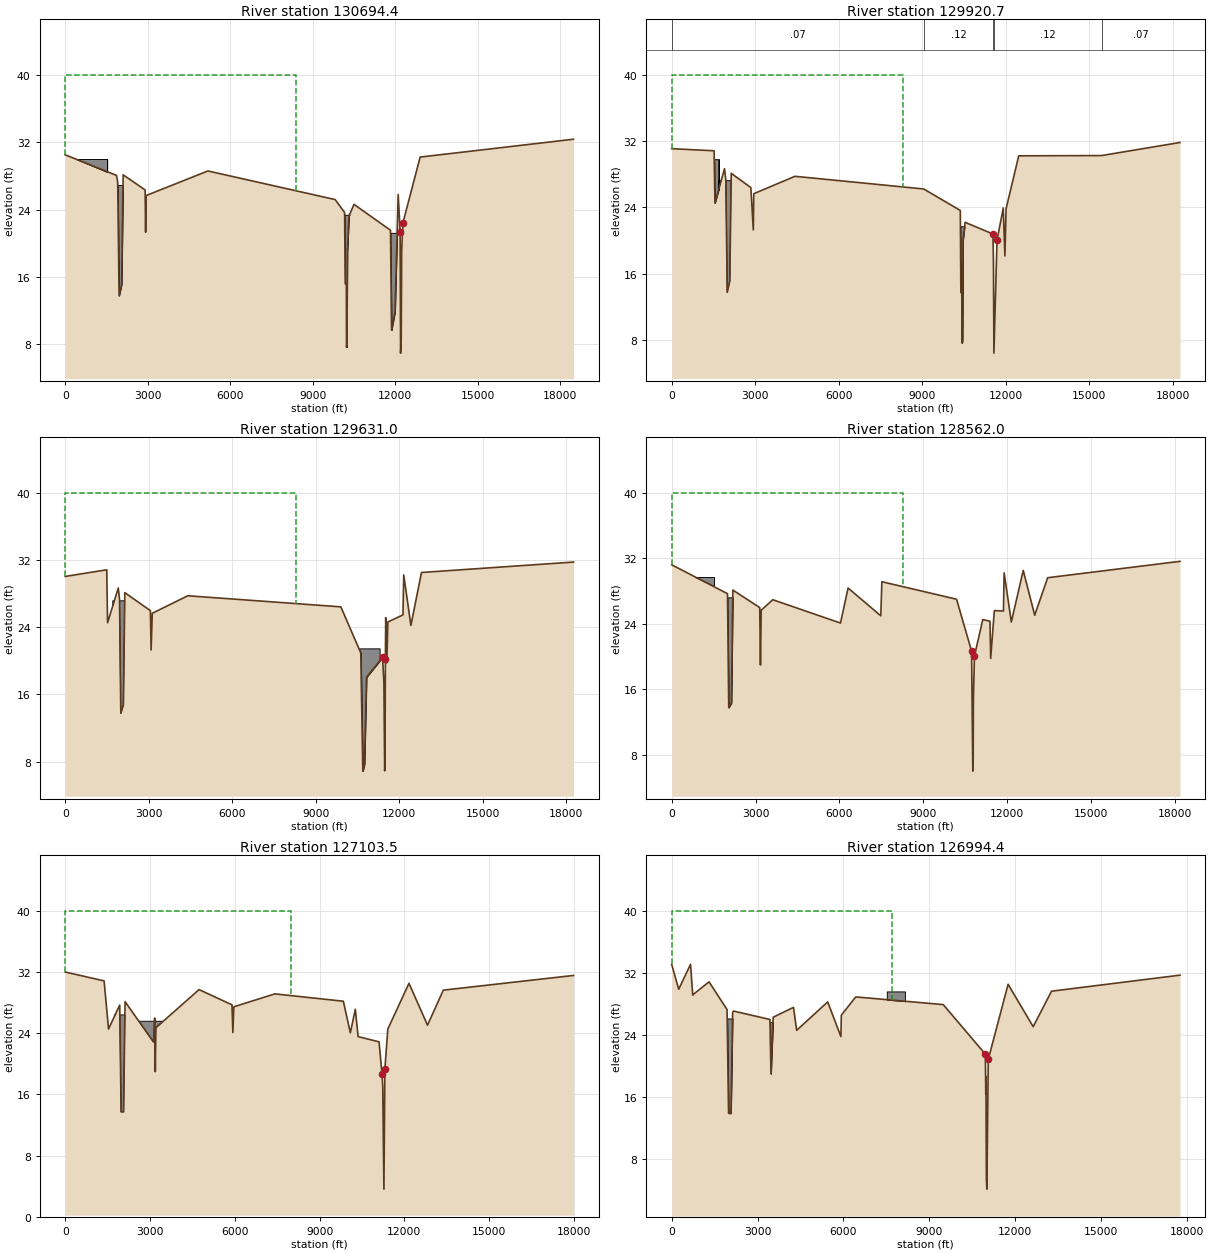
Type RM Length L Ch R = 1 ,130694.4,594.12,773.71,130.84
XS GIS Cut Line= 6
     3182140.679    13780469.089     3175581.941      13772892.1
     3175133.318    13772094.249     3175592.106    13770673.502
     3175620.073    13769834.477      3172293.84    13765914.742
#Sta/Elev= 30
       0    30.5 1867.05   28.05 1909.75   27.25 1960.36   13.76 2052.86   15.12
 2107.82   28.12 2906.82   26.33 2924.75    21.3 2944.73   25.66 5190.15   28.58
 9819.31   25.1810163.28   23.6410184.43   15.1810225.84   15.1810232.46    7.64
10244.96    7.9810262.94   18.96 10322.3   23.2310505.49   24.6111831.89   21.54
11870.64    9.6711996.59   11.8412111.21   25.7912182.68   21.37 12198.9    6.94
12222.33     8.812238.61   19.1112285.27   22.4312911.23   30.23 18489.9   32.35
#Mann= 0 ,-1 , 0
#XS Ineff= 1 ,-1
       0    8400      40
Permanent Ineff=
       T
#Block Obstruct= 6 ,-1
   247.1 1521.59      30 1520.46 1527.09      30 1679.39 2167.94   26.91
 9740.4610473.28   23.3811786.8212084.52   21.2315342.29   16000      30
Bank Sta=12182.68,12285.27
XS Rating Curve= 0
Vertical n Elevations= 2
      24      30
Vertical n for Station=0
     .07      .1
Vertical n for Station=8895.47
     .12     .24
Vertical n for Station=12198.9
    .041    .041
Vertical n for Station=12217.27
     .12     .24
Vertical n for Station=15600.65
     .07      .1
Vertical n Flow= 0
Exp/Cntr=.3,.1

Type RM Length L Ch R = 1 ,129920.7,230.2,289.73,110.85
XS GIS Cut Line= 6
      3182180.61    13780439.141     3175761.633     13773031.86
     3175578.761    13771053.839     3175678.849    13770793.609
     3175753.238    13769836.631     3172312.325    13765887.014
#Sta/Elev= 30
       0   31.09 1524.26   30.84 1554.65   24.54 1899.83   28.68 1947.67   27.25
 1996.02   13.76 2088.67   15.12 2139.53   28.12 2845.17    26.4 2933.38    21.3
 2950.44   25.66 4430.61   27.76 9056.55   26.23 10371.5   23.6410391.41   13.74
10424.51   13.8710435.18    7.6410450.19    7.9810469.87   20.0810543.39   22.21
11544.56    20.811562.27   17.3811578.62    6.4311690.36   20.0411914.88   23.94
11973.88   18.1512015.92   23.8412470.62   30.2315447.52   30.2618265.25   31.84
#Mann= 5 ,-1 , 0
       0     .07       0 9056.55     .12       011562.27    .081       0
11578.62     .12       015447.52     .07       0
#XS Ineff= 1 ,-1
       0    8300      40
Permanent Ineff=
       T
#Block Obstruct= 4 ,-1
   208.4 1690.07   29.82 1679.39  2137.4   27.23  1686.6 1690.87   29.82
10015.2710625.95   21.73
Bank Sta=11544.56,11690.36
XS Rating Curve= 0
Vertical n Elevations= 2
      24      30
Vertical n for Station=0
     .07      .1
Vertical n for Station=9056.55
     .12     .24
Vertical n for Station=11562.27
    .041    .041
Vertical n for Station=11578.62
     .12     .24
Vertical n for Station=15447.52
     .07      .1
Vertical n Flow= 0
Exp/Cntr=.3,.1

Type RM Length L Ch R = 1 ,129631.0,536.08,1068.98,73.64
XS GIS Cut Line= 6
     3182200.576    13780389.226      3176101.05     13773311.38
     3175805.197     13771991.01     3175930.828    13771217.799
     3175855.016    13769799.621     3172330.811      13765840.8
#Sta/Elev= 30
       0   30.05 1493.24   30.84 1522.17   24.54 1907.48   28.68 1951.52   27.33
 1997.93   13.76 2091.33   14.74 2142.12   28.12 3060.38   25.98 3086.85    21.3
 3128.93   25.66 4403.37   27.75 9904.83   26.4310620.79   20.95 10694.8    6.88
10755.05    7.7410827.98   18.0611403.16   20.4211451.83   17.41 11479.4    6.91
11490.05    7.6311505.39   20.2811516.61   25.1411555.57   19.7711593.97   24.63
12136.05   25.4712165.03   30.23   12422   24.22   12802   30.5218265.74   31.76
#Mann= 0 ,-1 , 0
#XS Ineff= 1 ,-1
       0    8290      40
Permanent Ineff=
       T
#Block Obstruct= 4 ,-1
   30.36 1491.53   29.76 1709.92 2229.01   27.1510290.0811297.71   21.49
   1512816533.45    29.8
Bank Sta=11403.16,11505.39
XS Rating Curve= 0
Vertical n Elevations= 2
      24      30
Vertical n for Station=0
     .07      .1
Vertical n for Station=8837.23
     .12     .24
Vertical n for Station=11464.67
    .041    .041
Vertical n for Station=11490.05
     .12     .24
Vertical n for Station=15507.48
     .07      .1
Vertical n Flow= 0
Exp/Cntr=.3,.1

Type RM Length L Ch R = 1 ,128562.0,660.21,1458.51,98.81
XS GIS Cut Line= 6
      3182250.49    13780379.244     3176570.244    13773740.643
      3176351.53    13771850.497     3176032.495    13771400.812
     3175919.783    13769771.863     3172340.054    13765785.343
#Sta/Elev= 30
       0   31.21 1996.91   27.68 2041.94   13.76 2137.35   14.35 2189.09   28.12
 3151.06   25.98 3176.83   18.97 3203.69   25.66 3617.55   26.94 6040.44   24.09
 6311.54   28.37 7481.76   24.98 7520.21   29.14 10192.6      2710730.04   20.67
10774.43       610787.03    6.7710794.69   14.7910833.45   20.0811131.09   24.52
11388.55   24.3111413.28   19.77 11544.8   25.6111869.67   25.5611895.06   30.23
12152.53   24.22 12578.7   30.5212988.69   25.0513453.29   29.6318187.12   31.63
#Mann= 0 ,-1 , 0
#XS Ineff= 1 ,-1
       0    8290      40
Permanent Ineff=
       T
#Block Obstruct= 2 ,-1
  -65.77 1498.21   29.73 1709.92 2290.08   27.23
Bank Sta=10730.04,10833.45
XS Rating Curve= 0
Vertical n Elevations= 2
      24      30
Vertical n for Station=0
     .07      .1
Vertical n for Station=8866.92
     .12     .24
Vertical n for Station=10774.43
    .041    .041
Vertical n for Station=10797.83
     .12     .24
Vertical n for Station=15380.43
     .07      .1
Vertical n Flow= 0
Exp/Cntr=.3,.1

Type RM Length L Ch R = 1 ,127103.5,105.68,109.08,82.04
XS GIS Cut Line= 6
     3182341.868    13780161.587     3177502.731    13774454.562
     3176872.794    13771650.127     3176188.107    13770743.379
     3176003.056    13769744.105     3172330.811    13765720.644
#Sta/Elev= 30
       0      32 1375.83   30.84 1532.63   24.54 1928.68   27.68 1977.55   13.72
 2065.96   13.72 2117.83   28.12 3127.84   22.83 3165.34   25.98 3187.34   18.97
 3205.71    24.7  4735.8    29.7 5900.24   27.71  5932.3   24.09 5965.79   27.45
 7419.02   29.14 9840.39   28.1810087.99   24.0510263.21   27.1310363.22   23.55
11103.66   22.8711207.18   18.68 11234.8   17.03 11275.9    3.6111310.12   19.34
11413.78   24.5412162.42   30.5212818.37   25.05 13378.1   29.6317984.16   31.55
#Mann= 0 ,-1 , 0
#XS Ineff= 1 ,-1
       0    8000      40
Permanent Ineff=
       T
#Block Obstruct= 3 ,-1
 1740.46  2137.4   26.39 2442.75 3541.98   25.5613380.96   15000   29.24
Bank Sta=11207.18,11310.12
XS Rating Curve= 0
Vertical n Elevations= 2
      24      30
Vertical n for Station=0
     .07      .1
Vertical n for Station=8876.78
     .12     .24
Vertical n for Station=11264.37
    .041    .041
Vertical n for Station=11285.96
     .12     .24
Vertical n for Station=14995.79
     .07      .1
Vertical n Flow= 0
Exp/Cntr=.3,.1

Type RM Length L Ch R = 1 ,126994.4,184.45,550.39,117.12
XS GIS Cut Line= 6
     3182657.464    13779872.291     3178791.414    13775296.151
     3176956.067    13771576.107     3176326.088    13770760.246
     3176077.076      13769725.6     3172349.296    13765655.944
#Sta/Elev= 30
       0    33.1  246.22   29.88  658.91    33.1  735.39   29.16 1305.93   30.84
 1934.44   27.26 1987.51   13.88 2071.07   13.88 2129.85   26.89 2158.41   27.07
 3432.85   25.98 3469.09   18.97 3545.98   26.27 4255.56   27.54 4366.56   24.58
 5450.93   28.25  5911.3   23.77 5926.53   26.54 6429.67   28.89 9486.16    27.9
10956.76   21.5110972.54   16.3510978.39   18.6210993.59    5.3511009.54    4.09
11060.04   20.8311751.83   30.5212628.48   25.0513269.17   29.6317756.81    31.7
#Mann= 0 ,-1 , 0
#XS Ineff= 1 ,-1
       0    7700      40
Permanent Ineff=
       T
#Block Obstruct= 5 ,-1
      35 1401.94   29.18 1770.99 2198.47   26.11 3297.71 3664.12   25.65
13278.97   15000   29.137514.3048147.866    29.6
Bank Sta=10956.76,11060.04
XS Rating Curve= 0
Vertical n Elevations= 2
      23      30
Vertical n for Station=0
     .07      .1
Vertical n for Station=8890.92
     .12     .24
Vertical n for Station=10987.87
    .041    .041
Vertical n for Station=11017.91
     .12     .24
Vertical n for Station=14744.42
     .07      .1
Vertical n Flow= 0
Exp/Cntr=.3,.1