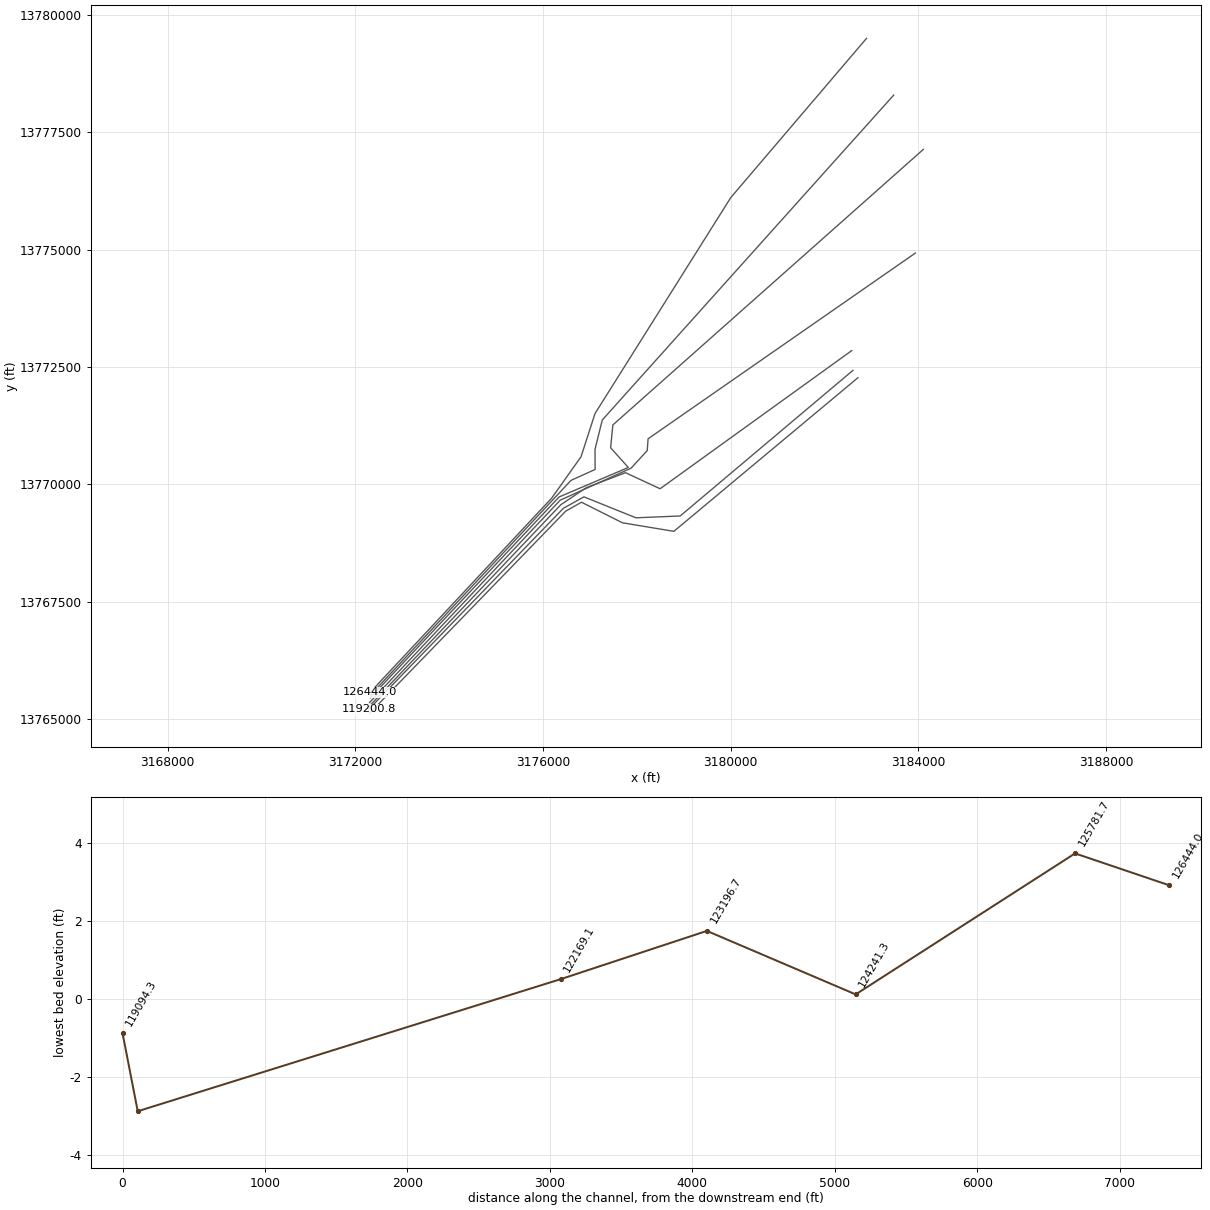
HEC-RAS study A100-00-00.prj: A100-00-00

--- A100-00-00.g01 (geometry) --- (continued)

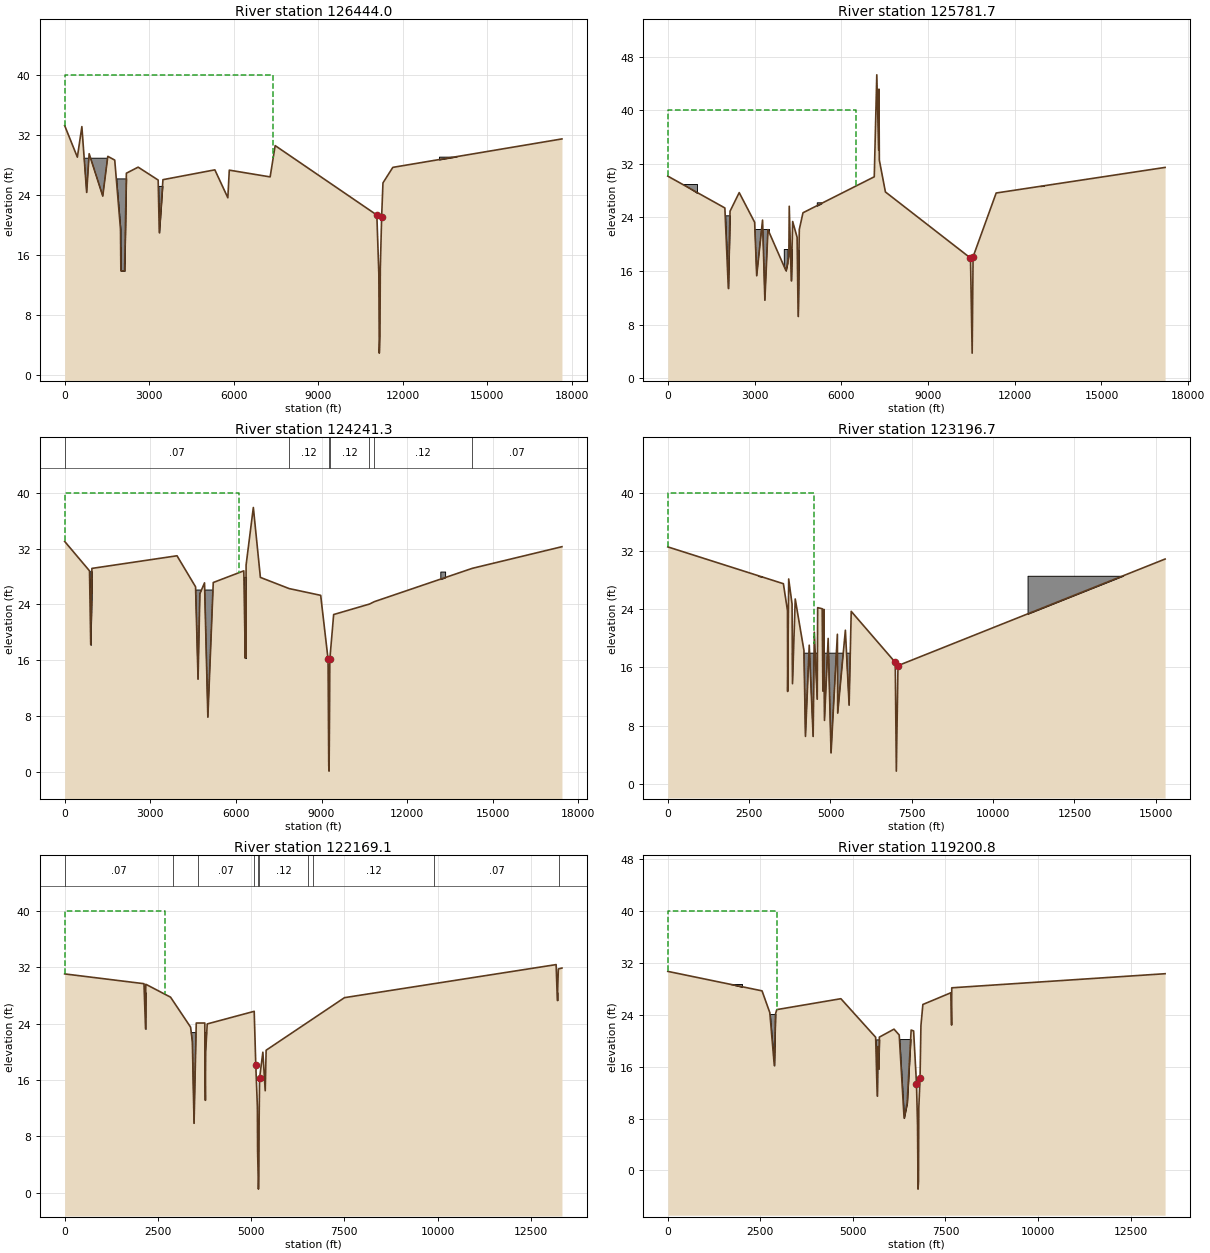
Type RM Length L Ch R = 1 ,126444.0,195.8,662.32,54.97
XS GIS Cut Line= 6
      3182894.16    13779504.095     3180001.198     13776111.44
     3177108.236       13771509.     3176809.475    13770587.029
      3176185.49    13769707.341     3172321.568    13765572.759
#Sta/Elev= 30
       0   33.24  451.42   29.03  611.07    33.1  781.72   24.33  869.53   29.49
 1352.69   23.85 1531.28   29.14 1777.96   28.64 1982.41   19.44 1995.28   13.88
 2128.41   13.88 2190.75   26.89 2608.55    27.7 3319.45   25.98 3359.08   18.97
 3489.28   26.03 5332.03   27.34 5792.77   23.62 5844.34    27.3 7294.37    26.4
 7472.78   30.5711082.28   21.3211152.82   13.5311168.95    2.92 11193.9    5.22
11205.13   14.1811252.92    21.111299.54    25.611649.67   27.6717653.26   31.46
#Mann= 0 ,-1 , 0
#XS Ineff= 1 ,-1
       0    7400      40
Permanent Ineff=
       T
#Block Obstruct= 4 ,-1
  215.37 1548.71   28.89 1648.85 2198.47    26.2 3267.18 3572.52    25.2
13289.56   15000    29.1
Bank Sta=11082.28,11252.92
XS Rating Curve= 0
Vertical n Elevations= 2
      23      30
Vertical n for Station=0
     .07      .1
Vertical n for Station=8668.15
     .12     .24
Vertical n for Station=11168.95
    .041    .041
Vertical n for Station=11189.32
     .12     .24
Vertical n for Station=14497.06
     .07      .1
Vertical n Flow= 0
Exp/Cntr=.3,.1

Type RM Length L Ch R = 1 ,125781.7,259.49,1540.39,56.13
XS GIS Cut Line= 6
     3183472.753    13778294.311     3177262.228     13771370.64
     3177108.236     13770746.31     3177110.164    13770317.446
     3176595.444    13770084.219     3172321.568    13765508.059
#Sta/Elev= 30
       0   30.16 1973.88   25.41 2093.34    13.4    2153   24.92 2469.58    27.7
 3004.45   23.27 3074.81   15.29 3277.42    23.6 3357.51   11.64 3464.16   22.17
 4087.55   16.04 4186.79   18.13 4200.48   25.66  4271.3   14.55 4318.83   23.39
 4472.51   21.03 4507.86    9.23 4548.23    22.2 4675.38   24.69 7140.99   30.06
 7228.41   45.28 7292.62   34.03 7303.24   43.14  7316.5   32.55 7526.41    27.8
10469.36   17.93 10527.1    3.7410559.27   18.1211357.62   27.6417200.02   31.46
#Mann= 0 ,-1 , 0
#XS Ineff= 1 ,-1
       0    6500      40
Permanent Ineff=
       T
#Block Obstruct= 8 ,-1
 -117.83 1020.26   28.93 1952.99 2168.22   24.31 2964.58 3517.01    22.2
 4012.05 4141.19   19.28 4205.75 4327.72   19.28 4464.03 4571.65   19.16
 5152.78 5310.61   26.2512891.19   14000   28.72
Bank Sta=10469.36,10559.27
XS Rating Curve= 0
Vertical n Elevations= 2
      23      30
Vertical n for Station=0
     .07      .1
Vertical n for Station=8265.55
     .12     .24
Vertical n for Station=10527.1
    .041    .041
Vertical n for Station=10534.73
     .12     .24
Vertical n for Station=14121.62
     .07      .1
Vertical n Flow= 0
Exp/Cntr=.3,.1

Type RM Length L Ch R = 1 ,124241.3,998.7,1044.56,63.87
XS GIS Cut Line= 6
     3184103.945    13777137.126     3177488.604    13771266.158
     3177440.407    13770780.263     3177817.537    13770359.673
     3176342.989     13769731.41     3172321.568    13765452.602
#Sta/Elev= 30
       0   33.04  870.74   28.82  913.57   18.24  954.79   29.17 3936.43   30.98
    4587   26.53 4673.69    13.3  4737.6   25.54 4900.66    27.1 5017.48    7.86
 5206.75   27.15 6276.43   28.82 6327.69   16.31 6335.23   25.92 6344.57   16.31
 6357.39   29.67 6610.69    37.9  6857.6   27.88 7864.53   26.28 8969.91   25.31
 9228.31   16.18 9252.84     .91 9264.25     .12 9283.97   10.29 9290.71   16.16
 9424.57   22.5610679.33   24.0610853.59   24.4114281.88   29.1817422.97   32.28
#Mann= 7 ,-1 , 0
       0     .07       0 7864.53     .12       0 9252.84    .081       0
 9283.97     .12       010679.33    .042       010853.59     .12       0
14281.88     .07       0
#XS Ineff= 1 ,-1
       0    6100      40
Permanent Ineff=
       T
#Block Obstruct= 5 ,-1
 -106.75 2727.84   28.77  796.95 1099.24   27.64 4396.95 5193.89   26.07
 6155.73 6403.05   27.9613161.9513329.54   28.72
Bank Sta=9228.31,9290.71
XS Rating Curve= 0
Vertical n Elevations= 2
      23      30
Vertical n for Station=0
     .07      .1
Vertical n for Station=7864.53
     .12     .24
Vertical n for Station=9252.84
    .041    .041
Vertical n for Station=9283.97
     .12     .24
Vertical n for Station=10679.33
    .042    .042
Vertical n for Station=10853.59
     .12     .24
Vertical n for Station=14281.88
     .07      .1
Vertical n Flow= 0
Exp/Cntr=.3,.1

Type RM Length L Ch R = 1 ,123196.7,1167.89,1027.61,79.21
XS GIS Cut Line= 6
     3183933.433    13774927.786     3178238.833    13770970.822
     3178221.098     13770720.21     3177876.793    13770344.859
     3176365.918    13769662.622     3172303.082    13765350.932
#Sta/Elev= 30
       0   32.57 3553.67   27.51 3679.36   23.81 3684.06    12.7 3716.38   28.16
 3820.18   24.71 3833.38   13.77 3917.43   25.41 4185.03   18.35 4232.09    6.52
 4348.13   19.06 4468.46    6.52 4504.04   20.85 4594.02   11.64 4607.41   24.22
 4746.21   24.07 4767.66   12.76  4795.1   23.99 4816.56    8.72 4929.85   19.99
 5018.38    4.26 5213.41   20.56 5223.36    9.73 5459.06   21.12 5574.35   10.82
 5638.49   23.71 6992.43    16.7  7025.8    1.75 7076.59   16.2515287.78    30.9
#Mann= 0 ,-1 , 0
#XS Ineff= 1 ,-1
       0    4500      40
Permanent Ineff=
       T
#Block Obstruct= 3 ,-1
 2361.98  2883.7   28.63 3541.98 5740.46   17.9611059.6715508.66    28.6
Bank Sta=6992.43,7076.59
XS Rating Curve= 0
Vertical n Elevations= 2
      23      30
Vertical n for Station=0
     .07      .1
Vertical n for Station=5018.38
     .12     .24
Vertical n for Station=5335.54
     .07      .1
Vertical n for Station=6212.17
     .12     .24
Vertical n for Station=7017.06
    .041    .041
Vertical n for Station=7038.48
     .12     .24
Vertical n for Station=8571.85
    .042    .042
Vertical n for Station=8725.87
     .12     .24
Vertical n for Station=12014.74
     .07      .1
Vertical n for Station=15287.78
     .15     .15
Vertical n Flow= 0
Exp/Cntr=.3,.1

Type RM Length L Ch R = 1 ,122169.1,1009,2968.34,102.44
XS GIS Cut Line= 6
     3182578.565    13772850.283     3178494.673    13769906.157
     3177757.676    13770248.631     3176923.763    13769930.069
      3176382.41    13769568.307      3172293.84    13765267.746
#Sta/Elev= 30
       0   31.05 2127.23   29.66 2169.71   23.24 2175.61   29.58  2839.6   27.75
 3376.77    23.5 3424.57   21.45 3470.05    9.85 3529.03   24.08  3758.4   24.08
 3762.53    18.3 3774.32   13.11 3780.53   19.95 3823.17   23.95 5082.82   25.74
 5125.48   18.12  5168.2    12.2 5174.36     5.9 5196.52     .51 5208.24    2.26
 5215.56   10.55  5227.4   16.29 5315.14   19.94 5378.43   14.47 5402.88   20.22
 7504.73   27.6813179.57   32.3713212.06   27.2913238.67   31.7513335.64   31.88
#Mann= 10 ,-1 , 0
       0     .07       0 2905.04     .12       0 3578.08     .07       0
 5075.54     .12       0 5181.83    .081       0 5210.23     .12       0
 6520.73    .042       0 6662.35     .12       0 9903.31     .07       0
13260.56     .15       0
#XS Ineff= 1 ,-1
       0    2700      40
Permanent Ineff=
       T
#Block Obstruct= 3 ,-1
 1277.87 2389.68   28.43 3270.23  3868.7   22.72 9239.79 14027.1   28.42
Bank Sta=5125.48,5227.4
XS Rating Curve= 0
Vertical n Elevations= 2
      24      31
Vertical n for Station=0
     .07      .1
Vertical n for Station=2931.77
     .12     .24
Vertical n for Station=3738.28
     .07      .1
Vertical n for Station=5082.82
     .12     .24
Vertical n for Station=5182.65
    .041    .041
Vertical n for Station=5213.64
     .12     .24
Vertical n for Station=6545.24
    .042    .042
Vertical n for Station=6751.06
     .12     .24
Vertical n for Station=9939.25
     .07      .1
Vertical n for Station=13335.64
     .15     .15
Vertical n Flow= 0
Exp/Cntr=.3,.1

Type RM Length L Ch R = 1 ,119200.8,357.36,106.45,91.17
XS GIS Cut Line= 6
     3182604.864    13772429.488     3178922.913    13769326.129
     3177979.678    13769287.342     3176872.398    13769733.694
     3176434.706    13769490.652     3172284.597    13765203.047
#Sta/Elev= 30
       0   30.67 2545.97   27.67 2755.47   24.32 2877.59   16.15 2908.36   24.08
 2944.54   24.78 4676.01   26.46 5615.07   20.52 5657.23   11.47 5669.86   19.08
 5697.99   15.63 5715.24   20.54 6110.78   21.77 6251.25   20.87 6383.42    8.06
 6466.23    10.4 6573.52   21.63 6640.41   21.49 6718.06   13.35 6746.52    7.04
 6760.22   -2.88 6772.28   -1.72  6780.7    9.63  6814.1   14.24 6838.17   22.31
 6890.42   25.57 7648.75   27.38 7666.24    22.4 7670.86   28.1413433.77   30.31
#Mann= 0 ,-1 , 0
#XS Ineff= 1 ,-1
       0    2960      40
Permanent Ineff=
       T
#Block Obstruct= 6 ,-1
 1354.84 2007.17    28.7 2586.26 3163.36   24.11 5543.29 5740.06   20.19
 6198.47 6583.21   20.24    9500   12000    28.313135.0413418.09   28.58
Bank Sta=6718.06,6814.1
XS Rating Curve= 0
Vertical n Elevations= 2
      23      30
Vertical n for Station=0
     .07      .1
Vertical n for Station=2545.97
     .12     .24
Vertical n for Station=3079.3
     .07      .1
Vertical n for Station=5567.05
     .12     .24
Vertical n for Station=5773.83
     .07      .1
Vertical n for Station=6110.78
     .12     .24
Vertical n for Station=6491.65
     .07      .1
Vertical n for Station=6640.41
     .12     .24
Vertical n for Station=6753.19
    .041    .041
Vertical n for Station=6775.29
     .12     .24
Vertical n for Station=9941.37
     .07      .1
Vertical n for Station=13314.19
     .15     .15
Vertical n Flow= 0
Exp/Cntr=.3,.1

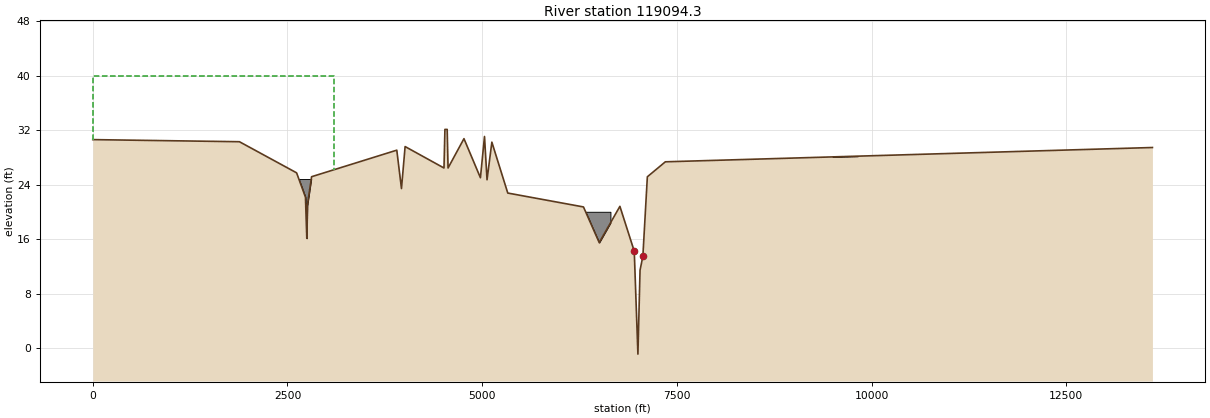
Type RM Length L Ch R = 1 ,119094.3,318.57,397.07,169.8
XS GIS Cut Line= 6
     3182710.063     13772271.69     3178787.893    13768998.694
     3177691.031    13769181.504     3176819.858    13769619.237
     3176484.188    13769429.519     3172303.082    13765119.861
#Sta/Elev= 30
       0   30.63 1883.26   30.32 2617.51   25.75 2731.32   22.17 2748.43   16.13
  2755.3   20.96 2809.83   25.18 3903.97   29.08 3964.19   23.44 4010.77   29.61
 4510.08   26.46    4522   32.13 4551.11   32.13 4562.29   26.46 4766.56   30.77
 4978.01   25.03 5030.29   31.09 5062.82   24.73 5124.81   30.26 5329.16   22.78
 6301.33   20.74 6503.58    15.5 6768.99   20.83 6953.33   14.24 7000.41    -.88
 7027.62   11.44 7064.01   13.51  7121.5   25.17 7352.66   27.3713607.39   29.47
#Mann= 0 ,-1 , 0
#XS Ineff= 1 ,-1
       0    3100      40
Permanent Ineff=
       T
#Block Obstruct= 4 ,-1
 2479.39 2821.37   24.84 6219.85 6647.33   20.03    9500   12500    28.2
12914.7813683.38    28.2
Bank Sta=6953.33,7064.01
XS Rating Curve= 0
Vertical n Elevations= 2
      23      30
Vertical n for Station=0
     .07      .1
Vertical n for Station=2617.51
     .12     .24
Vertical n for Station=2898.56
     .07      .1
Vertical n for Station=5986.47
     .12     .24
Vertical n for Station=6547.38
     .07      .1
Vertical n for Station=6603.06
     .12     .24
Vertical n for Station=6650.12
     .07      .1
Vertical n for Station=6859.2
     .12     .24
Vertical n for Station=7000.41
    .041    .041
Vertical n for Station=7014.1
     .12     .24
Vertical n for Station=10108.97
     .07      .1
Vertical n for Station=13444.51
     .15     .15
Vertical n Flow= 0
Exp/Cntr=.3,.1