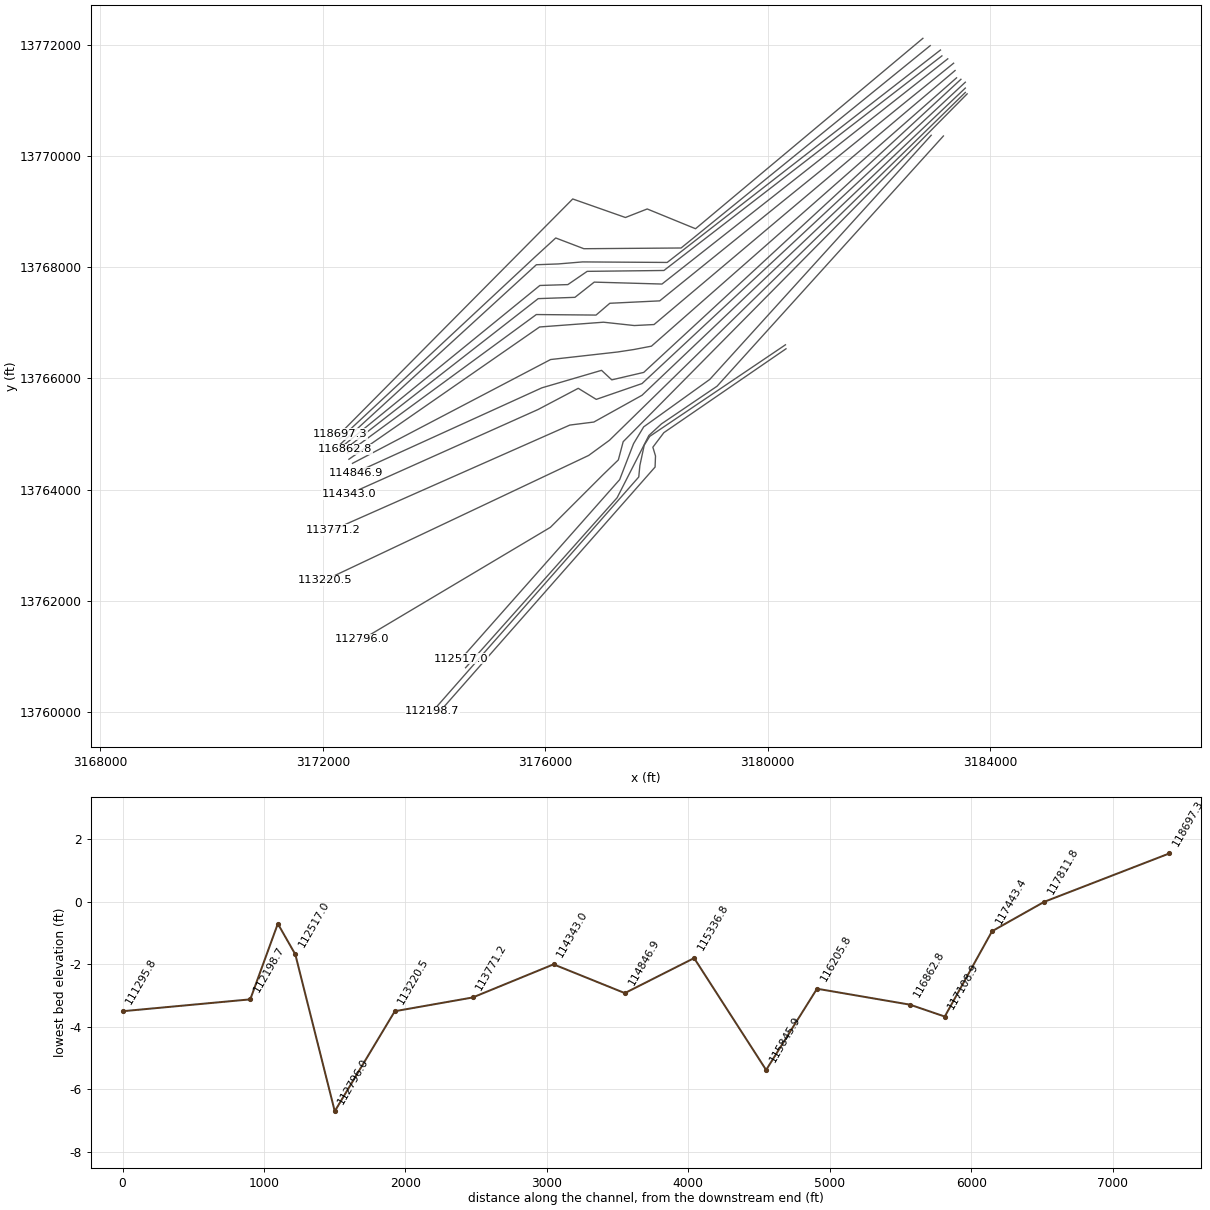
HEC-RAS study A100-00-00.prj: A100-00-00

--- A100-00-00.g01 (geometry) --- (continued)

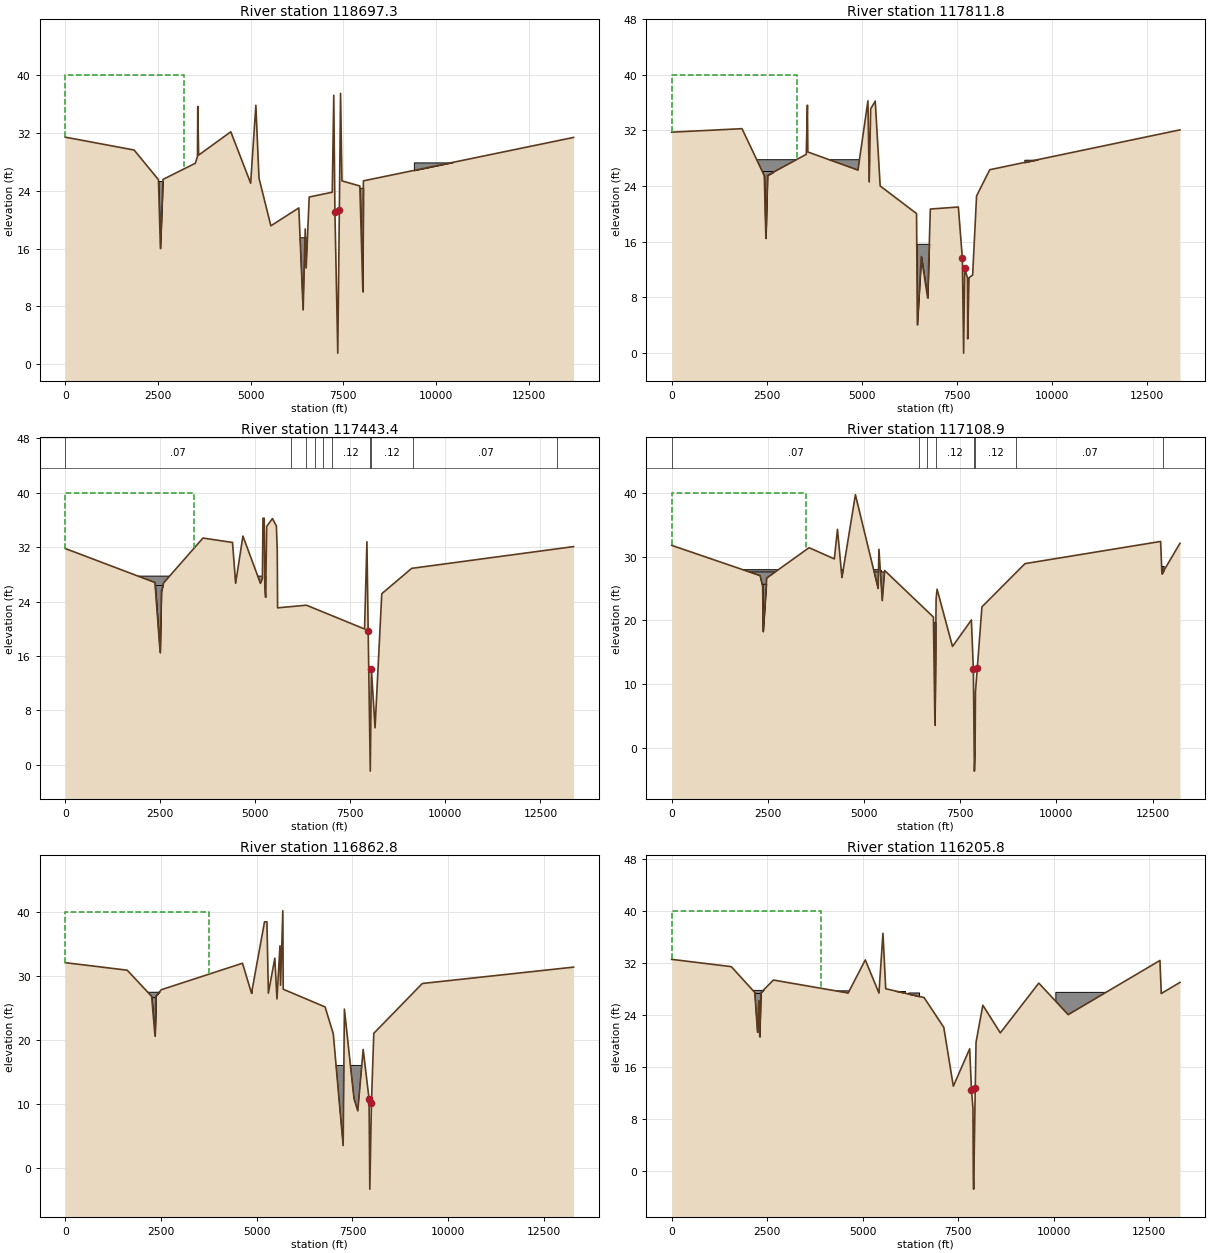
Type RM Length L Ch R = 1 ,118697.3,451.71,885.43,964.49
XS GIS Cut Line= 6
     3182788.962    13772113.892     3178701.298    13768690.803
     3177832.351    13769046.171     3177440.869    13768892.856
      3176493.44    13769225.963     3172303.082    13764999.705
#Sta/Elev= 30
       0   31.39 1858.44   29.61 2514.43   25.51 2566.89   16.02 2636.84   25.55
 3506.73   27.78  3566.2   28.72 3574.14   35.63 3597.76   28.91 4465.19   32.13
 5000.12   25.03 5140.51   35.79 5224.87   25.73 5544.84   19.14 6298.69   21.61
 6415.74    7.52 6471.53   18.71  6496.1   13.32 6578.97   23.12 7200.17   23.78
  7240.9   37.17  7272.3      21 7348.98    1.55 7391.51   21.26 7424.14   37.44
  7460.9   25.35 7943.75   24.64  8025.6   10.04 8039.58   25.3513705.47   31.35
#Mann= 0 ,-1 , 0
#XS Ineff= 1 ,-1
       0    3200      40
Permanent Ineff=
       T
#Block Obstruct= 5 ,-1
 2372.52  2714.5   25.34 6155.73 6647.33   17.49  7822.9 8036.64    24.4
    940013785.28    27.912745.5213899.64   28.62
Bank Sta=7272.3,7391.51
XS Rating Curve= 0
Vertical n Elevations= 2
      23      30
Vertical n for Station=0
     .07      .1
Vertical n for Station=6173.82
     .12     .24
Vertical n for Station=6415.74
     .07      .1
Vertical n for Station=7035.72
     .07      .1
Vertical n for Station=7200.17
     .12     .24
Vertical n for Station=7328.62
    .041    .041
Vertical n for Station=7353.12
     .12     .24
Vertical n for Station=10085.55
     .07      .1
Vertical n for Station=13455.05
     .15     .15
Vertical n Flow= 0
Exp/Cntr=.3,.1

Type RM Length L Ch R = 1 ,117811.8,264.44,368.45,364.79
XS GIS Cut Line= 6
      3182920.46    13771982.394     3178441.515    13768344.425
     3176693.719    13768331.596     3176188.054    13768524.678
     3175815.614    13768183.679     3172303.082    13764907.277
#Sta/Elev= 30
       0   31.76 1849.74   32.26 2436.06   25.51    2478    16.5 2521.15   25.55
 3539.03   28.57 3570.08   35.63 3580.79   28.91  4899.1   26.31 5161.11   36.26
 5195.29   24.62 5233.28   35.12 5353.53   36.22 5482.62   24.03 6439.58   20.06
 6460.39    4.09 6564.73   13.89 6732.34    7.93 6802.07   20.71    7539      21
 7644.68   13.63 7677.82       0  7705.9   12.18    7780   10.79 7784.55    2.05
 7818.51   10.83 7915.02   11.23 8017.75   22.59 8364.17   26.3613367.73   32.09
#Mann= 0 ,-1 , 0
#XS Ineff= 1 ,-1
       0    3300      40
Permanent Ineff=
       T
#Block Obstruct= 4 ,-1
 1791.51 5370.72    27.8 2329.77 2671.76   26.18 6305.34 6903.82   15.71
 9274.8813849.81    27.8
Bank Sta=7644.68,7705.9
XS Rating Curve= 0
Vertical n Elevations= 2
      23      30
Vertical n for Station=0
     .07      .1
Vertical n for Station=5839.93
     .12     .24
Vertical n for Station=6452.27
     .07      .1
Vertical n for Station=6640
     .12     .24
Vertical n for Station=6889.98
     .07      .1
Vertical n for Station=7190.97
     .12     .24
Vertical n for Station=7671.42
    .041    .041
Vertical n for Station=7689.73
     .12     .24
Vertical n for Station=9323.33
     .07      .1
Vertical n for Station=13031
     .15     .15
Vertical n Flow= 0
Exp/Cntr=.3,.1

Type RM Length L Ch R = 1 ,117443.4,187.12,334.46,438.08
XS GIS Cut Line= 6
     3183104.558    13771903.495     3178191.354    13768084.642
     3176669.371    13768094.207     3176232.672    13768057.856
     3175839.654    13768043.406     3172303.082    13764805.606
#Sta/Elev= 30
       0   31.81 2360.67   26.81 2498.19    16.5 2530.61   25.55 2589.19   26.75
 3623.47   33.35 4401.22    32.7 4483.16    26.7 4674.56   33.64 5136.06   26.68
 5187.29    27.4 5201.98   36.27 5235.09   36.27 5250.51   26.25 5272.18   24.62
  5299.7   35.05 5450.93   36.22 5555.23   35.12 5577.92   31.47 5586.68   23.08
 6345.58   23.47 7874.45   19.97 7936.39    32.8 7969.28   19.74 8024.68    -.94
 8054.34   14.04 8150.31    5.43 8327.35   25.16 9113.79   28.8913371.21   32.09
#Mann= 10 ,-1 , 0
       0     .07       0 5934.68     .12       0 6345.58     .07       0
  6566.2     .12       0 6786.96     .07       0 7006.25     .12       0
 8009.22    .081       0 8037.17     .12       0 9159.28     .07       0
12946.54     .15       0
#XS Ineff= 1 ,-1
       0    3400      40
Permanent Ineff=
       T
#Block Obstruct= 3 ,-1
 1914.14 5495.97   27.75 2244.27 2629.01   26.4512511.3513297.49   28.49
Bank Sta=7969.28,8054.34
XS Rating Curve= 0
Vertical n Elevations= 2
      23      30
Vertical n for Station=0
     .07      .1
Vertical n for Station=5994.23
     .12     .24
Vertical n for Station=6345.58
     .07      .1
Vertical n for Station=6592.31
     .12     .24
Vertical n for Station=6801.99
     .07      .1
Vertical n for Station=7092.33
     .12     .24
Vertical n for Station=8009.27
    .041    .041
Vertical n for Station=8038.33
     .12     .24
Vertical n for Station=9189.06
     .07      .1
Vertical n for Station=12954.56
     .15     .15
Vertical n Flow= 0
Exp/Cntr=.3,.1

Type RM Length L Ch R = 1 ,117108.9,275.35,246.1,247.06
XS GIS Cut Line= 6
     3183130.857    13771798.297     3178132.906    13767940.168
     3176753.133    13767924.404     3176405.606    13767686.385
     3175902.512    13767670.683     3172340.054    13764768.635
#Sta/Elev= 30
       0   31.76 2299.07   27.01 2365.71   25.34 2377.95   18.23 2469.83   26.63
 3571.42   31.39 4228.15   29.63 4309.96   34.28 4426.16    26.7 4775.85   39.71
 5367.19      25 5387.48   31.14 5474.36   23.08 5536.17   27.81 6803.45   20.51
 6843.06    3.54 6873.63   23.42 6899.43   24.88 7299.64   15.89 7790.87   20.05
 7841.97    12.3 7869.32   -3.67 7885.48   -1.36 7896.29    8.77 7945.61   12.59
 8064.47    22.1 9184.64   28.8912709.14   32.3712743.89   27.2913213.15   32.09
#Mann= 8 ,-1 , 0
       0     .07       0 6436.39     .12       0 6639.87     .07       0
 6865.03     .12       0 7862.75    .081       0  7887.2     .12       0
 8943.46     .07       012780.29     .15       0
#XS Ineff= 1 ,-1
       0    3500      40
Permanent Ineff=
       T
#Block Obstruct= 5 ,-1
 1494.23 5430.69   27.94  1890.5 5545.33   27.59 2158.78 2543.51   25.73
 6625.95 6861.07   19.7112721.6412787.41   28.53
Bank Sta=7841.97,7945.61
XS Rating Curve= 0
Vertical n Elevations= 2
      23      30
Vertical n for Station=0
     .07      .1
Vertical n for Station=6442.47
     .12     .24
Vertical n for Station=6692.49
     .07      .1
Vertical n for Station=6870.02
     .12     .24
Vertical n for Station=7863.68
    .041    .041
Vertical n for Station=7888.3
     .12     .24
Vertical n for Station=8979.11
     .07      .1
Vertical n for Station=12788.31
     .15     .15
Vertical n Flow= 0
Exp/Cntr=.3,.1

Type RM Length L Ch R = 1 ,116862.8,324.88,657.04,365.62
XS GIS Cut Line= 6
     3183236.056    13771745.697     3178098.079    13767696.378
     3176879.912      13767730.9     3176532.938    13767457.324
     3175872.651    13767434.098      3172395.51    13764722.421
#Sta/Elev= 30
       0   32.15 1619.47   30.97 2257.21   26.88 2345.11   20.65 2367.71   26.93
 2510.74   27.92 4629.09   32.06 4864.56   27.37 5204.26   38.54 5267.51   38.54
 5304.67   27.37 5473.33   32.85 5529.05   26.47  5607.6   34.78 5622.12   28.63
 5682.11   40.26  5692.6   27.99 6785.74   25.22 6999.64   21.02 7257.32    3.54
 7289.46   24.88 7540.62    10.9 7639.13    8.96 7779.81   18.57 7933.54   10.86
 7953.39   -3.29 7995.67   10.15 8057.19   21.09 9324.22   28.8913272.56   31.45
#Mann= 0 ,-1 , 0
#XS Ineff= 1 ,-1
       0    3760      40
Permanent Ineff=
       T
#Block Obstruct= 6 ,-1
 1636.41 4548.16    27.6 2201.53 2458.02   26.75 4640.29 5113.58   27.76
 6967.94 7758.78   16.07 9996.1313559.73   27.4612310.6313397.85   28.54
Bank Sta=7933.54,7995.67
XS Rating Curve= 0
Vertical n Elevations= 2
      23      30
Vertical n for Station=0
     .07      .1
Vertical n for Station=6837.25
     .12     .24
Vertical n for Station=7947.46
    .041    .041
Vertical n for Station=7970.7
     .12     .24
Vertical n for Station=9116.55
     .07      .1
Vertical n for Station=12852.95
     .15     .15
Vertical n Flow= 0
Exp/Cntr=.3,.1

Type RM Length L Ch R = 1 ,116205.8,428.98,359.88,236.53
XS GIS Cut Line= 6
     3183341.255    13771666.798     3178057.119    13767393.962
     3177160.159    13767350.563     3176912.847    13767138.565
     3175838.864    13767148.013     3172441.724    13764657.721
#Sta/Elev= 30
       0   32.54 1560.96   31.42 2175.42   27.45 2247.77   21.34 2282.25   26.18
 2304.44   20.65 2335.35   27.42 2662.96   29.36  4619.2   27.37 5068.08   32.45
 5425.65   27.37 5530.34   36.54 5602.72   28.02 6606.26   26.67  7122.9   22.09
 7372.16   13.04 7800.06   18.79 7847.74   12.45  7886.5    9.62 7895.36    -.79
 7904.39   -2.78 7946.23   12.77 7966.81    19.8 8144.49   25.49  8602.5   21.24
 9609.59   28.8910378.97   24.0412780.74   32.3712815.06   27.2913305.44      29
#Mann= 0 ,-1 , 0
#XS Ineff= 1 ,-1
       0    3910      40
Permanent Ineff=
       T
#Block Obstruct= 5 ,-1
 1629.99 3057.73   27.85  1728.8 6486.48    27.3 6190.11 6475.66   27.45
10056.2513652.86   27.47    4000    6100    27.7
Bank Sta=7847.74,7946.23
XS Rating Curve= 0
Vertical n Elevations= 2
      23      30
Vertical n for Station=0
     .07      .1
Vertical n for Station=6870.52
     .12     .24
Vertical n for Station=7885.07
    .041    .041
Vertical n for Station=7916.13
     .12     .24
Vertical n for Station=9009.41
     .07      .1
Vertical n for Station=12898.54
     .15     .15
Vertical n Flow= 0
Exp/Cntr=.3,.1

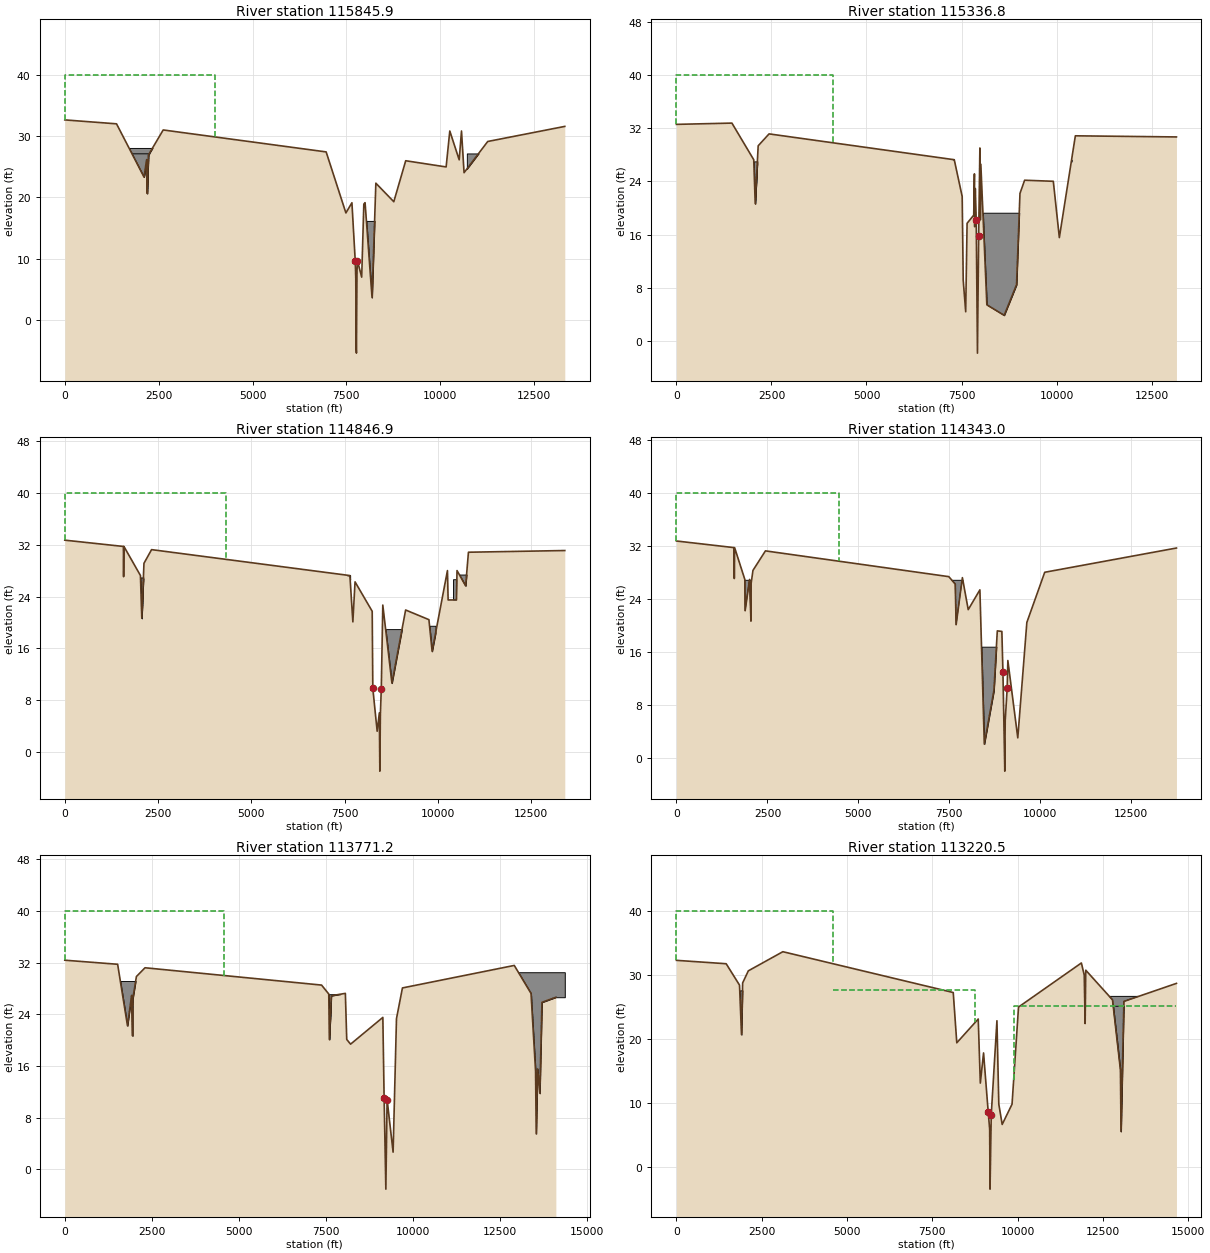
Type RM Length L Ch R = 1 ,115845.9,405.99,509.12,618.66
XS GIS Cut Line= 6
     3183367.554      13771535.3     3177955.341    13766968.345
     3177600.549    13766950.209     3177046.726    13767010.262
     3175897.542    13766924.502     3172469.453    13764546.808
#Sta/Elev= 30
       0   32.65 1378.36   32.01 2110.49   23.33 2180.33   26.18 2195.87   20.65
 2227.89   26.93 2621.39   31.01 6961.92   27.43 7488.08   17.48 7648.42   19.14
 7737.18     9.6 7751.03    6.84 7762.25   -4.68 7768.34   -5.38 7783.96    8.06
 7796.75    9.66 7908.52    7.01 7965.35   18.92 7998.56   19.15 8184.68    3.68
 8286.05   22.33  8763.9   19.31  9081.1   25.9910157.86   24.9810255.55   30.84
10505.65   26.1410567.28   30.8410635.39   24.0411265.45   29.1313318.55   31.59
#Mann= 0 ,-1 , 0
#XS Ineff= 1 ,-1
       0    4000      40
Permanent Ineff=
       T
#Block Obstruct= 5 ,-1
 1471.92 2759.86   28.08    1754 6934.96    27.2 6406.75 6959.02   27.44
 7972.52  8314.5   16.1810709.1411100.09   27.18
Bank Sta=7737.18,7796.75
XS Rating Curve= 0
Vertical n Elevations= 2
      23      30
Vertical n for Station=0
     .07      .1
Vertical n for Station=6850.17
     .12     .24
Vertical n for Station=7762.25
    .041    .041
Vertical n for Station=7796.75
     .12     .24
Vertical n for Station=9021.32
     .07      .1
Vertical n for Station=12831.21
     .15     .15
Vertical n Flow= 0
Exp/Cntr=.3,.1

Type RM Length L Ch R = 1 ,115336.8,483.28,489.9,603.26
XS GIS Cut Line= 6
     3183393.854    13771403.802     3177909.078    13766579.739
     3177592.424    13766519.149      3177298.18    13766474.482
     3176095.582    13766339.173     3172534.152    13764472.865
#Sta/Elev= 30
       0   32.56 1459.26   32.75 2033.46   27.25 2072.31   20.65 2150.18   29.34
 2436.77   31.13 7309.28   27.25 7517.81   21.72 7545.03    9.14 7610.06    4.41
 7646.64    17.7  7821.3   18.92 7839.65   25.12  7846.3   17.19 7862.64   22.92
 7886.88   18.23 7919.61    -1.8 7951.29   15.82 7983.47   29.01  7995.9   18.22
 8008.47   26.57 8166.79    5.46 8622.88    3.88 8948.26    8.48 9038.32   22.19
  9160.4   24.17 9915.43   24.0110074.28   15.5510495.36   30.8413155.43   30.67
#Mann= 0 ,-1 , 0
#XS Ineff= 1 ,-1
       0    4120      40
Permanent Ineff=
       T
#Block Obstruct= 6 ,-1
 1838.17  2222.9   26.73 1951.22 2168.87      27 7151.58 7307.05   26.61
 8036.64  9062.6   19.2910387.9211174.91   27.25    6500    7300    27.3
Bank Sta=7886.88,7951.29
XS Rating Curve= 0
Vertical n Elevations= 2
      23      30
Vertical n for Station=0
     .07      .1
Vertical n for Station=6911.25
     .12     .24
Vertical n for Station=7904.66
    .041    .041
Vertical n for Station=7926.58
     .12     .24
Vertical n for Station=9717.42
     .07      .1
Vertical n for Station=11099.02
     .15     .15
Vertical n for Station=11144.9
     .07      .1
Vertical n for Station=12607.04
     .15     .15
Vertical n Flow= 0
Exp/Cntr=.3,.1

Type RM Length L Ch R = 1 ,114846.9,202.93,503.92,359.17
XS GIS Cut Line= 6
     3183472.753    13771377.502      3177770.29    13766107.859
     3177195.218    13765973.667     3177011.582    13766144.869
     3175938.288    13765830.283     3172589.609    13764306.495
#Sta/Elev= 30
       0    32.7 1571.43   31.73  1576.6   27.07 1585.09   31.73 2027.92   27.25
 2064.33   20.65  2122.5   29.13 2326.48   31.24    7643   27.24  7722.3    20.1
 7780.91   26.27 8240.94   21.73 8257.16    9.85 8373.94    3.23 8432.17    6.07
 8445.49   -2.92  8460.2    5.89 8484.55    9.78 8524.95   22.69 8769.67   10.64
 9137.01   21.93 9761.13   20.44 9847.15   15.5510258.03   28.0110276.31   23.48
10499.85   23.4810514.48   28.0110745.59   25.6610820.79   30.8413403.59    31.1
#Mann= 0 ,-1 , 0
#XS Ineff= 1 ,-1
       0    4330      40
Permanent Ineff=
       T
#Block Obstruct= 8 ,-1
 1838.17 2244.27   26.73 1916.23 2157.22   26.95    6700    7650    27.3
 6856.56 7631.17   26.48 8549.62 9083.97   18.98 9746.56 9938.93    19.5
10421.5611086.92    26.610513.9311110.05    27.4
Bank Sta=8257.16,8484.55
XS Rating Curve= 0
Vertical n Elevations= 2
      23      30
Vertical n for Station=0
     .07      .1
Vertical n for Station=6935.34
     .12     .24
Vertical n for Station=7377.79
     .07      .1
Vertical n for Station=8204.47
     .12     .24
Vertical n for Station=8432.17
    .041    .041
Vertical n for Station=8460.2
     .12     .24
Vertical n for Station=10049.93
     .15     .15
Vertical n for Station=11699.25
     .07      .1
Vertical n for Station=12790.89
     .15     .15
Vertical n Flow= 0
Exp/Cntr=.3,.1

Type RM Length L Ch R = 1 ,114343.0,191.34,571.75,498.84
XS GIS Cut Line= 6
     3183551.652    13771324.903     3177739.428    13765907.174
     3176916.321    13765622.796     3176592.918    13765821.671
     3175870.481    13765440.703     3172469.453    13763918.297
#Sta/Elev= 30
       0   32.73 1583.29   31.73 1589.44   27.07 1598.23   31.73 1878.61   26.93
 1887.32   22.21 2009.57   26.93 2046.56   20.65 2051.94   26.32  2101.9   28.29
 2444.99   31.24 7483.49   27.35 7660.38   26.23 7684.67    20.1    7857    27.2
 8017.47   22.37 8337.86   25.36 8459.01    2.08 8723.45   10.16 8816.52   19.17
 8941.68   19.08  8970.8   12.99 9022.39      -2 9033.68    5.66 9087.85    10.5
  9106.3   14.69 9379.13    3.02  9628.1   20.44 10119.5   28.0113739.13   31.67
#Mann= 0 ,-1 , 0
#XS Ineff= 1 ,-1
       0    4460      40
Permanent Ineff=
       T
#Block Obstruct= 4 ,-1
 1733.13 7874.07    26.8 8293.13 8827.48   16.7810295.5911285.35   27.31
10353.4311094.89   26.62
Bank Sta=8970.8,9087.85
XS Rating Curve= 0
Vertical n Elevations= 2
      22      29
Vertical n for Station=0
     .07      .1
Vertical n for Station=7036.76
     .12     .24
Vertical n for Station=7310.18
     .07      .1
Vertical n for Station=8886.11
     .12     .24
Vertical n for Station=9015.39
    .041    .041
Vertical n for Station=9058.79
     .12     .24
Vertical n for Station=9776.37
     .15     .15
Vertical n for Station=12091.19
     .07      .1
Vertical n for Station=13110.74
     .15     .15
Vertical n Flow= 0
Exp/Cntr=.3,.1

Type RM Length L Ch R = 1 ,113771.2,194.81,550.69,654.04
XS GIS Cut Line= 5
     3183551.652    13771219.704     3177739.428    13765696.777
     3176873.239    13765215.342     3176441.496    13765160.967
     3172177.564    13763273.837
#Sta/Elev= 30
       0   32.36 1518.21   31.73 1801.48   22.21  1919.2   26.93 1947.31   20.65
 1952.02   26.32 2057.13   29.83  2304.7   31.19 7376.51   28.51 7583.43   27.13
 7599.67    20.1 7656.65   26.86  8059.9   27.23 8099.49    20.1 8209.57   19.37
 9136.84   23.51 9173.08   11.09 9223.15   -3.06 9259.01    10.8 9431.31    2.66
 9528.39   23.32 9699.84   28.0712912.26   31.5513393.45   27.2213524.08   15.16
13542.52    5.5113582.96   15.5413646.27   11.7613707.81   25.8414106.79   26.63
#Mann= 0 ,-1 , 0
#XS Ineff= 1 ,-1
       0    4570      40
Permanent Ineff=
       T
#Block Obstruct= 6 ,-1
 1172.52 2247.33   29.14 7405.19 8050.97    27.1 7474.81  7645.8   25.79
  9694.711132.05   27.3310125.8911043.89   26.4412922.1414363.36    30.5
Bank Sta=9173.08,9259.01
XS Rating Curve= 0
Vertical n Elevations= 2
      22      29
Vertical n for Station=0
     .07      .1
Vertical n for Station=6893.7
     .12     .24
Vertical n for Station=7194.7
     .07      .1
Vertical n for Station=9106.84
     .12     .24
Vertical n for Station=9213.71
    .041    .041
Vertical n for Station=9237.45
     .12     .24
Vertical n for Station=9528.39
     .15     .15
Vertical n for Station=12170.78
     .07      .1
Vertical n Flow= 0
Exp/Cntr=.5,.3

Type RM Length L Ch R = 1 ,113220.5,192.38,424.55,531.03
XS GIS Cut Line= 4
     3183551.652    13771140.805     3177154.233    13764888.067
     3176779.823     13764614.81      3172036.53     13762371.22
#Sta/Elev= 30
       0   32.26  1457.6   31.73 1848.31   28.39 1906.47   20.65  1940.2   28.73
 2106.88   30.62 3118.99   33.61 8113.41   27.23 8217.09   19.37 8845.74   23.09
 8907.14   13.07 9001.73   17.79 9136.97    8.63 9181.11    5.86 9191.65    -3.5
 9227.44    8.13 9394.05   22.82 9448.78    9.79 9547.98    6.61 9836.96    9.78
10026.77   24.9611869.58   31.85   11953   29.9611979.57   22.3911997.79   30.72
12781.43   26.0913013.94   15.1613031.49    5.5113115.76   25.8414656.25   28.66
#Mann= 0 ,-1 , 0
#XS Ineff= 3 ,-1
       0    4600      40    4600  8759.6   27.56 9883.7414656.25   25.09
Permanent Ineff=
       T       F       F
#Block Obstruct= 4 ,-1
 1709.92 2125.19   27.5710504.0913892.92   26.6312775.5713459.54   25.16
    7000    7500    27.2
Bank Sta=9136.97,9227.44
XS Rating Curve= 0
Vertical n Elevations= 2
      22      29
Vertical n for Station=0
     .07      .1
Vertical n for Station=6788.92
     .12     .24
Vertical n for Station=7137.04
     .07      .1
Vertical n for Station=9136.97
     .12     .24
Vertical n for Station=9180.1
    .041    .041
Vertical n for Station=9214.07
     .12     .24
Vertical n for Station=9349.28
     .07      .1
Vertical n for Station=10026.77
     .15     .15
Vertical n for Station=11900.62
     .07      .1
Vertical n for Station=14218.65
     .15     .15
Vertical n Flow= 0
Exp/Cntr=.5,.3

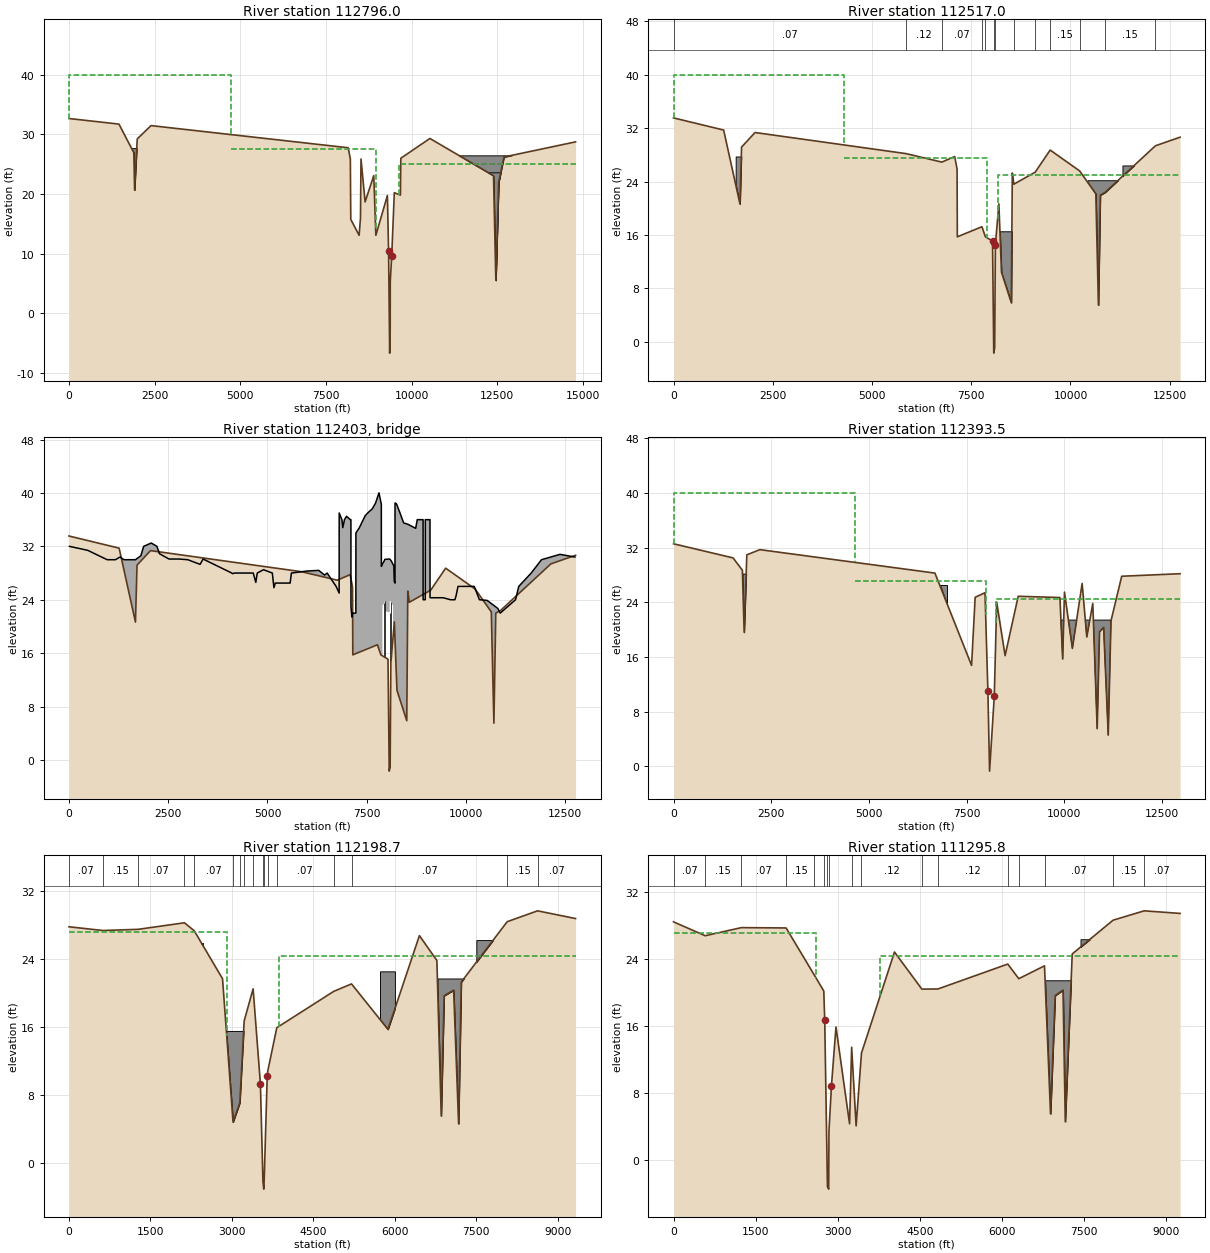
Type RM Length L Ch R = 1 ,112796.0,92.7,278.95,306.94
XS GIS Cut Line= 6
     3183584.579    13771115.362     3177400.372    13764861.695
     3177313.629     13764534.74     3177036.277    13764266.297
     3176091.799    13763322.373     3172710.774    13761308.942
#Sta/Elev= 30
       0   32.67 1458.95   31.73 1893.28   26.93 1915.53   20.65 1992.19   29.24
 2394.91   31.48 8152.02   27.76 8214.26   25.88 8227.02   15.74  8470.9   13.07
 8510.45   15.98 8525.43   25.88 8645.63   18.67 8898.34   23.09 8958.86   13.07
 9296.36   19.75 9330.79   10.42 9362.87    -6.7 9378.19   -2.58 9380.07    5.36
 9422.55    9.64 9497.98   20.22 9676.42   19.82 9688.12      2610537.77   29.32
12394.44   23.0712462.68    5.5112545.25   21.9912700.73   26.2114789.73   28.75
#Mann= 0 ,-1 , 0
#XS Ineff= 3 ,-1
       0    4740      40    4740 8953.11   27.52 9634.9214789.73   25.03
Permanent Ineff=
       T       F       F
#Block Obstruct= 3 ,-1
 1636.64 2174.05    27.710384.2914565.77   26.4912189.3112824.43   23.64
Bank Sta=9330.79,9422.55
XS Rating Curve= 0
Vertical n Elevations= 2
      22      29
Vertical n for Station=0
     .07      .1
Vertical n for Station=6798.42
     .12     .24
Vertical n for Station=7793.95
     .07      .1
Vertical n for Station=9018.69
     .12     .24
Vertical n for Station=9350.71
    .041    .041
Vertical n for Station=9389.51
     .12     .24
Vertical n for Station=9497.98
     .07      .1
Vertical n for Station=9548.67
     .15     .15
Vertical n for Station=10446.26
     .07      .1
Vertical n for Station=10710.43
     .15     .15
Vertical n for Station=11794.17
     .07      .1
Vertical n for Station=13885.45
     .15     .15
Vertical n Flow= 0
Exp/Cntr=.5,.3

Type RM Length L Ch R = 1 ,112517.0,175.01,123.51,199.09
XS GIS Cut Line= 6
 3182938.211357713770371.1193735     3178957.776    13765982.184
     3177769.427    13765128.696     3177587.207    13764827.269
     3177337.319    13764180.298 3174486.213072813760958.3966584
#Sta/Elev= 30
       0   33.551262.994   31.731674.703   20.651714.245   29.182053.987   31.36
5857.527    28.26759.588   26.937083.766   27.767143.558   25.887149.957   15.74
 7770.03   17.257857.431   15.748036.836    15.18067.727   -1.688091.015    -.87
 8108.75   14.53 8196.81   20.678262.125   10.448509.938    5.87 8535.38    25.3
8574.292   23.629111.582   25.429489.612   28.7310231.23   25.6110639.07   22.18
10704.85    5.5110752.42   21.9910870.42   22.38 12140.2   29.3712762.02   30.66
#Mann= 13 ,-1 , 0
       0     .07       05857.527     .12       06759.588     .07       0
 7770.03     .12       07857.431     .07       08067.727    .081       0
8091.015     .07       08574.292     .15       09111.582     .07       0
9489.612     .15       010231.23     .07       010870.42     .15       0
 12140.2     .07       0
#XS Ineff= 3 ,-1
       04304.146      404304.1467896.367    27.58164.62812762.02      25
Permanent Ineff=
       T       F       F
#Block Obstruct= 4 ,-1
1565.4531713.544   27.778186.9188694.627   16.5710429.3311381.29   24.21
11310.1111998.82   26.43
Bank Sta=8036.836,8108.75
XS Rating Curve= 0
Vertical n Elevations= 2
      22      29
Vertical n for Station=0
     .07      .1
Vertical n for Station=5857.527
     .12     .24
Vertical n for Station=6759.588
     .07      .1
Vertical n for Station=7770.03
     .12     .24
Vertical n for Station=7857.431
     .07      .1
Vertical n for Station=8067.727
    .041    .041
Vertical n for Station=8091.015
     .07      .1
Vertical n for Station=8574.292
     .15     .15
Vertical n for Station=9111.582
     .07      .1
Vertical n for Station=9489.612
     .15     .15
Vertical n for Station=10231.23
     .07      .1
Vertical n for Station=10870.42
     .15     .15
Vertical n for Station=12140.2
     .07      .1
Vertical n Flow= 0
Skew Angle= 30
Exp/Cntr=.5,.3

Type RM Length L Ch R = 3 ,112403  ,,,
BEGIN DESCRIPTION:
FM2351
END DESCRIPTION:
Bridge Culvert--1,0,-1,-1, 0
Deck Dist Width WeirC Skew NumUp NumDn MinLoCord MaxHiCord MaxSubmerge Is_Ogee
5,114,2.6,30, 100, 100, , , .95, 0, 0,0,,
   12.12  473.72  961.29    1170 1285.05 1386.51 1674.89 1810.86 1881.01  2072.4
 2214.43 2279.38 2519.27 2771.28 2991.25 3303.02 3378.37 4100.63 4123.15 4162.98
  4641.9 4705.98 4743.22 4900.84 5122.54 5162.38 5197.02 5571.14 5603.19 5998.09
 6291.67  6438.9 6503.85 6729.02 6806.09 6806.96 6876.24 6897.03 6940.33 6992.29
 7088.42 7103.14 7104.01 7126.52 7147.31 7226.98 7227.85 7315.32 7463.41 7550.01
 7636.61 7723.21 7809.82 7868.71 7869.57 7895.55 7896.42 7938.85 7957.04 7957.91
 8079.15 8080.02 8080.88 8122.45 8164.89 8165.75 8183.94  8195.2 8212.52 8213.39
 8250.62 8335.49 8429.89 8548.54 8733.87  8773.7 8920.93 8921.79 8975.49 8976.35
    9095 9095.86 9428.42 9611.15 9722.87 9752.31 9800.8110209.5710235.5510340.34
10350.74 10535.210803.6710864.2911249.6711331.0811644.5811903.5212369.44 12745.3
      32    31.4      30      30    30.4      30      30    30.6      32    32.5
      32    30.9    30.1    30.1      30    29.3    30.1      28    27.9      28
      28    26.6      28    28.5      28    25.8    26.5    26.5      28    28.3
    28.4    27.7      28      26      25      37      36    34.8      36    36.5
      36      36      23    21.4      22      22      34    34.8   36.61   37.14
   37.59   38.48   40.02    38.3      29   29.38   29.38   29.78   30.05   30.05
    30.1    30.1    30.1   29.79   29.28   29.28   29.05   26.73    26.5    38.5
   38.37   37.07   35.52   35.28    34.7      36      36      24      24      36
      36    24.3    24.3      24      24    24.6      26      26    25.6      24
      24    23.9    22.7      22      24      26      28      30    30.8    30.4
                                                                                
                                                                                
                                                                                
                                                                                
                                                                                
                                                   23.09    23.5   23.89    22.3
   22.08      22    23.9    23.6   23.07
                                                                                
                                                                                
                                                                                
  103.92  565.51 1053.09  1261.8 1377.85 1478.31 1766.69 1902.66 1972.81  2164.2
 2306.23 2371.18 2611.07 2863.08 3083.05 3394.82 3470.16 4192.43 4214.95 4254.78
 4733.69 4797.78 4835.02 4992.64 5214.34 5254.18 5288.82 5662.94 5694.98 6089.89
 6383.47  6530.7 6595.65 6820.82 6897.89 6898.76 6968.04 6988.83 7032.13 7084.09
 7180.22 7194.94 7195.81 7218.32 7239.11 7318.78 7319.65 7407.12 7555.21 7641.81
 7728.41 7815.01 7901.62  7960.5 7961.37 7987.35 7988.22 8030.65 8048.84 8049.71
 8170.95 8171.82 8172.68 8214.25 8256.69 8257.55 8275.74    8287 8304.32 8305.18
 8342.42 8427.29 8521.69 8640.33 8825.67  8865.5 9012.73 9013.59 9067.29 9068.15
  9186.8 9187.66 9520.22 9702.95 9814.67 9844.11 9892.6110301.3710327.3510432.14
10442.53   1062710895.4610956.0911341.4711422.8711736.3811995.3212461.2412837.09
      32    31.4      30      30    30.4      30      30    30.6      32    32.5
      32    30.9    30.1    30.1      30    29.3    30.1      28    27.9      28
      28    26.6      28    28.5      28    25.8    26.5    26.5      28    28.3
    28.4    27.7      28      26      25      37      36    34.8      36    36.5
      36      36      23    21.4      22      22      34    34.8   36.61   37.14
   37.59   38.48   40.02    38.3      29   29.38   29.38   29.78   30.05   30.05
    30.1    30.1    30.1   29.79   29.28   29.28   29.05   26.73    26.5    38.5
   38.37   37.07   35.52   35.28    34.7      36      36      24      24      36
      36    24.3    24.3      24      24    24.6      26      26    25.6      24
      24    23.9    22.7      22      24      26      28      30    30.8    30.4
                                                                                
                                                                                
                                                                                
                                                                                
                                                                                
                                                   23.09    23.5   23.89    22.3
   22.08      22    23.9    23.6   23.07
                                                                                
                                                                                
                                                                                
Pier Skew, UpSta & Num, DnSta & Num=  ,7938.854, 2 ,8030.652, 2 , 0 , 0 , 0 ,,
     2.5     2.5
     -30      28
     2.5     2.5
     -30      28
Pier Skew, UpSta & Num, DnSta & Num=  ,7957.042, 2 ,8048.84, 2 , 0 , 0 , 0 ,,
     2.5     2.5
       0      28
     2.5     2.5
       0      28
Pier Skew, UpSta & Num, DnSta & Num=  ,8080.016, 2 ,8171.815, 2 , 0 , 0 , 0 ,,
     2.5     2.5
       0      28
     2.5     2.5
       0      28
Pier Skew, UpSta & Num, DnSta & Num=  ,8122.452, 2 ,8214.251, 2 , 0 , 0 , 0 ,,
     2.5     2.5
       0      28
     2.5     2.5
       0      28
BR Coef=-1 , 1 , 1 ,1.05, 0 ,,,.8,-1,1.2,0,
WSPro=,,,, 1 ,,,, 0 ,,,, 0 ,,,,-1 ,-1 ,-1 , 0 , 0 , 0 , 0 , 0
BC Design=,, 0 ,, 0 ,,,,,,
BC HTab HWMax=33.55

Type RM Length L Ch R = 1 ,112393.5,65.37,194.86,51.01
XS GIS Cut Line= 6
 3183157.712334313770358.3130543     3179088.454    13765859.673
     3178087.954    13765181.784     3177862.842    13764974.081
     3177291.637    13763854.589 3174567.114932313760798.2460028
#Sta/Elev= 30
       0   32.551524.819   30.481762.258   28.681808.278    19.61875.992   30.93
2209.188   31.696689.967   28.267627.986   14.767719.932   24.727971.546   25.39
8045.505   11.038088.607     -.78209.305    10.38271.174   24.018486.147   16.19
8821.214   24.879889.309   24.699959.621    15.710005.73   25.4810208.36   17.25
10457.65   26.7510576.72   18.9310730.18   23.8210842.82    5.51   10903   19.66
11008.02   20.3211125.53    4.58 11196.3   21.2811470.54    27.8 12964.4   28.17
#Mann= 0 ,-1 , 0
#XS Ineff= 3 ,-1
       04641.896      404641.896  7988.4   27.148257.152 12964.4    24.4
Permanent Ineff=
       T       F       F
#Block Obstruct= 3 ,-1
 1650.07 1925.09   28.19 9900.4511360.14   21.39    5000    7000    26.5
Bank Sta=8045.505,8209.305
XS Rating Curve= 0
Vertical n Elevations= 2
      22      29
Vertical n for Station=0
     .07      .1
Vertical n for Station=5892.963
     .15     .15
Vertical n for Station=5988.324
     .07      .1
Vertical n for Station=8072.36
    .041    .041
Vertical n for Station=8106.006
     .07      .1
Vertical n for Station=11855.45
     .15     .15
Vertical n for Station=11980.01
     .07      .1
Vertical n Flow= 0
Skew Angle= 30
Exp/Cntr=.5,.3

Type RM Length L Ch R = 1 ,112198.7,91.23,902.89,107.82
XS GIS Cut Line= 6
     3180317.653    13766603.937       3177877.5    13764957.328
     3177779.078    13764800.271     3177700.637    13764434.651
      3177680.62    13764227.801     3173972.512    13760011.671
#Sta/Elev= 30
       0   27.79  623.54   27.35 1273.05   27.49 2124.91   28.26 2305.67   27.32
  2826.5   21.67 3020.37    4.77 3144.92    7.05 3225.25    16.7 3389.66   20.48
 3523.78    9.29 3570.79   -2.27 3586.29   -3.12 3593.74   -2.01 3649.37   10.18
 3659.64    10.8 3825.75    15.9 4873.67   20.18  5201.2   21.06 5872.46    15.7
 6451.13   26.75 6772.71   23.82 6853.12    5.51 6906.07   19.66 7081.08   20.32
 7172.74    4.58 7221.92   21.28 8067.25   28.39  8626.3   29.67 9325.67   28.76
#Mann= 17 ,-1 , 0
       0     .07       0  623.54     .15       0 1273.05     .07       0
 2124.91     .15       0 2305.67     .07       0 3020.37     .12       0
 3144.92     .12       0 3225.25     .07       0 3389.66     .12       0
 3570.79    .071       0 3593.74     .07       0 3659.64     .12       0
 3825.75     .07       0 4873.67     .12       0  5201.2     .07       0
 8067.25     .15       0  8626.3     .07       0
#XS Ineff= 2 ,-1
       0 2904.39   27.12 3858.12 9325.67   24.38
Permanent Ineff=
       F       F
#Block Obstruct= 6 ,-1
  173.41 2141.97    25.9 2305.43 2475.76   25.87 2793.89 3282.44   15.52
 5725.19    6000   22.54 6641.22 7312.98    21.7 7498.96 7902.18   26.22
Bank Sta=3523.78,3649.37
XS Rating Curve= 0
Vertical n Elevations= 2
      20      27
Vertical n for Station=0
     .07      .1
Vertical n for Station=623.54
     .15     .15
Vertical n for Station=1273.05
     .07      .1
Vertical n for Station=2124.91
     .15     .15
Vertical n for Station=2305.67
     .07      .1
Vertical n for Station=3020.37
     .12     .24
Vertical n for Station=3144.92
     .12     .24
Vertical n for Station=3225.25
     .07      .1
Vertical n for Station=3389.66
     .12     .24
Vertical n for Station=3570.79
    .041    .041
Vertical n for Station=3593.74
     .07      .1
Vertical n for Station=3659.64
     .12     .24
Vertical n for Station=3825.75
     .07      .1
Vertical n for Station=4873.67
     .12     .24
Vertical n for Station=5201.2
     .07      .1
Vertical n for Station=8067.25
     .15     .15
Vertical n for Station=8626.3
     .07      .1
Vertical n Flow= 0
Exp/Cntr=.5,.3

Type RM Length L Ch R = 1 ,111295.8,534.61,816.48,99.37
XS GIS Cut Line= 6
     3180327.901    13766532.205     3178131.788    13765024.544
     3177934.222    13764762.833     3177981.751    13764605.065
     3177974.078    13764406.284     3174074.993    13759977.511
#Sta/Elev= 30
       0   28.48  578.78   26.82 1240.17   27.79 2057.17   27.75 2575.88   22.08
 2745.71    20.2  2762.9   16.73 2812.33   -3.18 2835.03    -3.5 2840.21    3.43
 2885.68    8.86 2968.35    15.9 3216.85    4.32 3254.77   13.48 3336.56    4.07
 3433.89   12.77 4037.49   24.87 4538.04   20.43  4831.5   20.45 6107.35   23.43
  6308.7   21.68 6778.64   23.22 6888.98    5.51 6974.25   19.66 7116.95   20.32
 7158.49    4.58 7285.37   24.64 8032.07   28.68 8599.88    29.8 9256.02   29.49
#Mann= 17 ,-1 , 0
       0     .07       0  578.78     .15       0 1240.17     .07       0
 2057.17     .15       0 2575.88     .07       0 2745.71     .12       0
 2812.33    .071       0 2840.21     .12       0 3254.77    .042       0
 3433.89     .12       0 4538.04     .07       0  4831.5     .12       0
 6107.35     .07       0  6308.7     .12       0 6778.64     .07       0
 8032.07     .15       0 8599.88     .07       0
#XS Ineff= 2 ,-1
       0 2607.05   27.11  3772.2 9256.02   24.36
Permanent Ineff=
       F       F
#Block Obstruct= 2 ,-1
 6748.09 7282.44   21.49  7436.6 7777.87    26.4
Bank Sta=2762.9,2885.68
XS Rating Curve= 0
Vertical n Elevations= 2
      19      26
Vertical n for Station=0
     .07      .1
Vertical n for Station=578.78
     .15     .15
Vertical n for Station=1240.17
     .07      .1
Vertical n for Station=2057.17
     .15     .15
Vertical n for Station=2575.88
     .07      .1
Vertical n for Station=2745.71
     .12     .24
Vertical n for Station=2812.33
    .041    .041
Vertical n for Station=2840.21
     .12     .24
Vertical n for Station=3254.77
    .042    .042
Vertical n for Station=3433.89
     .12     .24
Vertical n for Station=4538.04
     .07      .1
Vertical n for Station=4831.5
     .12     .24
Vertical n for Station=6107.35
     .07      .1
Vertical n for Station=6308.7
     .12     .24
Vertical n for Station=6778.64
     .07      .1
Vertical n for Station=8032.07
     .15     .15
Vertical n for Station=8599.88
     .07      .1
Vertical n Flow= 0
Exp/Cntr=.5,.3