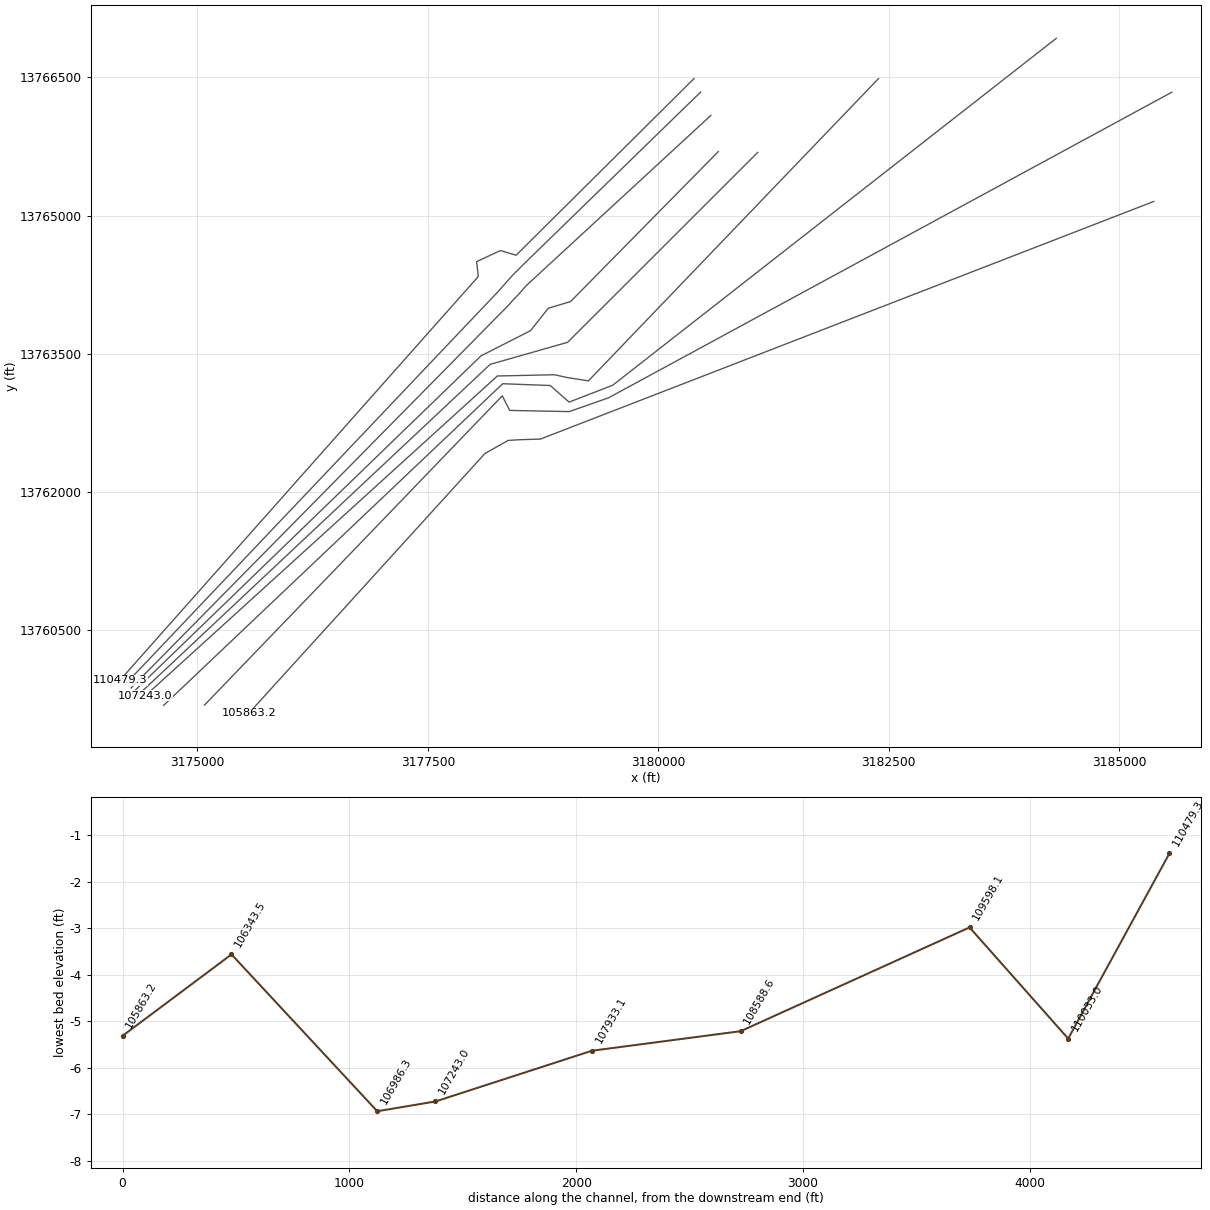
HEC-RAS study A100-00-00.prj: A100-00-00

--- A100-00-00.g01 (geometry) --- (continued)

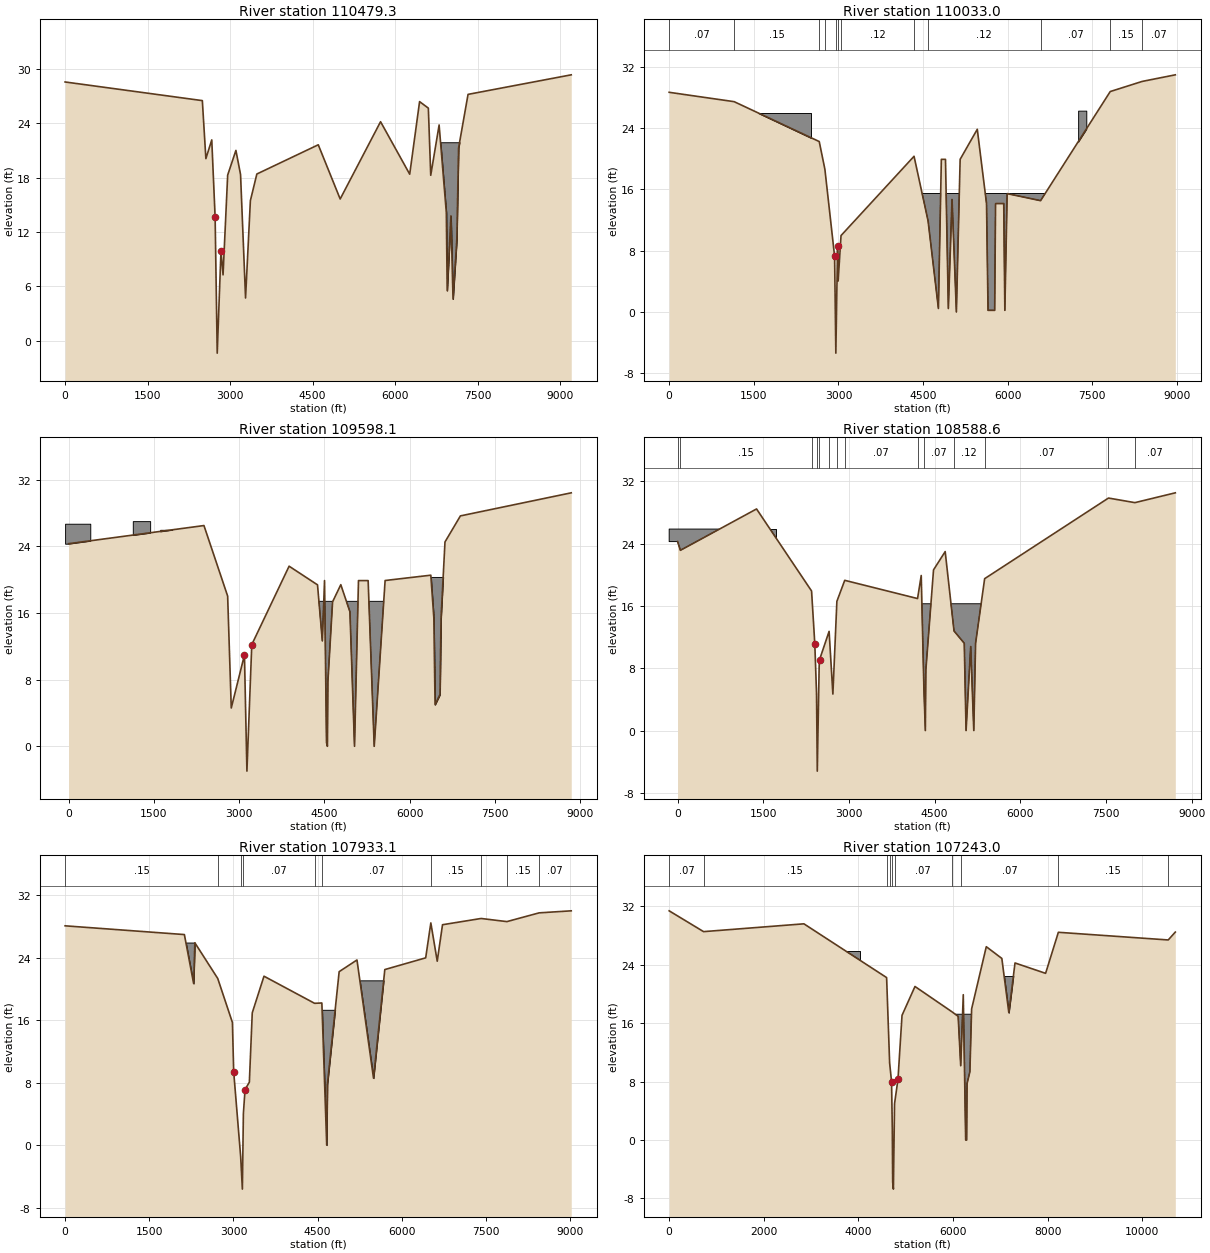
Type RM Length L Ch R = 1 ,110479.3,129.15,446.34,248.51
XS GIS Cut Line= 6
     3180388.084    13766487.389     3178457.644    13764570.398
     3178287.823    13764621.483     3178029.156    13764501.122
     3178047.117    13764339.476     3174160.393    13759960.431
#Sta/Elev= 30
       0   28.57 2494.93   26.51 2559.13    20.1 2666.12   22.17 2727.34   13.63
 2765.34   -1.39 2833.82    9.91  2871.4    7.26 2955.41   18.28 3105.05   21.01
 3189.38   18.35 3280.44     4.7 3368.23   15.46 3485.68    18.4 4602.39   21.63
 5000.54   15.64 5734.74   24.18  6264.5   18.38 6444.12    26.4 6603.31   25.68
  6646.8   18.26 6799.08   23.82 6930.27   14.13  6945.9    5.51  7013.9   13.77
 7052.19    4.58 7120.88   11.13 7153.15   21.28 7325.11    27.2 9200.98   29.36
#Mann= 0 ,-1 , 0
#Block Obstruct= 3 ,-1
  1610.5 2474.91      26 6778.63 7267.18   21.91 7425.98 7694.36   26.11
Bank Sta=2727.34,2833.82
XS Rating Curve= 0
Vertical n Elevations= 2
      19      26
Vertical n for Station=0
     .07      .1
Vertical n for Station=975.32
     .15     .15
Vertical n for Station=1640.57
     .07      .1
Vertical n for Station=2167.18
     .15     .15
Vertical n for Station=2666.12
     .07      .1
Vertical n for Station=2675.56
     .12     .24
Vertical n for Station=2765.34
    .041    .041
Vertical n for Station=2794.91
     .12     .24
Vertical n for Station=3169.78
    .042    .042
Vertical n for Station=3368.23
     .12     .24
Vertical n for Station=4602.39
     .07      .1
Vertical n for Station=4811.6
     .12     .24
Vertical n for Station=6781.42
     .07      .1
Vertical n for Station=8039.08
     .15     .15
Vertical n for Station=8643
     .07      .1
Vertical n Flow= 0
Exp/Cntr=.3,.1

Type RM Length L Ch R = 1 ,110033.0,195.7,434.85,162.99
XS GIS Cut Line= 5
     3180460.882    13766341.792     3178554.726    13764488.032
     3178414.602    13764347.908     3178254.461    13764167.748
     3174211.634     13759909.19
#Sta/Elev= 30
       0   28.64 1151.66   27.42 2659.54   22.22 2759.99    18.6 2931.76    7.27
 2953.86   -5.37 2984.56     8.6 2994.83    4.03  3045.8    9.96 4339.94    20.3
 4588.37   11.88 4771.72     .45 4823.74    19.9 4897.06    19.9 4947.85     .45
 5013.43   14.67 5090.22       0 5156.77    19.9 5460.61   23.82 5624.34   14.13
 5651.26     .21  5769.1     .21 5784.44   14.13 5929.44   14.13 5949.07     .21
 5990.05   15.43  6582.4   14.51 7816.86   28.74 8383.15   30.06 8970.08   30.92
#Mann= 12 ,-1 , 0
       0     .07       0 1151.66     .15       0 2659.54     .07       0
 2759.99     .12       0 2953.86    .071       0 2994.83    .042       0
  3045.8     .12       0 4339.94     .07       0 4588.37     .12       0
  6582.4     .07       0 7816.86     .15       0 8383.15     .07       0
#Block Obstruct= 3 ,-1
  -52.18 2517.08   25.98 4473.28 6839.69   15.45  7247.8 7392.42   26.25
Bank Sta=2931.76,2984.56
XS Rating Curve= 0
Vertical n Elevations= 2
      18      25
Vertical n for Station=0
     .07      .1
Vertical n for Station=1151.66
     .15     .15
Vertical n for Station=2659.54
     .07      .1
Vertical n for Station=2759.99
     .12     .24
Vertical n for Station=2953.86
    .041    .041
Vertical n for Station=2994.83
    .042    .042
Vertical n for Station=3045.8
     .12     .24
Vertical n for Station=4339.94
     .07      .1
Vertical n for Station=4588.37
     .12     .24
Vertical n for Station=6582.4
     .07      .1
Vertical n for Station=7816.86
     .15     .15
Vertical n for Station=8383.15
     .07      .1
Vertical n Flow= 0
Exp/Cntr=.3,.1

Type RM Length L Ch R = 1 ,109598.1,457.3,1009.48,154.69
XS GIS Cut Line= 6
     3180570.079    13766086.998     3178568.071    13764241.147
     3178467.983    13764127.713     3178421.275    13764081.005
     3178381.239    13764034.297     3174279.954     13759875.03
#Sta/Elev= 30
       0   24.33 2381.82   26.51 2798.61   18.04  2862.2     4.6 3094.12   10.97
 3137.58   -2.98  3223.1   12.21 3879.69   21.63 4379.54   19.39  4464.2   12.66
 4502.98    19.9  4537.7     .45 4553.74       0 4562.25    7.76 4644.68   17.35
 4789.29   19.41 4950.01   16.15  5030.4       0 5100.18    19.9 5270.21    19.9
 5377.14       0 5568.72   19.91 6372.59   20.55  6425.8   15.43 6447.38       5
 6533.94    6.22 6552.84   15.43 6622.01   24.54 6893.45   27.67 8843.17   30.44
#Mann= 0 ,-1 , 0
#Block Obstruct= 6 ,-1
  -61.07  381.68   26.73 1129.77 1435.11   27.04 1612.52    2140      26
 4381.68 5572.52   17.41 6229.01 6687.02   20.34 7099.57 7351.95   26.49
Bank Sta=3094.12,3223.1
XS Rating Curve= 0
Vertical n Elevations= 2
      18      25
Vertical n for Station=0
     .07      .1
Vertical n for Station=1066.12
     .15     .15
Vertical n for Station=2586.83
     .07      .1
Vertical n for Station=2671.56
     .12     .24
Vertical n for Station=2887.53
    .042    .042
Vertical n for Station=2937.36
     .12     .24
Vertical n for Station=3152.24
    .041    .041
Vertical n for Station=3199.77
     .12     .24
Vertical n for Station=3312.39
     .07      .1
Vertical n for Station=3617.97
     .12     .24
Vertical n for Station=4045.25
     .07     .07
Vertical n for Station=4464.2
     .12     .24
Vertical n for Station=4770.75
     .07      .1
Vertical n for Station=4899.79
     .12     .24
Vertical n for Station=6221.69
     .07      .1
Vertical n for Station=7745.52
     .15     .15
Vertical n for Station=8237.06
     .07      .1
Vertical n Flow= 0
Exp/Cntr=.3,.1

Type RM Length L Ch R = 1 ,108588.6,315.87,655.57,124.29
XS GIS Cut Line= 6
     3180651.746    13765695.333     3179048.496     13764067.66
     3178807.136    13763995.463     3178614.263    13763751.873
     3178076.861    13763478.639     3174297.035    13759823.789
#Sta/Elev= 30
       0   24.25   49.21   23.13 1382.33   28.44 2345.32   17.91 2401.85   11.16
 2432.27    4.76 2445.36   -5.21 2478.12    8.22 2484.52    9.08 2652.34   12.73
 2718.45    4.68 2788.47   16.58 2925.92   19.28 4200.76   16.94 4265.05    19.9
 4312.37    5.26 4337.29       0 4346.03    7.76  4480.4   20.62 4684.47   22.97
 4839.09   12.78 5018.39    11.2 5050.08       0 5131.45   10.78 5185.14       0
 5216.85    11.2 5375.11   19.49 7543.12   29.84 8005.64   29.25  8713.1   30.51
#Mann= 14 ,-1 , 0
       0     .07       0   49.21     .15       0 2345.32     .07       0
 2432.27    .071       0 2478.12     .07       0 2652.34    .042       0
 2788.47     .12       0 2925.92     .07       0 4200.76     .12       0
 4312.37     .07       0 4839.09     .12       0 5375.11     .07       0
 7543.12     .15       0 8005.64     .07       0
#Block Obstruct= 2 ,-1
 -147.55 1722.95   25.86 4061.07 5312.98   16.27
Bank Sta=2401.85,2484.52
XS Rating Curve= 0
Vertical n Elevations= 2
      18      25
Vertical n for Station=0
     .07      .1
Vertical n for Station=49.21
     .15     .15
Vertical n for Station=2345.32
     .07      .1
Vertical n for Station=2432.27
    .041    .041
Vertical n for Station=2478.12
     .07      .1
Vertical n for Station=2652.34
    .042    .042
Vertical n for Station=2788.47
     .12     .24
Vertical n for Station=2925.92
     .07      .1
Vertical n for Station=4200.76
     .12     .24
Vertical n for Station=4312.37
     .07      .1
Vertical n for Station=4839.09
     .12     .24
Vertical n for Station=5375.11
     .07      .1
Vertical n for Station=7543.12
     .15     .15
Vertical n for Station=8005.64
     .07      .1
Vertical n Flow= 0
Exp/Cntr=.3,.1

Type RM Length L Ch R = 1 ,107933.1,584.52,690.1,133.79
XS GIS Cut Line= 4
     3181079.667    13765686.608     3179016.546    13763625.534
     3178175.949    13763386.257     3174365.355    13759806.709
#Sta/Elev= 30
       0   28.08 2125.43   26.96 2290.41   20.69 2312.09   25.91 2719.71   21.34
 2981.31    15.7 3003.92    9.39 3127.63   -1.42 3158.73   -5.63 3176.76    4.07
 3206.65    7.12  3283.2    8.07 3334.72   16.94 3543.82   21.63 4445.02   18.16
 4574.85    18.2  4661.4       0 4673.01    7.76 4883.14   22.21 5200.79   23.71
 5495.59    8.57 5696.71   22.48 6424.87   23.98 6516.61   28.45 6630.74   23.55
 6724.63   28.22 7411.92   29.02 7871.68   28.62 8446.65   29.74  9018.4      30
#Mann= 10 ,-1 , 0
       0     .15       0 2719.71     .07       0 3127.63    .071       0
 3176.76     .07       0 4445.02     .12       0 4574.85     .07       0
 6516.61     .15       0 7411.92     .07       0 7871.68     .15       0
 8446.65     .07       0
#Block Obstruct= 3 ,-1
   -93.1 2310.93   25.94 4412.21 4961.83   17.33 5206.11 5740.46    21.1
Bank Sta=3003.92,3206.65
XS Rating Curve= 0
Vertical n Elevations= 2
      17      24
Vertical n for Station=0
     .15     .15
Vertical n for Station=2719.71
     .07      .1
Vertical n for Station=3127.63
    .041    .041
Vertical n for Station=3176.76
     .07      .1
Vertical n for Station=4445.02
     .12     .24
Vertical n for Station=4574.85
     .07      .1
Vertical n for Station=6516.61
     .15     .15
Vertical n for Station=7411.92
     .07      .1
Vertical n for Station=7871.68
     .15     .15
Vertical n for Station=8446.65
     .07      .1
Vertical n Flow= 0
Exp/Cntr=.3,.1

Type RM Length L Ch R = 1 ,107243.0,311,256.67,117.98
XS GIS Cut Line= 6
     3182390.036    13766487.389     3179242.001    13763206.899
      3179005.55    13763244.674     3178875.009    13763273.624
     3178254.461    13763260.279     3174433.676    13759789.629
#Sta/Elev= 30
       0   31.39  727.65   28.54 2849.29   29.61 4597.79   22.25 4661.88   10.54
 4702.14    7.99 4718.27    1.43 4725.93   -5.77 4741.39   -6.72 4765.46    4.97
 4837.88    8.31 4923.83   17.08 5197.69   21.03 5974.18   17.59 6110.62   16.94
 6164.66   10.18 6218.81    19.9 6269.45     .01 6290.04       0 6299.82    7.76
 6358.83    9.36 6395.19   17.95 6705.48   26.48 7034.32   24.87 7182.45   17.44
 7312.73   24.25 7959.58   22.83 8229.43   28.4510552.32    27.410702.23   28.48
#Mann= 10 ,-1 , 0
       0     .07       0  727.65     .15       0 4597.79     .07       0
 4661.88     .12       0 4718.27    .071       0 4765.46     .07       0
 5974.18     .12       0 6164.66     .07       0 8229.43     .15       0
10552.32     .07       0
#Block Obstruct= 3 ,-1
 2502.91 4036.39   25.88  5954.2 6448.85   17.23 6888.55 7328.24   22.46
Bank Sta=4702.14,4837.88
XS Rating Curve= 0
Vertical n Elevations= 2
      17      24
Vertical n for Station=0
     .07      .1
Vertical n for Station=727.65
     .15     .15
Vertical n for Station=4597.79
     .07      .1
Vertical n for Station=4661.88
     .12     .24
Vertical n for Station=4718.27
    .041    .041
Vertical n for Station=4765.46
     .07      .1
Vertical n for Station=5974.18
     .12     .24
Vertical n for Station=6164.66
     .07      .1
Vertical n for Station=8229.43
     .15     .15
Vertical n for Station=10552.32
     .07      .1
Vertical n Flow= 0
Exp/Cntr=.3,.1

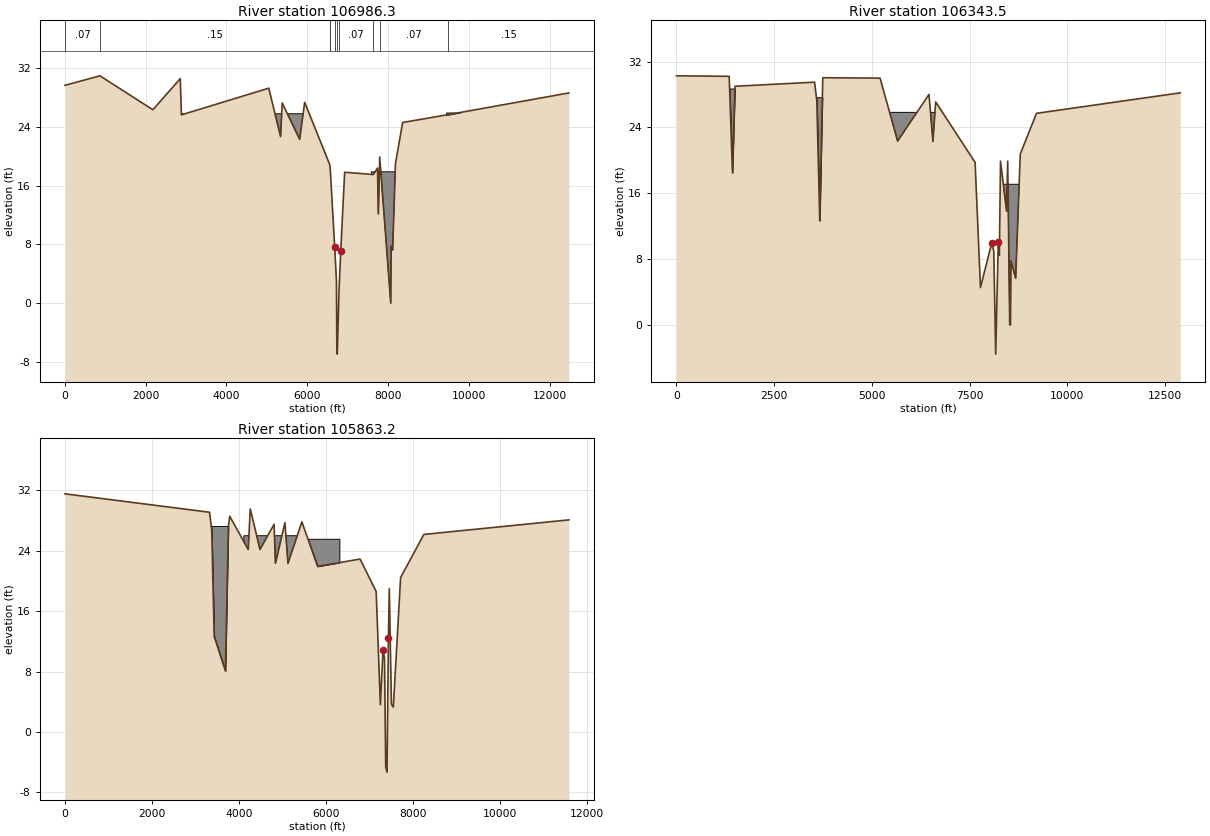
Type RM Length L Ch R = 1 ,106986.3,389.4,642.75,122.12
XS GIS Cut Line= 6
     3184319.191    13766924.179     3179505.363    13763159.327
      3179032.54    13762976.773     3178828.615    13763156.707
     3178312.144    13763176.133      3174632.78     13759686.14
#Sta/Elev= 30
       0   29.65     867   30.94 2177.16   26.32 2855.48   30.56  2883.5   25.63
 5047.24   29.26 5339.86   22.67 5379.59   27.25 5811.55   22.29  5935.9   27.34
  6559.1   18.83 6573.98   17.91 6678.86     7.7 6722.71    3.07 6731.82   -5.14
 6742.73   -6.93 6786.26    1.61  6828.8    7.04 6926.47   17.82 7635.68   17.51
 7739.84   18.38 7760.67   12.16 7794.12    19.9 8067.95       0 8078.05    7.76
 8114.82    7.24 8184.52   18.99 8362.23   24.59 9492.84   25.6612478.12   28.61
#Mann= 10 ,-1 , 0
       0     .07       0     867     .15       0  6559.1     .07       0
 6573.98     .12       0 6678.86     .07       0 6731.82    .071       0
 6786.26     .07       0 7635.68     .12       0 7794.12     .07       0
 9492.84     .15       0
#Block Obstruct= 3 ,-1
  946.23 5945.08   25.78 7587.79 8335.88   17.88 9438.7210273.67   25.95
Bank Sta=6678.86,6828.8
XS Rating Curve= 0
Vertical n Elevations= 2
      17      24
Vertical n for Station=0
     .07      .1
Vertical n for Station=867
     .15     .15
Vertical n for Station=6559.1
     .07      .1
Vertical n for Station=6573.98
     .12     .24
Vertical n for Station=6678.86
     .07      .1
Vertical n for Station=6731.82
    .041    .041
Vertical n for Station=6786.26
     .07      .1
Vertical n for Station=7635.68
     .12     .24
Vertical n for Station=7794.12
     .07      .1
Vertical n for Station=9492.84
     .15     .15
Vertical n Flow= 0
Exp/Cntr=.3,.1

Type RM Length L Ch R = 1 ,106343.5,380.48,480.31,307.35
XS GIS Cut Line= 6
     3185573.816    13766339.899     3179461.404    13763023.682
     3179034.798    13762873.626     3178387.912    13762886.615
     3178307.807    13763044.748     3175076.065    13759688.734
#Sta/Elev= 30
       0   30.27 1351.08   30.21 1434.56   18.49  1499.2      29 3535.52    29.5
 3592.46   27.26 3668.01   12.66 3745.69   30.04 5211.04   29.99 5660.45   22.34
  6462.5   28.01 6563.38   22.29 6633.16    27.1 7642.43   19.75 7779.28    4.53
 8066.04    9.93 8119.79    8.97  8168.9   -3.56 8235.59   10.08 8262.76    8.47
 8292.29    19.9 8447.55   13.83 8476.11    19.9 8527.99     .01 8547.12       0
 8558.04    7.76 8680.15    5.66 8797.75   20.76 9212.59   25.7112889.64    28.2
#Mann= 0 ,-1 , 0
#Block Obstruct= 5 ,-1
 1356.35 1500.88   28.73 3483.97 3804.58   27.67 3832.76 6630.37   25.83
 8335.88  8891.6   17.09  9212.810926.57    25.7
Bank Sta=8066.04,8235.59
XS Rating Curve= 0
Vertical n Elevations= 2
      17      24
Vertical n for Station=0
     .07      .1
Vertical n for Station=668.77
     .15     .15
Vertical n for Station=7436.81
     .07      .1
Vertical n for Station=7492.08
     .12     .24
Vertical n for Station=7774.65
    .042    .042
Vertical n for Station=7858.56
     .12     .24
Vertical n for Station=8168.9
    .041    .041
Vertical n for Station=8187.06
     .07      .1
Vertical n for Station=9262.69
     .15     .15
Vertical n for Station=12414.86
     .07      .1
Vertical n Flow= 0
Exp/Cntr=.3,.1

Type RM Length L Ch R = 1 ,105863.2,365.66,679.34,978.14
XS GIS Cut Line= 6
     3185376.948    13765153.998     3178721.396    13762575.551
     3178497.376    13762568.839     3178371.469     13762560.97
     3178119.657    13762419.325     3175555.699    13759599.072
#Sta/Elev= 30
       0   31.55 3325.34   29.11  3375.5   26.69 3431.76   12.66 3689.61    8.09
 3758.23   27.26 3790.42   28.57 4214.91   24.17 4261.72   29.55 4484.78   24.17
 4808.51   27.51 4840.87   22.34 5058.88   27.73 5128.52   22.34 5449.18   27.83
 5809.74   21.94 6786.98   22.91  7157.2    18.6 7253.82    3.62 7314.15    10.9
 7348.62    9.79 7376.69   -4.62 7406.23   -5.31 7438.86   12.39  7459.3   18.99
 7508.25    3.69 7551.45     3.3 7719.19   20.46 8253.87   26.1711588.27    28.1
#Mann= 0 ,-1 , 0
#Block Obstruct= 5 ,-1
 1836.62 3335.25   25.49 3297.71 3810.69    27.3 4113.95    5500      26
 8258.52 9918.76   25.64    5501 6310.48    25.6
Bank Sta=7314.15,7438.86
XS Rating Curve= 0
Vertical n Elevations= 2
      15      22
Vertical n for Station=0
     .15     .15
Vertical n for Station=6947.41
     .07      .1
Vertical n for Station=7001.03
     .12     .24
Vertical n for Station=7199.24
    .042    .042
Vertical n for Station=7339.6
     .12     .24
Vertical n for Station=7376.69
    .041    .041
Vertical n for Station=7417.77
     .12     .24
Vertical n for Station=8253.87
     .07      .1
Vertical n for Station=8747.73
     .12     .24
Vertical n for Station=9591.84
     .07      .1
Vertical n for Station=9712.88
     .15     .15
Vertical n for Station=10975.33
     .07      .1
Vertical n Flow= 0
Exp/Cntr=.3,.1