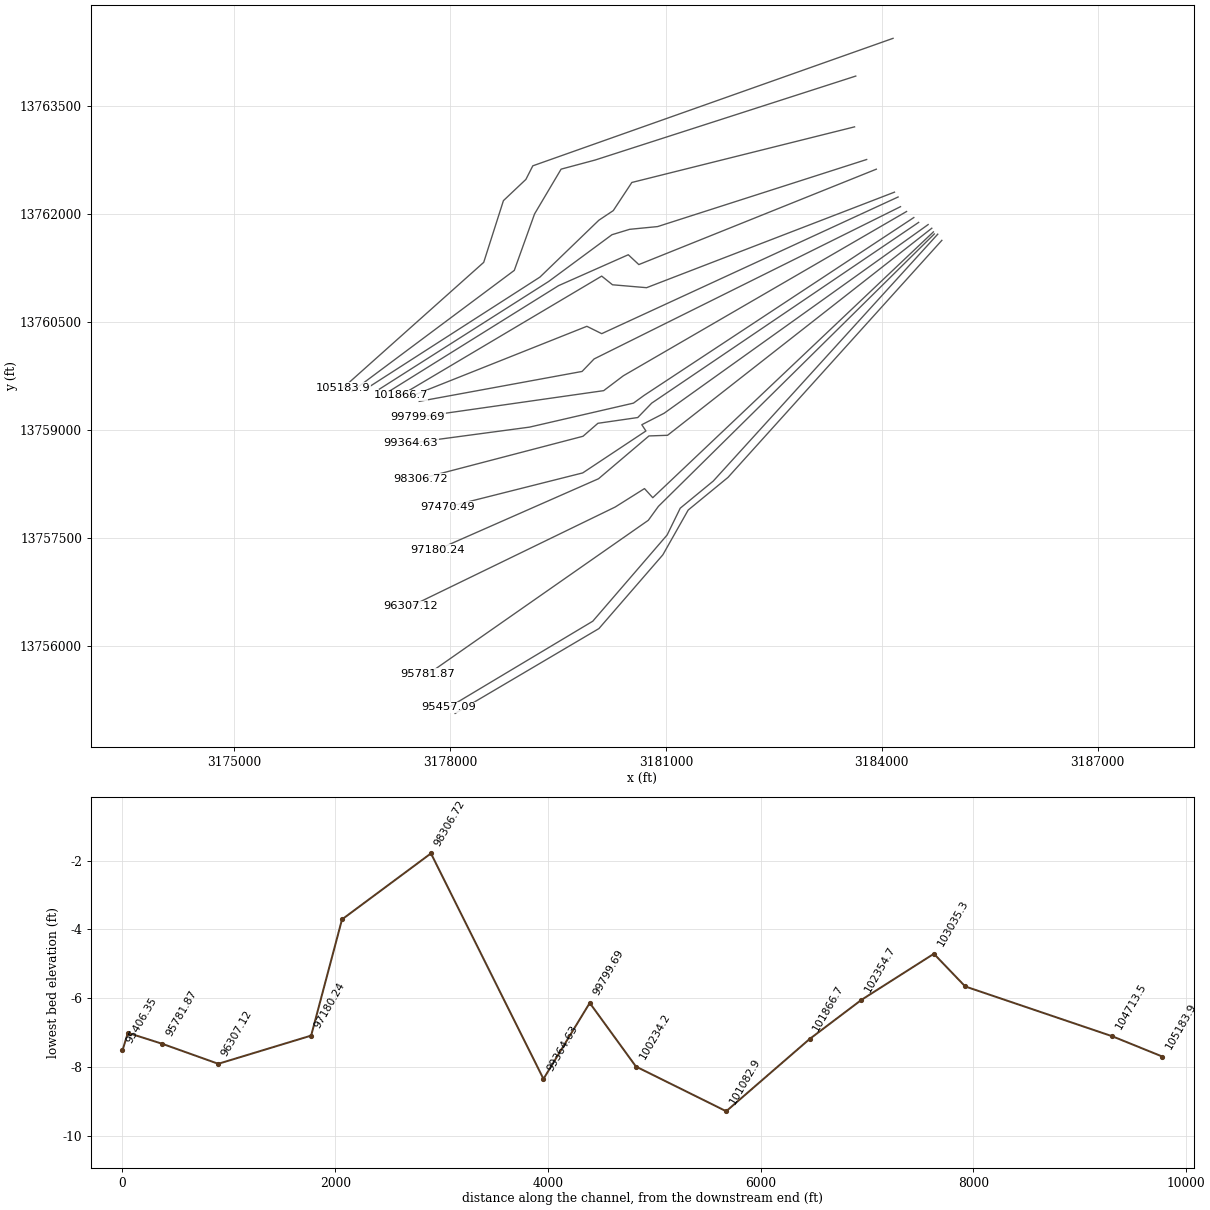
HEC-RAS study A100-00-00.prj: A100-00-00

--- A100-00-00.g01 (geometry) --- (continued)

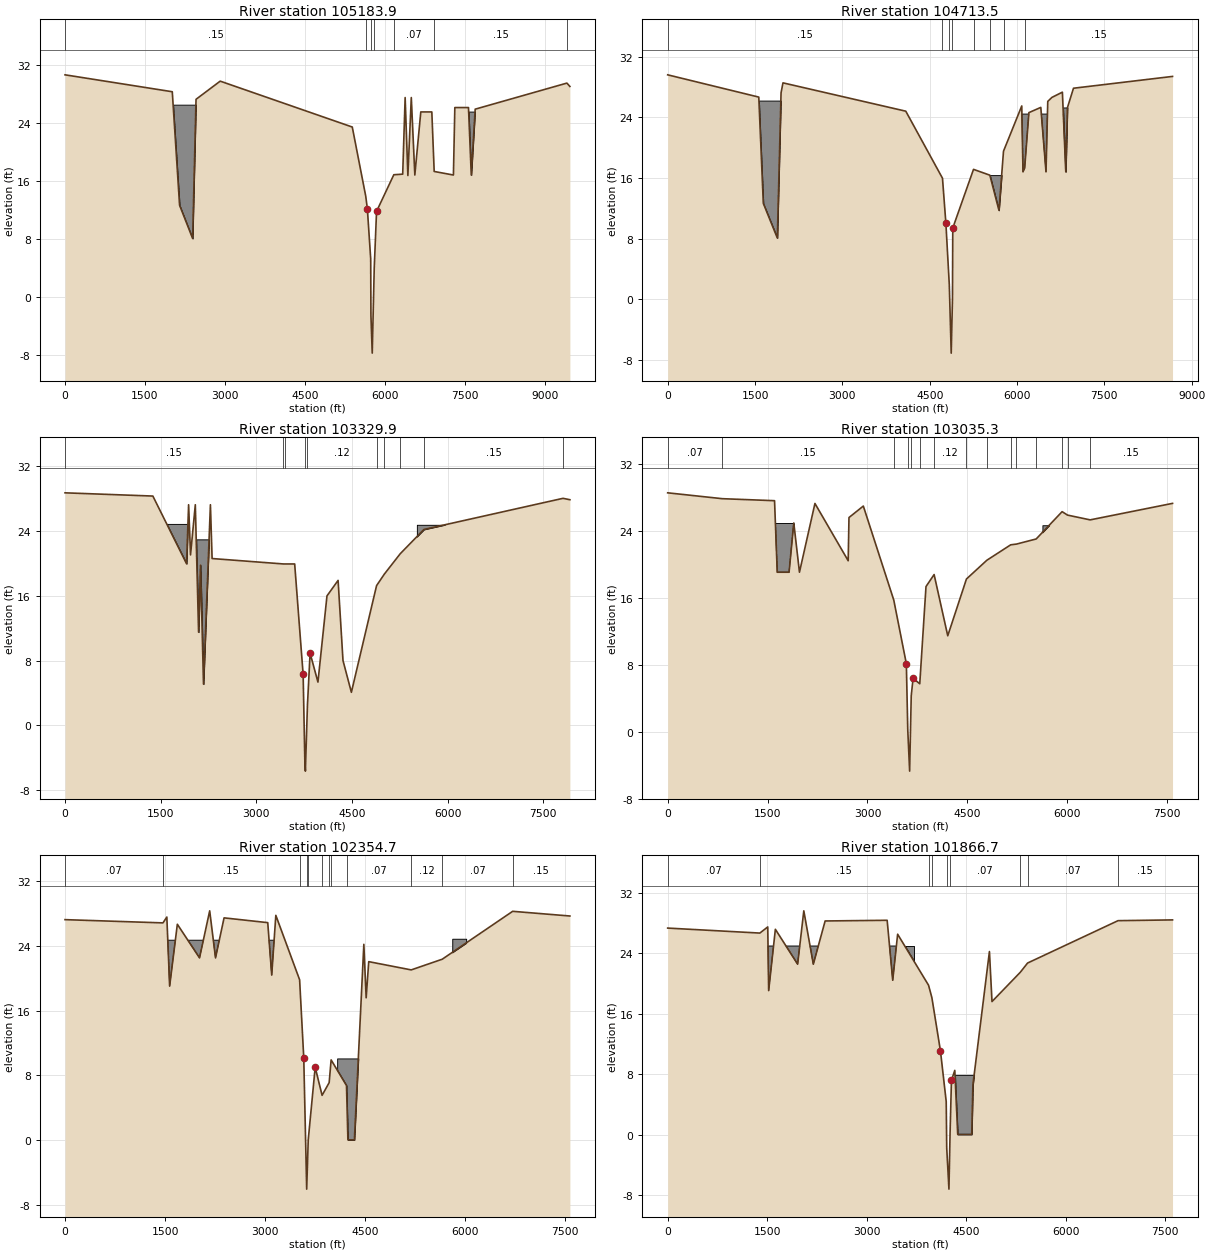
Type RM Length L Ch R = 1 ,105183.9,394.41,470.43,458.35
XS GIS Cut Line= 6
     3184157.999    13764440.042     3179151.231     13762668.23
     3179055.169    13762479.589     3178742.748     13762184.18
     3178468.857    13761326.612     3176513.445    13759581.658
#Sta/Elev= 30
       0   30.63 2012.46    28.3 2149.66   12.66 2394.57    8.09  2458.5   27.26
  2911.8   29.76  5390.1   23.44 5642.45   13.93 5673.17    12.2 5735.79    5.28
 5740.25   -2.52 5764.68    -7.7 5802.38    4.05 5845.76   11.82 6169.73   16.87
  6336.4   16.95 6382.21    27.5 6433.54   16.76 6497.75    27.5 6563.96   16.83
 6675.95   25.52 6882.91   25.52 6927.17   17.32 7288.14   16.83 7314.74   26.12
 7570.72   26.12 7623.18   16.83 7696.83    25.9 9417.19   29.49 9473.72   29.03
#Mann= 7 ,-1 , 0
       0     .15       0 5642.45     .12       0 5740.25    .071       0
 5802.38     .12       0 6169.73     .07       0 6927.17     .15       0
 9417.19     .07       0
#Block Obstruct= 4 ,-1
 1509.65 1821.87   25.65 1923.66 2534.35   26.52 2538.13 4539.97   25.62
 7515.02 7741.34   25.57
Bank Sta=5673.17,5845.76
XS Rating Curve= 0
Vertical n Elevations= 2
      15      22
Vertical n for Station=0
     .15     .15
Vertical n for Station=5642.45
     .12     .24
Vertical n for Station=5740.25
    .041    .041
Vertical n for Station=5802.38
     .12     .24
Vertical n for Station=6169.73
     .07      .1
Vertical n for Station=6927.17
     .15     .15
Vertical n for Station=9417.19
     .07      .1
Vertical n Flow= 0
Exp/Cntr=.3,.1

Type RM Length L Ch R = 1 ,104713.5,1006.24,1383.54,379.77
XS GIS Cut Line= 6
     3183639.617    13763915.593     3180018.656    13762749.189
     3179544.464    13762621.967     3179175.275    13761999.164
      3178893.73    13761214.821      3176635.34    13759529.417
#Sta/Elev= 30
       0   29.63 1564.58   26.69  1642.3   12.66 1883.06    8.09 1947.24   27.26
 1980.11   28.57 4089.11   24.83 4719.58   15.98 4778.23   10.01 4836.34    1.95
 4869.49   -7.11  4891.1     .06 4896.19     9.4 5252.48   17.15 5533.04   16.38
  5689.4   11.74 5767.59   19.55 6080.98   25.52 6102.22   16.83 6130.97   17.32
 6203.63   24.64 6407.95   25.33 6497.49   16.83 6527.75   26.12 6598.63   26.65
 6778.91   27.34 6836.87   16.83 6865.23   25.29 6969.45   27.86 8670.62   29.42
#Mann= 8 ,-1 , 0
       0     .15       0 4719.58     .12       0 4836.34    .071       0
  4891.1     .12       0 5252.48     .07       0 5533.04     .12       0
 5767.59     .07       0 6130.97     .15       0
#Block Obstruct= 5 ,-1
  758.48  1515.1   25.16 1480.92 1969.47   26.23 5435.11 5770.99   16.39
 6061.07 6916.03   24.45 6685.33 7079.61   25.32
Bank Sta=4778.23,4896.19
XS Rating Curve= 0
Vertical n Elevations= 2
      15      22
Vertical n for Station=0
     .15     .15
Vertical n for Station=4719.58
     .12     .24
Vertical n for Station=4836.34
    .041    .041
Vertical n for Station=4891.1
     .12     .24
Vertical n for Station=5252.48
     .07      .1
Vertical n for Station=5533.04
     .12     .24
Vertical n for Station=5767.59
     .07      .1
Vertical n for Station=6130.97
     .15     .15
Vertical n Flow= 0
Exp/Cntr=.3,.1

Type RM Length L Ch R = 1 ,103329.9,786.28,294.61,132.65
XS GIS Cut Line= 6
     3183622.811    13763209.745     3180527.545    13762436.916
     3180269.576    13762045.872     3180069.399     13761912.42
     3179250.282    13761121.882     3176826.889    13759564.245
#Sta/Elev= 30
       0   28.73 1377.59   28.33 1905.99   19.97 1938.29   27.26 1968.43   21.06
 2043.39   27.26 2094.77   11.51 2125.19   19.78 2171.96    5.09 2280.27   27.26
 2306.76   20.61 3426.04   19.94 3443.32   19.94 3601.81   19.94 3734.56    6.29
 3761.03   -4.29 3769.89   -5.66 3802.11    2.49 3843.76    8.92  3966.9    5.34
 4108.42   15.99 4282.82   17.91 4359.71    8.01 4491.29    4.08 4886.36   17.26
 5007.72   18.68 5258.28   21.21 5628.47    24.2 7810.57   28.05 7918.53   27.88
#Mann= 10 ,-1 , 0
       0     .15       0 3426.04     .07       0 3443.32     .12       0
 3761.03    .071       0 3802.11     .12       0 4886.36     .07       0
 5007.72     .12       0 5258.28     .07       0 5628.47     .15       0
 7810.57     .07       0
#Block Obstruct= 3 ,-1
  181.55 1940.15   24.89 2027.48 2283.97   22.98 5518.46 6534.12   24.78
Bank Sta=3734.56,3843.76
XS Rating Curve= 0
Vertical n Elevations= 2
      13      20
Vertical n for Station=0
     .15     .15
Vertical n for Station=3426.04
     .07      .1
Vertical n for Station=3443.32
     .12     .24
Vertical n for Station=3761.03
    .041    .041
Vertical n for Station=3802.11
     .12     .24
Vertical n for Station=4886.36
     .07      .1
Vertical n for Station=5007.72
     .12     .24
Vertical n for Station=5258.28
     .07      .1
Vertical n for Station=5628.47
     .15     .15
Vertical n for Station=7810.57
     .07      .1
Vertical n Flow= 0
Exp/Cntr=.3,.1

Type RM Length L Ch R = 1 ,103035.3,515,680.64,124.1
XS GIS Cut Line= 6
      3183790.87    13762755.985     3180886.081    13761823.936
     3180496.444    13761785.642      3180251.18    13761710.639
     3179370.979    13761060.602     3177018.438    13759564.245
#Sta/Elev= 30
       0   28.52  820.49   27.82 1604.59   27.58 1645.32   19.04 1822.74   19.04
 1893.54   24.92 1978.95   19.04 2211.27   27.25 2710.46   20.41 2722.39   25.57
 2937.88   26.94 3394.93   15.72 3583.76    8.12 3605.11     .22 3633.21   -4.71
 3657.12    4.29 3685.27    6.38 3785.25    5.72 3878.86   17.33 4000.74   18.76
 4205.49   11.45 4486.31   18.23 4792.86   20.47  5150.5   22.31  5237.8    22.4
  5533.5   23.01 5922.57   26.27 6004.41   25.86 6343.86   25.29 7580.97   27.26
#Mann= 15 ,-1 , 0
       0     .07       0  820.49     .15       0 3394.93     .12       0
 3605.11    .071       0 3657.12     .12       0 3785.25     .07       0
 4000.74     .12       0 4486.31     .07       0 4792.86     .12       0
  5150.5     .07       0  5237.8     .12       0  5533.5     .07       0
 5922.57     .15       0 6004.41     .07       0 6343.86     .15       0
#Block Obstruct= 2 ,-1
  912.52 1904.03   24.86 5626.93 5795.14   24.65
Bank Sta=3583.76,3685.27
XS Rating Curve= 0
Vertical n Elevations= 2
      13      20
Vertical n for Station=0
     .07      .1
Vertical n for Station=820.49
     .15     .15
Vertical n for Station=3394.93
     .12     .24
Vertical n for Station=3605.11
    .041    .041
Vertical n for Station=3657.12
     .12     .24
Vertical n for Station=3785.25
     .07      .1
Vertical n for Station=4000.74
     .12     .24
Vertical n for Station=4486.31
     .07      .1
Vertical n for Station=4792.86
     .12     .12
Vertical n for Station=5150.5
     .07      .1
Vertical n for Station=5237.8
     .12     .24
Vertical n for Station=5533.5
     .07      .1
Vertical n for Station=5922.57
     .15     .15
Vertical n for Station=6004.41
     .07      .1
Vertical n for Station=6343.86
     .15     .15
Vertical n Flow= 0
Exp/Cntr=.3,.1

Type RM Length L Ch R = 1 ,102354.7,388.25,487.99,190.28
XS GIS Cut Line= 5
     3183925.318    13762621.538     3180624.577    13761295.753
     3180478.147    13761432.421     3179509.512    13761003.146
      3177175.16    13759546.831
#Sta/Elev= 30
       0   27.25  1468.1   26.85 1526.13   27.57 1568.21   19.04 1683.63   26.68
 2016.23   22.53 2168.57   28.34 2256.01   22.53  2384.1   27.47  3038.9   26.88
 3098.29   20.41 3160.02   27.78 3516.57   19.82 3578.67   10.18 3622.56   -6.05
 3645.81     .03 3750.01    9.01 3853.43    5.54 3959.56    7.11 3988.96    9.92
 4219.45    6.75 4240.38     .04 4337.67     .04 4479.38    24.2 4514.11   17.59
 4552.72   22.06 5189.35   21.04 5654.63   22.36 6710.41   28.28 7568.21    27.7
#Mann= 12 ,-1 , 0
       0     .07       0  1468.1     .15       0 3516.57     .12       0
 3622.56    .071       0 3645.81     .07       0 3853.43    .042       0
 3959.56     .07       0 3988.96     .12       0 4219.45     .07       0
 5189.35     .12       0 5654.63     .07       0 6710.41     .15       0
#Block Obstruct= 3 ,-1
 1225.99 3146.05   24.71 4079.39 4506.87    10.1 5804.63 6013.15   24.89
Bank Sta=3578.67,3750.01
XS Rating Curve= 0
Vertical n Elevations= 2
      13      20
Vertical n for Station=0
     .07      .1
Vertical n for Station=1468.1
     .15     .15
Vertical n for Station=3516.57
     .12     .24
Vertical n for Station=3622.56
    .041    .041
Vertical n for Station=3645.81
     .07      .1
Vertical n for Station=3853.43
    .042    .042
Vertical n for Station=3959.56
     .07      .1
Vertical n for Station=3988.96
     .12     .24
Vertical n for Station=4219.45
     .07     .07
Vertical n for Station=5189.35
     .12     .24
Vertical n for Station=5654.63
     .07      .1
Vertical n for Station=6710.41
     .15     .15
Vertical n Flow= 0
Exp/Cntr=.3,.1

Type RM Length L Ch R = 1 ,101866.7,466.64,783.75,530.63
XS GIS Cut Line= 5
     3184177.406    13762302.226     3180732.195    13760974.559
     3180258.501    13761015.095     3180108.759     13761135.53
     3177314.469    13759477.177
#Sta/Elev= 30
       0    27.3 1389.11   26.64 1508.09   27.45    1522   19.04 1622.97   27.14
 1958.47   22.53 2051.63   29.58 2195.06   22.53 2373.13   28.24 3307.74   28.33
 3391.72   20.41 3465.76   26.49 3931.78   19.75 3981.96   18.11 4111.37   11.06
 4197.91    4.38 4205.55   -1.75 4239.16   -7.19 4256.14     .26 4276.92    7.19
 4327.18     8.5 4371.24     .04 4582.34     .04  4600.2    6.58 4849.41    24.2
 4887.95   17.59 5314.37   21.46 5424.12   22.68 6787.57   28.28 7609.11   28.38
#Mann= 9 ,-1 , 0
       0     .07       0 1389.11     .15       0 3931.78     .07       0
 3981.96     .12       0 4205.55    .071       0 4256.14     .07       0
 5314.37     .12       0 5424.12     .07       0 6787.57     .15       0
#Block Obstruct= 3 ,-1
 1222.38 3706.08   24.93 4311.45 4726.72    7.91 6008.91 6199.75   24.78
Bank Sta=4111.37,4276.92
XS Rating Curve= 0
Vertical n Elevations= 2
      13      20
Vertical n for Station=0
     .07      .1
Vertical n for Station=1389.11
     .15     .15
Vertical n for Station=3931.78
     .07      .1
Vertical n for Station=3981.96
     .12     .24
Vertical n for Station=4205.55
    .041    .041
Vertical n for Station=4256.14
     .07      .1
Vertical n for Station=5314.37
     .12     .24
Vertical n for Station=5424.12
     .07      .1
Vertical n for Station=6787.57
     .15     .15
Vertical n Flow= 0
Exp/Cntr=.3,.1

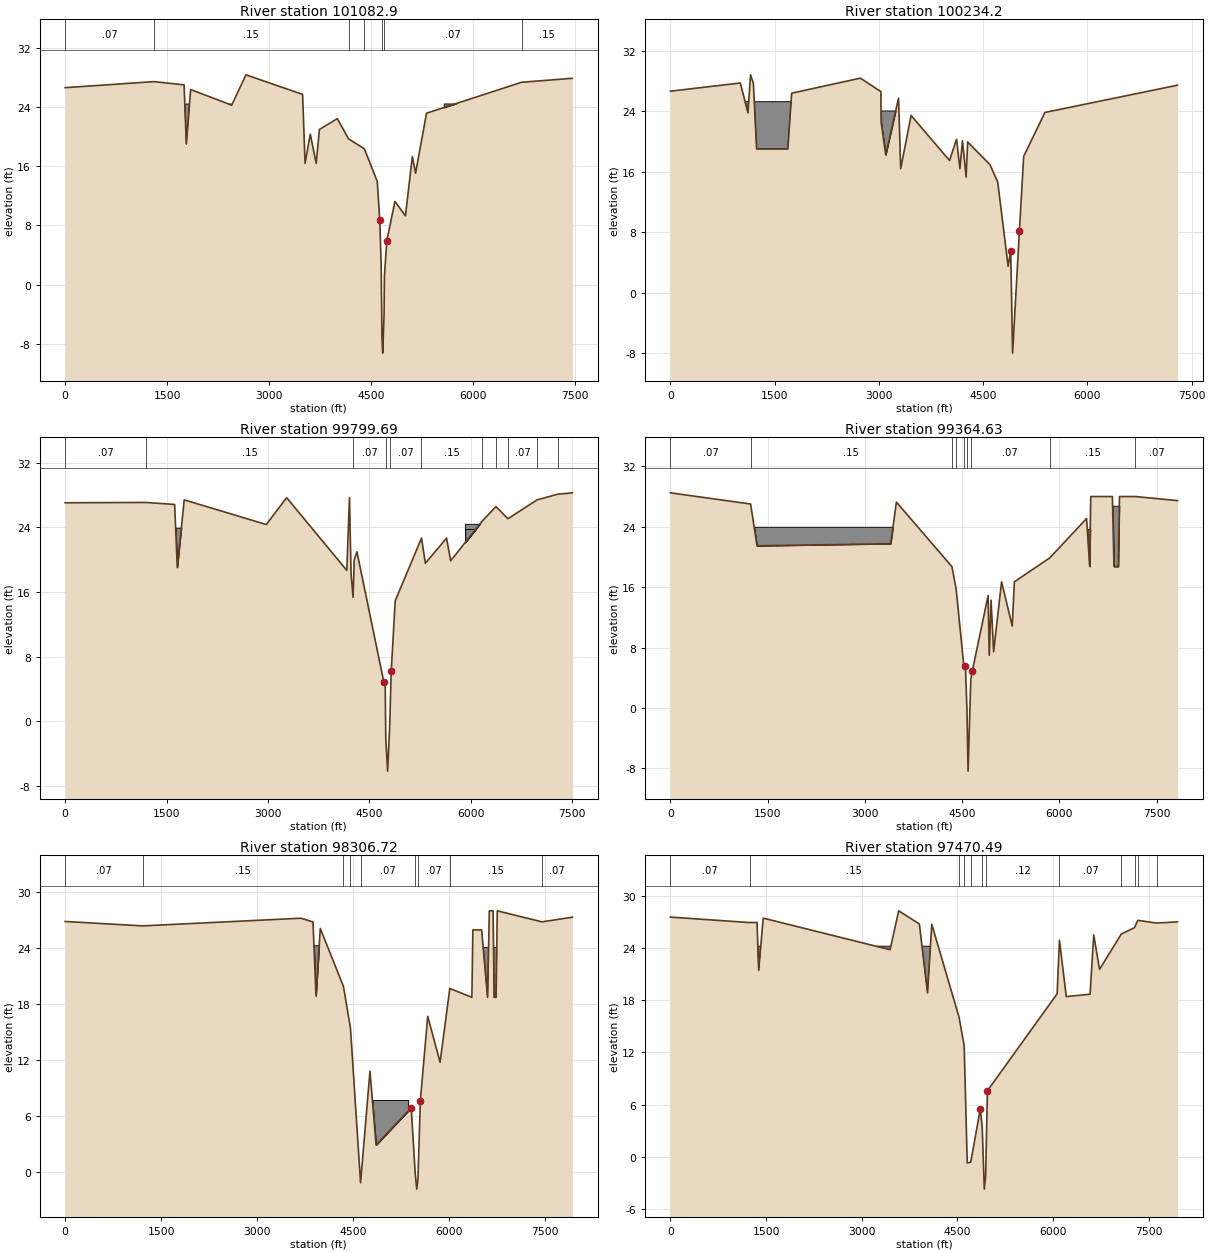
Type RM Length L Ch R = 1 ,101082.9,270.38,848.72,529.91
XS GIS Cut Line= 4
     3184227.824    13762235.002     3180108.759    13760335.577
     3179902.585    13760437.783     3177401.537     13759442.35
#Sta/Elev= 30
       0   26.67 1306.55   27.49 1748.73   27.05 1782.11   19.04 1845.16   26.42
 2449.01    24.3  2659.2   28.41 3491.68   25.76 3527.63   16.42 3604.75   20.37
 3691.09   16.42 3738.92   21.01 4002.16   22.48 4167.34   19.74 4399.46   18.39
 4589.47   13.97 4626.29     8.7 4646.61    2.66 4658.34   -7.07 4669.65   -9.29
 4689.85   -3.92 4694.73    1.14 4729.78    5.95 4849.66   11.26 5003.93     9.3
 5105.06   17.33 5152.55   15.08 5313.99   23.21 6710.65    27.4 7457.89   27.94
#Mann= 7 ,-1 , 0
       0     .07       0 1306.55     .15       0 4167.34     .07       0
 4399.46     .12       0 4658.34    .071       0 4694.73     .07       0
 6710.65     .15       0
#Block Obstruct= 2 ,-1
  1606.2 2927.12   24.45 5567.12 6193.91   24.53
Bank Sta=4626.29,4729.78
XS Rating Curve= 0
Vertical n Elevations= 2
      13      20
Vertical n for Station=0
     .07      .1
Vertical n for Station=1306.55
     .15     .15
Vertical n for Station=4167.34
     .07      .1
Vertical n for Station=4399.46
     .12     .24
Vertical n for Station=4658.34
    .041    .041
Vertical n for Station=4694.73
     .07      .1
Vertical n for Station=6710.65
     .15     .15
Vertical n Flow= 0
Exp/Cntr=.3,.1

Type RM Length L Ch R = 1 ,100234.2,374.35,434.57,314.92
XS GIS Cut Line= 4
     3184261.436    13762100.555     3180002.673    13759984.048
     3179835.859    13759810.561     3177572.684    13759394.803
#Sta/Elev= 30
       0   26.68 1006.27   27.77 1116.15   23.83 1153.84   28.85  1194.2   27.73
 1241.22   19.04 1689.87   19.04 1745.31   26.42 2734.12   28.41 3028.72   26.63
 3032.43   22.58  3098.7   18.26 3282.84   25.76 3313.93   16.42 3463.42   23.47
 4016.98   17.51 4117.82   20.33 4166.07   16.42 4203.05   20.13 4254.99   15.33
 4277.43   19.96 4598.48   16.96 4710.15   14.64 4859.74     3.5 4896.89    5.57
 4923.99   -7.99 5021.53    8.12 5083.61   18.06 5389.35   23.87 7297.42   27.48
#Mann= 0 ,-1 , 0
#Block Obstruct= 2 ,-1
     900 1807.63   25.29 2636.16 3251.29   24.13
Bank Sta=4896.89,5021.53
XS Rating Curve= 0
Vertical n Elevations= 2
      13      20
Vertical n for Station=0
     .07      .1
Vertical n for Station=1227.66
     .15     .15
Vertical n for Station=4107.59
     .07      .1
Vertical n for Station=4431.15
     .12     .24
Vertical n for Station=4912.99
    .041    .041
Vertical n for Station=4963.23
     .07      .1
Vertical n for Station=5125.78
     .15     .15
Vertical n for Station=5432.3
     .07      .1
Vertical n for Station=6737.31
     .15     .15
Vertical n Flow= 0
Exp/Cntr=.3,.1

Type RM Length L Ch R = 1 ,99799.69,368.76,435.06,383.61
XS GIS Cut Line= 4
     3184345.465    13762033.331       3180409.7    13759750.508
     3180136.125    13759543.659     3177555.169    13759175.398
#Sta/Elev= 30
       0   27.03 1193.56   27.07 1619.22   26.82 1658.27   19.04 1760.82   27.39
 2974.13   24.34 3275.57   27.66 4165.06   18.67 4204.13   27.66 4227.94   18.26
 4257.85   15.33 4274.48   19.96 4314.48   20.98 4713.18    4.84 4732.89    4.24
  4740.9      -2 4768.13   -6.14 4798.67    -.77  4821.8    6.23 4880.69    14.9
 5269.32   22.66  5326.8   19.56 5639.96   22.66 5700.74   19.86 6168.21   24.77
 6370.23   26.56 6547.48   25.06 6976.31   27.38 7281.56   28.09 7499.96   28.26
#Mann= 11 ,-1 , 0
       0     .07       0 1193.56     .15       0 4257.85     .07       0
  4740.9    .071       0 4798.67     .07       0 5269.32     .15       0
 6168.21     .07       0 6370.23     .15       0 6547.48     .07       0
 6976.31     .15       0 7281.56     .07       0
#Block Obstruct= 3 ,-1
 1487.72 3602.76   23.95 5912.91 6250.01   24.43 5916.03 6244.51   23.79
Bank Sta=4713.18,4821.8
XS Rating Curve= 0
Vertical n Elevations= 2
      13      20
Vertical n for Station=0
     .07      .1
Vertical n for Station=1193.56
     .15     .15
Vertical n for Station=4257.85
     .07      .1
Vertical n for Station=4740.9
    .041    .041
Vertical n for Station=4798.67
     .07      .1
Vertical n for Station=5269.32
     .15     .15
Vertical n for Station=6168.21
     .07      .1
Vertical n for Station=6370.23
     .15     .15
Vertical n for Station=6547.48
     .07      .1
Vertical n for Station=6976.31
     .15     .15
Vertical n for Station=7281.56
     .07      .1
Vertical n Flow= 0
Exp/Cntr=.3,.1

Type RM Length L Ch R = 1 ,99364.63,145.95,1057.91,330.9
XS GIS Cut Line= 5
     3184446.301    13761949.301     3180696.621    13759476.933
     3180549.824    13759370.172     3179104.968     13759036.61
     3177453.777    13758815.461
#Sta/Elev= 30
       0   28.46 1237.69   26.98 1336.43   21.45 3397.71   21.73 3485.89   27.23
 4342.09    18.7 4408.25   15.66 4526.79    5.47 4550.16    5.56 4573.76    -.23
 4591.13   -8.35 4632.91    3.74 4655.49    4.86 4900.33   14.88 4917.54    6.98
 4945.78   14.26 4984.98    7.45 5107.89   16.69 5271.86   10.84 5305.17   16.69
 5851.59   19.86 6418.31   25.06 6466.62   18.72 6482.98   27.97 6816.96   27.97
 6841.28   18.72 6908.37   18.72 6926.03   27.97 7168.05   27.97 7821.71   27.43
#Mann= 9 ,-1 , 0
       0     .07       0 1237.69     .15       0 4342.09     .07       0
 4408.25     .12       0 4526.79     .07       0 4573.76    .071       0
 4632.91     .07       0 5851.59     .15       0 7168.05     .07       0
#Block Obstruct= 3 ,-1
 1133.99 3486.49   23.97  6336.5 6699.05   23.68 6766.41 6949.62   26.75
Bank Sta=4550.16,4655.49
XS Rating Curve= 0
Vertical n Elevations= 2
      13      20
Vertical n for Station=0
     .07      .1
Vertical n for Station=1237.69
     .15     .15
Vertical n for Station=4342.09
     .07      .1
Vertical n for Station=4408.25
     .12     .24
Vertical n for Station=4526.79
     .07      .1
Vertical n for Station=4573.76
    .041    .041
Vertical n for Station=4632.91
     .07      .1
Vertical n for Station=5851.59
     .15     .15
Vertical n for Station=7168.05
     .07      .1
Vertical n Flow= 0
Exp/Cntr=.3,.1

Type RM Length L Ch R = 1 ,98306.72,211.11,836.24,692.61
XS GIS Cut Line= 6
     3184513.524    13761882.078     3180803.382    13759370.172
     3180609.877    13759169.995     3180056.054    13759089.924
     3179849.204    13758909.765     3177589.866    13758319.539
#Sta/Elev= 30
       0   26.83 1211.78   26.36 3686.19   27.18 3874.15   26.78 3921.21   18.87
  3988.1   26.08 4350.39   19.88 4459.68   15.44 4617.64   -1.11 4764.75   10.83
 4860.57    2.92 5409.63     6.9 5471.95    -.13 5495.66   -1.79 5514.82     -.7
 5552.21    7.67 5667.27   16.69  5860.8   11.78 6012.45   19.67 6357.66   18.72
 6372.91   25.93 6510.43   25.93 6603.26   18.72 6630.32   27.97 6689.33   27.97
 6705.64   18.72 6736.08   18.72 6754.33   27.97 7454.35   26.79 7927.95   27.29
#Mann= 9 ,-1 , 0
       0     .07       0 1211.78     .15       0 4350.39     .07       0
 4459.68    .042       0 4617.64     .07       0 5471.95    .071       0
 5514.82     .07       0 6012.45     .15       0 7454.35     .07       0
#Block Obstruct= 3 ,-1
 1046.64 4059.16   24.29 4763.36 5361.83    7.74 6505.91 6822.99   24.04
Bank Sta=5409.63,5552.21
XS Rating Curve= 0
Vertical n Elevations= 2
      13      20
Vertical n for Station=0
     .07      .1
Vertical n for Station=1211.78
     .15     .15
Vertical n for Station=4350.39
     .07      .1
Vertical n for Station=4459.68
    .042    .042
Vertical n for Station=4617.64
     .07      .1
Vertical n for Station=5471.95
    .041    .041
Vertical n for Station=5514.82
     .07      .1
Vertical n for Station=6012.45
     .15     .15
Vertical n for Station=7454.35
     .07      .1
Vertical n Flow= 0
Exp/Cntr=.3,.1

Type RM Length L Ch R = 1 ,97470.49,295.33,290.24,197.63
XS GIS Cut Line= 6
     3184645.441    13761851.598     3180976.868    13759230.048
     3180666.065    13759070.012     3180723.311    13758983.163
     3179845.171    13758400.498      3177969.27    13757927.891
#Sta/Elev= 30
       0   27.57 1241.07   26.94 1358.51   26.95 1384.37   21.45 1455.57   27.45
 3444.35   23.82 3579.48   28.29 3903.47   26.78 4031.36   18.87 4098.16   26.74
 4525.14   16.07 4605.97   12.77 4653.86     -.7 4708.73    -.61 4858.57    5.49
 4888.39    3.43 4921.46   -3.71 4942.58   -2.17  4970.3     7.6 6063.21   18.75
 6099.59    24.9 6206.26   18.43 6579.62    18.7 6636.82   25.52 6727.86   21.56
 7069.97   25.63 7276.22   26.36 7327.78    27.2 7621.26   26.88 7950.97   27.02
#Mann= 12 ,-1 , 0
       0     .07       0 1241.07     .15       0 4525.14     .07       0
 4605.97    .042       0 4708.73     .07       0 4888.39    .071       0
 4942.58     .12       0 6099.59     .07       0 7069.97     .15       0
 7276.22     .07       0 7327.78     .15       0 7621.26     .07       0
#Block Obstruct= 1 ,-1
 1019.34 4141.07   24.22
Bank Sta=4858.57,4970.3
XS Rating Curve= 0
Vertical n Elevations= 2
      12      19
Vertical n for Station=0
     .07      .1
Vertical n for Station=1241.07
     .15     .15
Vertical n for Station=4525.14
     .07      .1
Vertical n for Station=4605.97
    .042    .042
Vertical n for Station=4708.73
     .07      .1
Vertical n for Station=4888.39
    .041    .041
Vertical n for Station=4942.58
     .12     .24
Vertical n for Station=6099.59
     .07      .1
Vertical n for Station=7069.97
     .15     .15
Vertical n for Station=7276.22
     .07      .1
Vertical n for Station=7327.78
     .15     .15
Vertical n for Station=7621.26
     .07      .1
Vertical n Flow= 0
Exp/Cntr=.3,.1

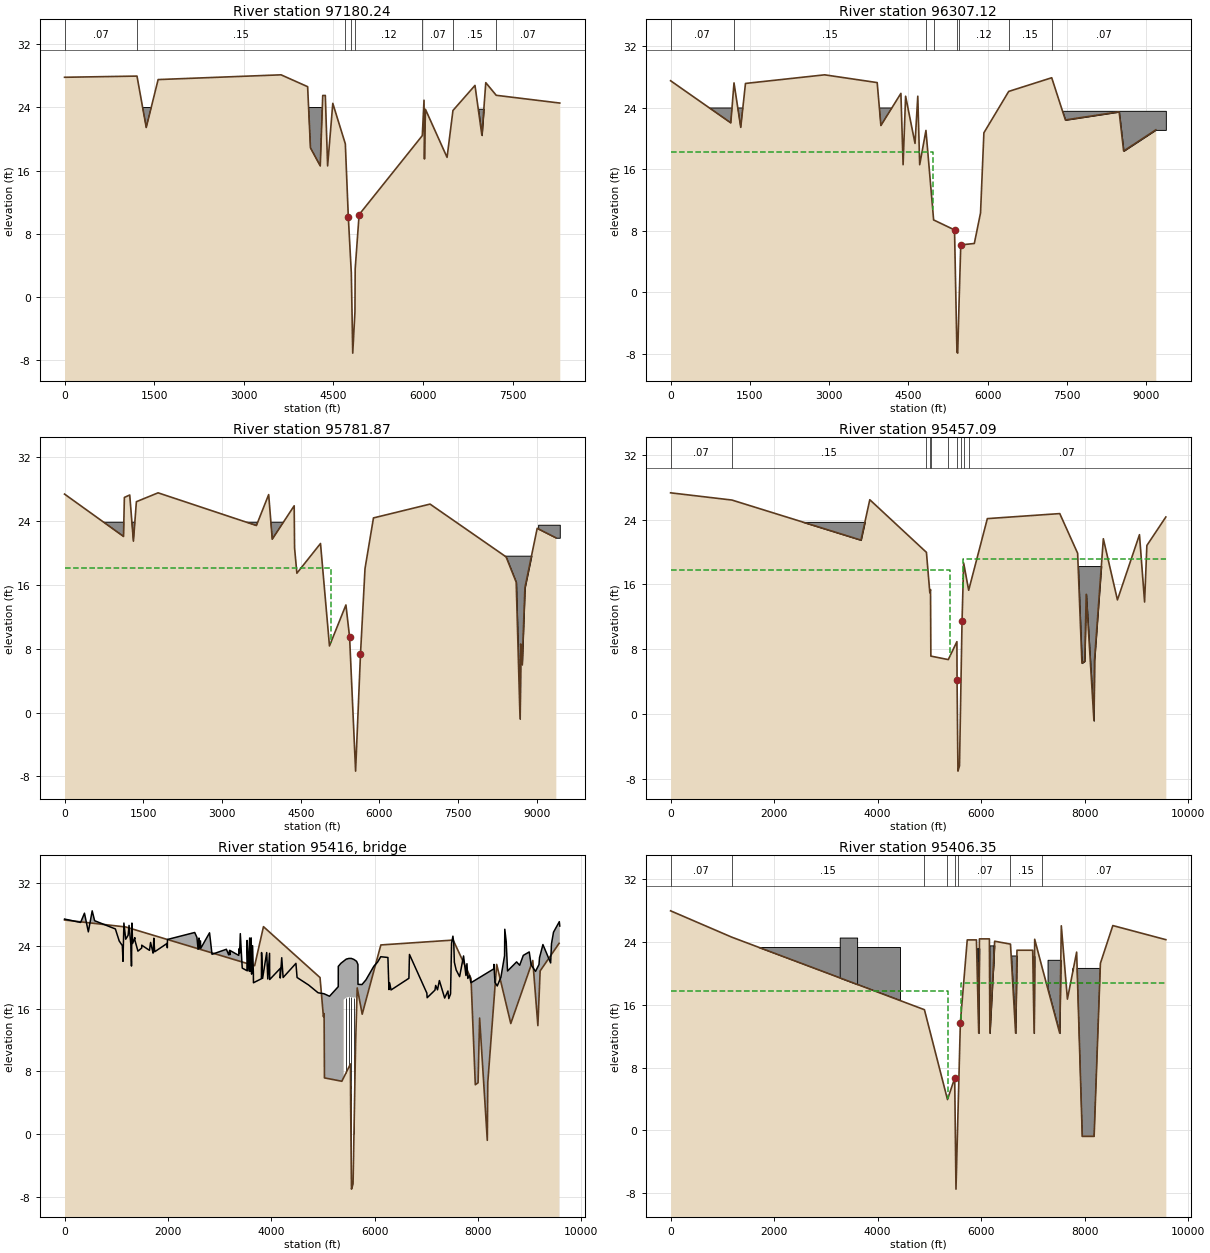
Type RM Length L Ch R = 1 ,97180.24,534.37,873.12,495.86
XS GIS Cut Line= 5
     3184696.268    13761800.771     3181023.576     13758923.11
     3180765.549    13758914.249     3180064.919    13758319.539
     3177824.258     13757333.14
#Sta/Elev= 30
       0    27.8 1212.88   27.95 1367.57   21.45 1566.73   27.51 3624.71   28.11
 4069.71   26.61  4117.2   18.87 4280.93   16.59 4322.59    25.5 4365.69    25.5
 4404.17   16.59 4491.06    24.5 4700.78   19.38 4751.04   10.09 4800.97    3.08
 4824.83   -7.09 4861.82   -1.87 4865.81    3.55 4931.53   10.43 5989.38   20.42
 6018.25    24.9 6025.66   17.47 6042.05   23.75 6404.07   17.67 6502.69    23.6
 6871.49   26.77 6987.14   20.46 7052.31   27.12  7227.3   25.52 8291.14   24.54
#Mann= 8 ,-1 , 0
       0     .07       0 1212.88     .15       0 4700.78     .07       0
 4800.97    .071       0 4861.82     .12       0 5989.38     .07       0
 6502.69     .15       0  7227.3     .07       0
#Block Obstruct= 2 ,-1
  898.75 4345.85   23.97 6907.13 8411.32   23.82
Bank Sta=4751.04,4931.53
XS Rating Curve= 0
Vertical n Elevations= 2
      12      19
Vertical n for Station=0
     .07      .1
Vertical n for Station=1212.88
     .15     .15
Vertical n for Station=4700.78
     .07      .1
Vertical n for Station=4800.97
    .041    .041
Vertical n for Station=4861.82
     .12     .24
Vertical n for Station=5989.38
     .07      .1
Vertical n for Station=6502.69
     .15     .15
Vertical n for Station=7227.3
     .07      .1
Vertical n Flow= 0
Exp/Cntr=.5,.3

Type RM Length L Ch R = 1 ,96307.12,129.18,525.25,425.13
XS GIS Cut Line= 5
     3184718.505    13761749.944     3180818.416    13758055.796
     3180703.293    13758182.455     3180296.232    13757926.306
     3177457.832    13756547.942
#Sta/Elev= 30
       0   27.51 1138.84   22.03 1199.69   27.23 1326.92   21.45 1416.66   27.16
 2914.78   28.28 3908.58   27.27 3978.59   21.69 4357.29   25.87 4398.74   16.59
 4446.02    25.5  4624.4   19.36 4676.54    25.5 4712.55   16.59 4831.01   21.05
 4976.39    9.41 5371.67    8.11 5417.62   -7.79 5431.94   -7.91  5458.6   -1.09
 5489.85    6.16 5746.26    6.35 5863.83   10.32 5927.36   20.74 6396.56   26.12
 7210.45    27.9 7469.16   22.41  8486.3   23.47 8571.21   18.37  9179.4   21.12
#Mann= 8 ,-1 , 0
       0     .07       0 1199.69     .15       0 4831.01     .07       0
 4976.39     .12       0 5417.62    .071       0  5458.6     .12       0
 6396.56     .15       0 7210.45     .07       0
#XS Ineff= 2 ,-1
       0 4960.36   18.18 6660.11  9179.4   19.38
Permanent Ineff=
       F       F
#Block Obstruct= 2 ,-1
  295.79 4323.09   23.97 6593.72 9369.46    23.6
Bank Sta=5371.67,5489.85
XS Rating Curve= 0
Vertical n Elevations= 2
      12      19
Vertical n for Station=0
     .07      .1
Vertical n for Station=1199.69
     .15     .15
Vertical n for Station=4831.01
     .07      .1
Vertical n for Station=4976.39
     .12     .24
Vertical n for Station=5417.62
    .041    .041
Vertical n for Station=5458.6
     .12     .24
Vertical n for Station=6396.56
     .15     .15
Vertical n for Station=7210.45
     .07      .1
Vertical n Flow= 0
Exp/Cntr=.5,.3

Type RM Length L Ch R = 1 ,95781.87,273.41,324.77,365.57
XS GIS Cut Line= 4
     3184731.211    13761721.354     3180896.798     13757935.57
     3180756.674    13757742.065     3177695.987    13755604.989
#Sta/Elev= 30
       0   27.33 1123.71   22.03 1139.67   26.91 1241.84   27.22 1312.01   21.45
 1368.52   26.38 1782.17   27.49 3655.16    23.4 3888.97   27.27 3957.34   21.69
 4374.97   25.87 4382.34   20.59 4426.48   17.43 4876.44   21.15 5047.42    8.33
 5360.59   13.46  5430.7    9.44 5544.98   -7.33 5638.06    7.28  5724.4   18.01
 5885.74   24.35  6963.5   26.08 8411.88   19.48 8604.62   16.31 8678.23    -.79
 8690.26    8.58 8717.67    5.99 8770.93   15.61 9004.88   23.05 9360.27   21.87
#Mann= 0 ,-1 , 0
#XS Ineff= 2 ,-1
       0 5071.21   18.07 5902.68 9360.27   19.28
Permanent Ineff=
       F       F
#Block Obstruct= 3 ,-1
  693.97  4368.6   23.81 8335.88  9022.9   19.63 9022.83 9435.13    23.5
Bank Sta=5430.7,5638.06
XS Rating Curve= 0
Vertical n Elevations= 2
      12      19
Vertical n for Station=0
     .07      .1
Vertical n for Station=1171.57
     .15     .15
Vertical n for Station=4876.44
     .07      .1
Vertical n for Station=4935.53
     .12     .24
Vertical n for Station=5514.94
    .041    .041
Vertical n for Station=5595.16
     .12     .24
Vertical n for Station=5740.31
     .07      .1
Vertical n Flow= 0
Exp/Cntr=.5,.3

Type RM Length L Ch R = 1 ,95457.09,100.96,50.74,140.32
XS GIS Cut Line= 6
     3184778.862    13761718.177     3181658.585    13758286.575
     3181199.939    13757909.939     3181018.243    13757538.156
     3179984.729    13756339.436      3177986.35    13755143.825
#Sta/Elev= 30
       0    27.3 1184.88   26.41 3678.42   21.47 3849.12   26.45  4943.7   19.96
 5008.94   14.98 5022.32   15.37 5029.02    7.17 5365.86    6.74 5532.36    8.95
 5535.39    4.19 5552.32   -7.01 5582.52   -6.36 5631.48   11.45 5662.96   18.64
 5759.83   15.29 6120.55   24.12 7519.91   24.74 7865.18   19.85 7948.15     6.3
 8001.85    6.55 8031.53    14.8 8180.31    -.79  8190.2     6.6 8361.96   21.64
 8634.45    14.1 9060.07   22.14 9158.94   13.84 9203.08   20.81 9569.41   24.32
#Mann= 10 ,-1 , 0
       0     .07       0 1184.88     .15       0  4943.7     .07       0
 5008.94     .07       0 5022.32     .12       0 5365.86     .07       0
 5532.36    .071       0 5603.75     .07       0 5662.96     .12       0
 5759.83     .07       0
#XS Ineff= 2 ,-1
       0 5401.17    17.8 5649.68 9569.41    19.2
Permanent Ineff=
       F       F
#Block Obstruct= 2 ,-1
     876 3993.17   23.72 7664.12 8366.41   18.27
Bank Sta=5535.39,5631.48
XS Rating Curve= 0
Vertical n Elevations= 2
      12      19
Vertical n for Station=0
     .07      .1
Vertical n for Station=1184.88
     .15     .15
Vertical n for Station=4943.7
     .07      .1
Vertical n for Station=5008.94
     .07      .1
Vertical n for Station=5022.32
     .12     .24
Vertical n for Station=5365.86
     .07      .1
Vertical n for Station=5532.36
    .041    .041
Vertical n for Station=5610.58
     .07      .1
Vertical n for Station=5662.96
     .12     .24
Vertical n for Station=5759.83
     .07      .1
Vertical n Flow= 0
Exp/Cntr=.5,.3

Type RM Length L Ch R = 3 ,95416   ,,,
BEGIN DESCRIPTION:
Whispering Pines
END DESCRIPTION:
Bridge Culvert--1,0,-1,-1, 0
Deck Dist Width WeirC Skew NumUp NumDn MinLoCord MaxHiCord MaxSubmerge Is_Ogee
5,41,2.6,0, 149, 149, , , .95, 0, 0,0,,
       0  310.57  385.31  460.05  534.79     582  983.24 1057.98 1118.18  1130.7
 1148.42 1183.87 1229.91 1247.76  1283.9  1294.8 1295.83 1303.75    1317 1360.34
 1360.95 1419.84 1493.27  1493.6 1643.44 1664.47 1713.03 1714.26 1715.78 1727.19
 1743.84 1985.66 1988.69 1991.51 2518.51 2561.62  2583.9 2600.79 2603.03 2630.27
 2634.39 2805.65 2853.55 3131.57 3176.27 3194.29 3200.33  3202.7 3370.16 3381.12
 3387.56 3401.06 3438.17 3529.84 3532.37 3551.08 3582.12 3589.12  3611.6 3619.72
 3638.48  3654.2 3655.23 3809.27 3812.36 3831.84 3911.64  3932.6 3966.95 3969.71
 4173.68 4173.93 4202.43 4229.26 4477.22 4499.14 4723.29    4906    5021    5127
    5296    5297    5349    5400    5401    5450    5501    5550    5600    5650
    5651    5677    5678    5755    5830    5985    6055    6119 6257.05 6276.79
 6290.59 6317.57 6663.46 6674.09 7010.55 7016.24 7167.49 7181.55 7216.42 7253.19
 7355.11 7418.71 7434.41 7469.06 7488.84 7514.95  7530.9 7542.94 7578.29 7644.39
 7720.74 7766.82 7786.36 7803.16 7836.39 7863.49 8307.42 8308.08 8328.81 8372.51
 8443.51 8514.18 8518.69 8546.25 8571.95 8746.96 8806.53 8876.75 8991.74 9027.85
 9112.65 9180.37 9190.69 9256.55 9405.62 9422.33 9461.53 9574.05 9582.79
   27.42   26.99   28.17   25.79   28.47   27.21   26.16   24.62   24.03   22.03
   26.91   24.85   25.35   26.61   24.14   21.43   21.79   26.91   24.31   25.05
   24.73   23.33   23.73   24.09   23.43   24.44   23.08    23.6   23.21   24.98
   23.25   24.32   23.76   24.82   25.71   25.08   23.57      25    23.7   24.64
   23.68   25.67   22.93   23.57   22.86   23.43   22.88   23.41   22.79   23.67
   23.06   25.56   21.17   20.84   24.69   20.81   25.01   20.74   25.02    20.4
   24.02   20.36    19.3   19.81   23.15   19.85   23.15   19.78   23.05   19.71
   21.13    19.9   22.49   19.97   21.77   19.97   19.01   18.02    17.9   17.58
    18.8   21.39   21.79   22.06   22.06   22.31    22.4    22.4   22.27   22.03
   22.03   21.63    19.1   19.07   19.65   21.41   21.91   22.62   22.52   18.43
   19.29   18.38   19.87   22.91   17.98   17.39   18.36   18.96    18.4   19.58
   17.35   18.25   17.28   17.87   24.35   25.24   24.39   21.91   20.92   20.08
   22.72   20.23   21.73   19.85   20.23    19.3   21.08   21.64   19.34   18.89
      20   22.75   26.12   24.54    20.8   21.96   21.53   22.79   23.23   21.59
   20.75   21.62   22.49   24.17   21.83   24.28   25.75   27.09   26.53
                                                                                
                                                                                
                                                                                
                                                                                
                                                                                
                                                                                
                                                                                
                                                                                
                                   17.15    17.4    17.5   17.48    17.4    17.4
                                                                                
                                                                                
                                                                                
                                                                                
                                                                                
                                                                        
       0  260.57  335.31  410.05  484.79     532  933.24 1007.98 1068.18  1080.7
 1098.42 1133.87 1179.91 1197.76  1233.9  1244.8 1245.83 1253.75    1267 1310.34
 1310.95 1369.84 1443.27  1443.6 1593.44 1614.47 1663.03 1664.26 1665.78 1677.19
 1693.84 1935.66 1938.69 1941.51 2468.51 2511.62  2533.9 2550.79 2553.03 2580.27
 2584.39 2755.65 2803.55 3081.57 3126.27 3144.29 3150.33  3152.7 3320.16 3331.12
 3337.56 3351.06 3388.17 3479.84 3482.37 3501.08 3532.12 3539.12  3561.6 3569.72
 3588.48  3604.2 3605.23 3759.27 3762.36 3781.84 3861.64  3882.6 3916.95 3919.71
 4123.68 4123.93 4152.43 4179.26 4427.22 4449.14 4673.29    4856    4971    5077
    5246    5247    5299    5350    5351    5400    5451    5500    5550    5600
    5601    5627    5628    5705    5780    5935    6005    6069 6207.05 6226.79
 6240.59 6267.57 6613.46 6624.09 6960.55 6966.24 7117.49 7131.55 7166.42 7203.19
 7305.11 7368.71 7384.41 7419.06 7438.84 7464.95  7480.9 7492.94 7528.29 7594.39
 7670.74 7716.82 7736.36 7753.16 7786.39 7813.49 8257.42 8258.08 8278.81 8322.51
 8393.51 8464.18 8468.69 8496.25 8521.95 8696.96 8756.53 8826.75 8941.74 8977.85
 9062.65 9130.37 9140.69 9206.55 9355.62 9372.33 9411.53 9524.05 9532.79
   27.42   26.99   28.17   25.79   28.47   27.21   26.16   24.62   24.03   22.03
   26.91   24.85   25.35   26.61   24.14   21.43   21.79   26.91   24.31   25.05
   24.73   23.33   23.73   24.09   23.43   24.44   23.08    23.6   23.21   24.98
   23.25   24.32   23.76   24.82   25.71   25.08   23.57      25    23.7   24.64
   23.68   25.67   22.93   23.57   22.86   23.43   22.88   23.41   22.79   23.67
   23.06   25.56   21.17   20.84   24.69   20.81   25.01   20.74   25.02    20.4
   24.02   20.36    19.3   19.81   23.15   19.85   23.15   19.78   23.05   19.71
   21.13    19.9   22.49   19.97   21.77   19.97   19.01   18.02    17.9   17.58
    18.8   21.39   21.79   22.06   22.06   22.31    22.4    22.4   22.27   22.03
   22.03   21.63    19.1   19.07   19.65   21.41   21.91   22.62   22.52   18.43
   19.29   18.38   19.87   22.91   17.98   17.39   18.36   18.96    18.4   19.58
   17.35   18.25   17.28   17.87   24.35   25.24   24.39   21.91   20.92   20.08
   22.72   20.23   21.73   19.85   20.23    19.3   21.08   21.64   19.34   18.89
      20   22.75   26.12   24.54    20.8   21.96   21.53   22.79   23.23   21.59
   20.75   21.62   22.49   24.17   21.83   24.28   25.75   27.09   26.53
                                                                                
                                                                                
                                                                                
                                                                                
                                                                                
                                                                                
                                                                                
                                                                                
                                   17.15    17.4    17.5   17.48    17.4    17.4
                                                                                
                                                                                
                                                                                
                                                                                
                                                                                
                                                                        
Pier Skew, UpSta & Num, DnSta & Num=  ,5450, 2 ,5400, 2 , 0 , 0 , 0 ,,
    1.33    1.33
     -30      19
    1.33    1.33
     -30      19
Pier Skew, UpSta & Num, DnSta & Num=  ,5501, 2 ,5451, 2 , 0 , 0 , 0 ,,
    1.33    1.33
       0      19
    1.33    1.33
       0      19
Pier Skew, UpSta & Num, DnSta & Num=  ,5550, 2 ,5500, 2 , 0 , 0 , 0 ,,
    1.33    1.33
       0      19
    1.33    1.33
       0      19
Pier Skew, UpSta & Num, DnSta & Num=  ,5600, 2 ,5550, 2 , 0 , 0 , 0 ,,
    1.33    1.33
       0      19
    1.33    1.33
       0      19
Abutment Skew #Up #Dn= , 2 , 2
    5401    5436
      17       3
    5351    5386
      17       3
BR Coef=-1 , 1 , 1 ,1.25, 0 ,,,.8,-1,2,0,
WSPro=,,,, 1 ,,,, 0 ,,,, 0 ,,,,-1 ,-1 ,-1 , 0 , 0 , 0 , 0 , 0
BC Design=,, 0 ,, 0 ,,,,,,
BC HTab HWMax=28.5

Type RM Length L Ch R = 1 ,95406.35,787.08,764.92,246.42
XS GIS Cut Line= 6
     3184836.042    13761632.407     3181863.547    13758337.815
      3181310.69    13757884.311     3180958.298    13757261.765
      3180070.13    13756236.955     3178071.751    13755058.424
#Sta/Elev= 30
       0      28 1181.45   24.64 4903.67   15.38 5349.34    3.91 5488.51    6.65
 5513.22   -7.52 5597.95   13.73 5730.83   24.29 5908.54   24.29 5952.54   12.39
 5966.31   24.42 6158.72   24.42 6168.15   12.39 6260.88   24.12 6566.07   23.75
 6665.37   12.39 6691.48   22.97 6995.16   22.97 7022.56   12.39 7033.91   24.37
  7169.4   20.97 7517.08   12.39 7548.21   26.09 7666.17   16.73 7844.17   22.73
 7953.24    -.79 8182.04    -.79 8303.24    21.3 8543.45   26.12 9567.36   24.32
#Mann= 8 ,-1 , 0
       0     .07       0 1181.45     .15       0 4903.67     .12       0
 5349.34     .07       0 5488.51    .061       0 5555.62     .07       0
 6566.07     .15       0  7169.4     .07       0
#XS Ineff= 2 ,-1
       0 5351.02   17.74 5601.69 9567.36   18.84
Permanent Ineff=
       F       F
#Block Obstruct= 10 ,-1
  671.22 4425.48   23.39 3267.18 3603.05   24.59 5895.61 5947.56   23.22
 5938.93    6000   23.22 6122.14 6244.27   23.59 6231.04 6267.41   23.59
 6580.15 6778.63    22.3 6916.03 7053.44   22.21 7282.44 7572.52   21.75
 7770.99 8305.34   20.65
Bank Sta=5488.51,5597.95
XS Rating Curve= 0
Vertical n Elevations= 2
      12      19
Vertical n for Station=0
     .07      .1
Vertical n for Station=1181.45
     .15     .15
Vertical n for Station=4903.67
     .12     .24
Vertical n for Station=5349.34
     .07      .1
Vertical n for Station=5488.51
    .041    .041
Vertical n for Station=5561.06
     .07      .1
Vertical n for Station=6566.07
     .15     .15
Vertical n for Station=7169.4
     .07      .1
Vertical n Flow= 0
Exp/Cntr=.5,.3