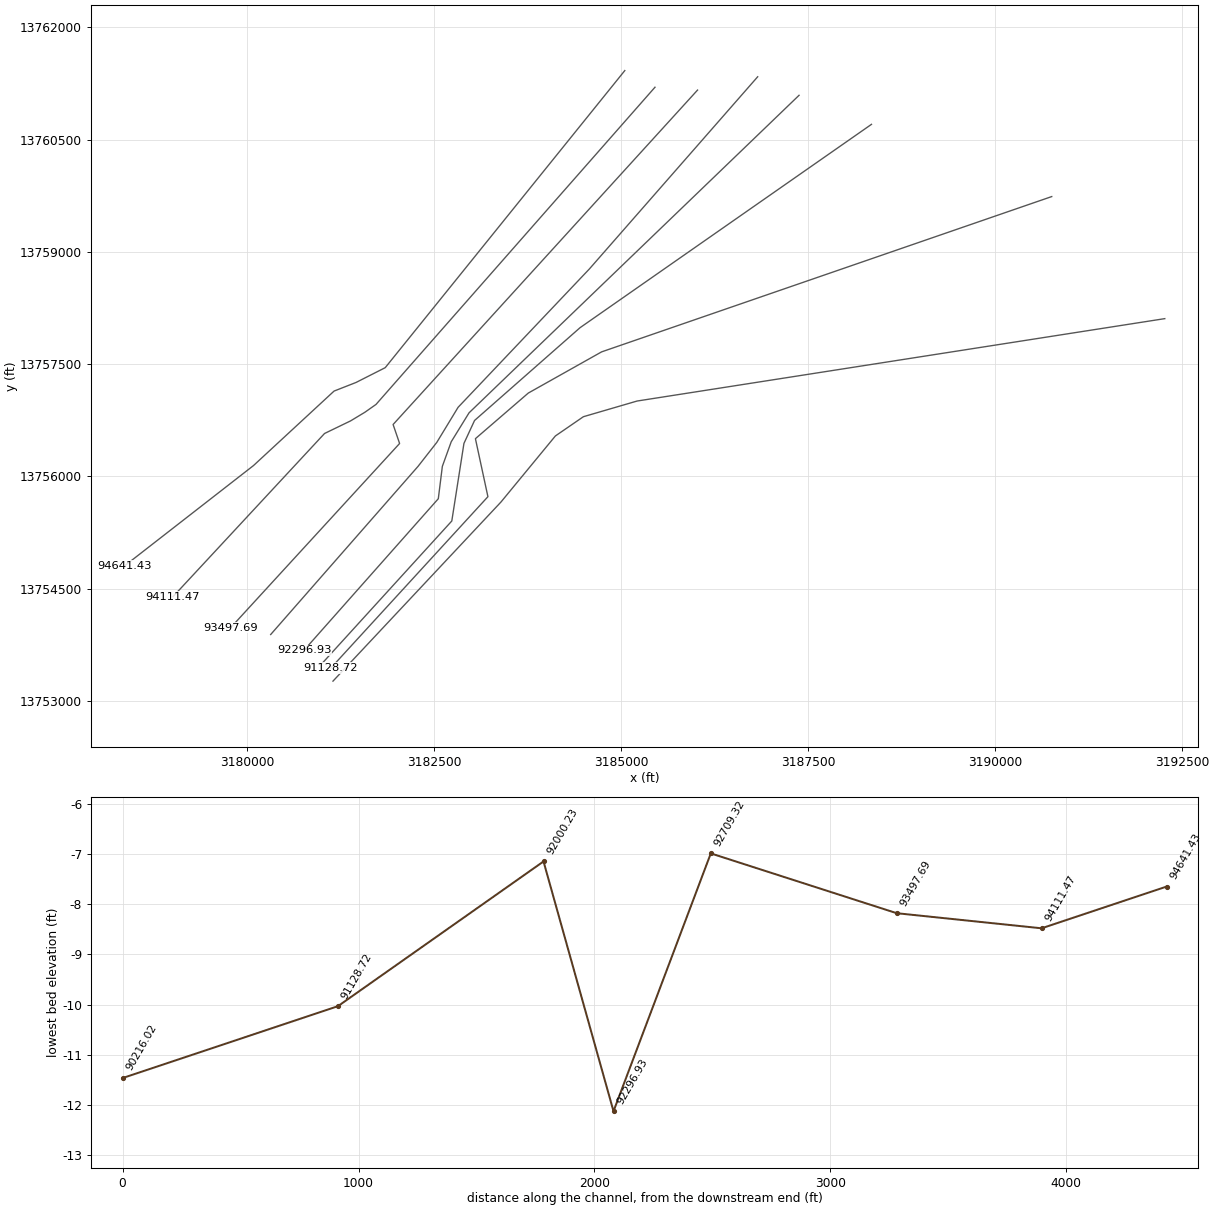
HEC-RAS study A100-00-00.prj: A100-00-00

--- A100-00-00.g01 (geometry) --- (continued)

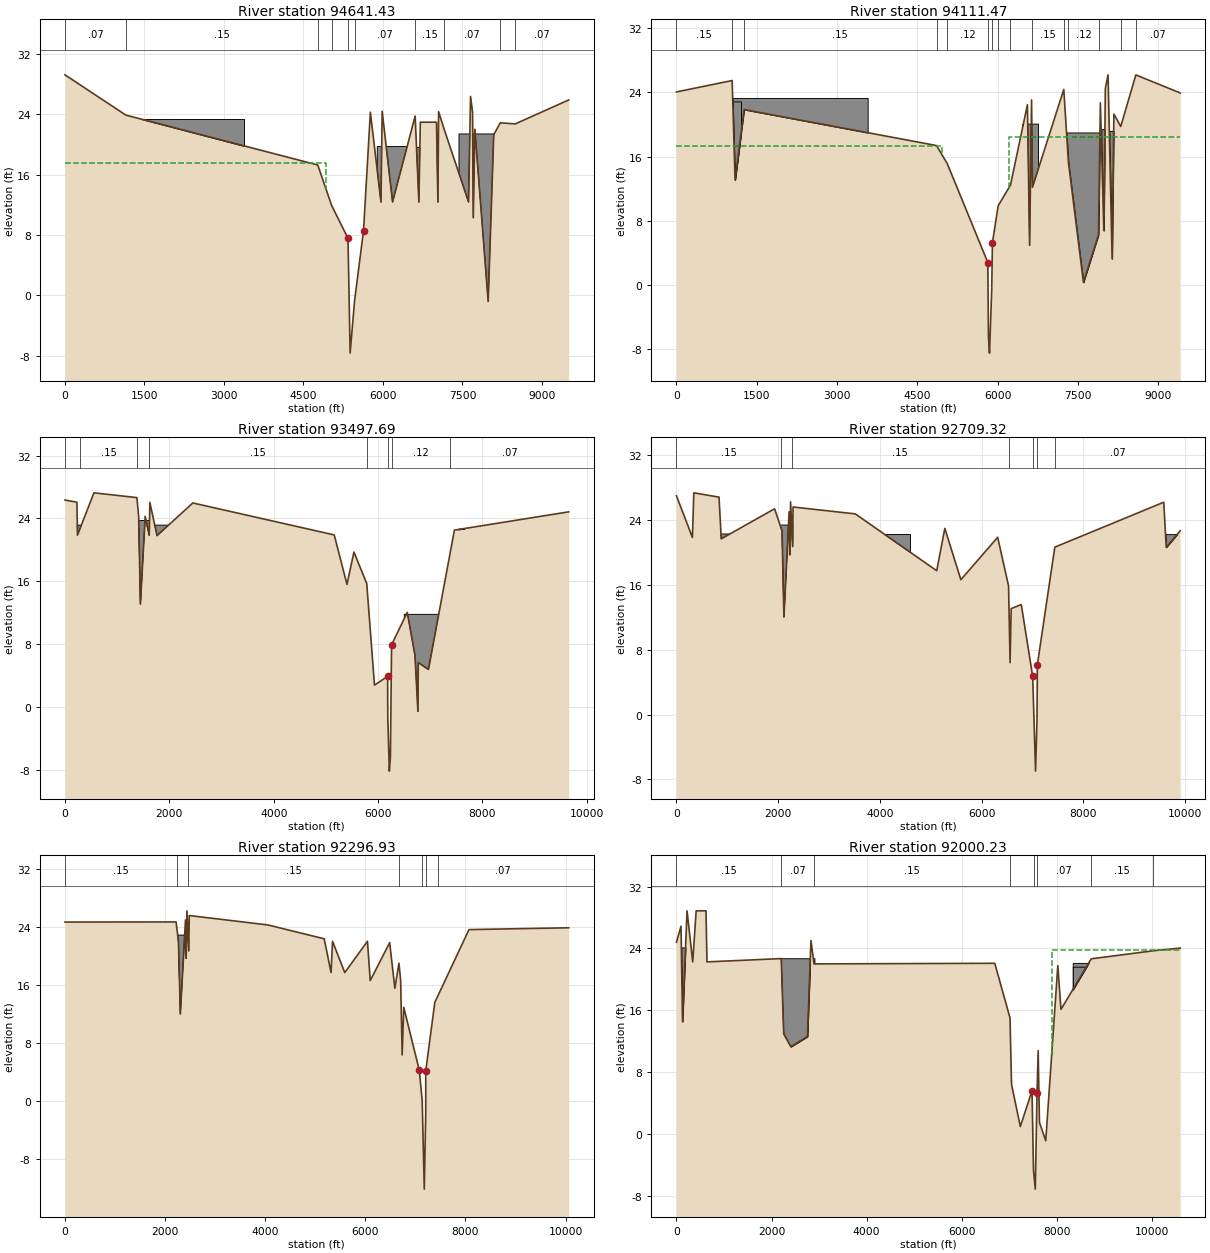
Type RM Length L Ch R = 1 ,94641.43,286.81,529.95,472.2
XS GIS Cut Line= 6
     3185048.879    13761422.747     3181847.561    13757452.777
     3181457.293    13757254.968     3181163.657     13757139.84
     3180086.808    13756144.239     3178362.113    13754802.221
#Sta/Elev= 30
       0   29.25 1148.33   23.91  4770.5   17.29  5031.2   11.94 5334.43    7.66
 5342.45    6.76 5380.83   -7.65 5464.54     -.7 5633.48    8.59 5762.77   24.29
 5962.77   12.39 5984.98   24.42 6181.37   12.39 6607.77   23.79 6678.34   12.39
 6705.13   22.97 7010.44   22.97 7037.17   12.39 7050.28   24.37 7150.97   22.12
 7615.32   12.39 7653.02   26.38 7691.18    24.3 7704.57   10.31 7733.88   22.05
  7985.5    -.79 8090.62    21.3 8214.28   22.89 8495.53   22.74 9505.58   25.92
#Mann= 10 ,-1 , 0
       0     .07       0 1148.33     .15       0  4770.5     .07       0
  5031.2     .12       0 5342.45    .061       0 5464.54     .07       0
 6607.77     .15       0 7150.97     .07       0 8214.28     .15       0
 8495.53     .07       0
#XS Ineff= 2 ,-1
       0  4925.6   17.55 5824.54 9505.58   18.65
Permanent Ineff=
       F       F
#Block Obstruct= 5 ,-1
  637.09 3378.84   23.39 5893.13 6473.28   19.74 6610.69 7129.77   19.63
 7435.11 8229.01   21.41 8968.56 9140.05   23.24
Bank Sta=5334.43,5633.48
XS Rating Curve= 0
Vertical n Elevations= 2
      12      19
Vertical n for Station=0
     .07      .1
Vertical n for Station=1148.33
     .15     .15
Vertical n for Station=4770.5
     .07      .1
Vertical n for Station=5031.2
     .12     .24
Vertical n for Station=5342.45
    .041    .041
Vertical n for Station=5464.54
     .07      .1
Vertical n for Station=6607.77
     .15     .15
Vertical n for Station=7150.97
     .07      .1
Vertical n for Station=8214.28
     .15     .15
Vertical n for Station=8495.53
     .07      .1
Vertical n Flow= 0
Exp/Cntr=.5,.3

Type RM Length L Ch R = 1 ,94111.47,401.24,613.78,883.44
XS GIS Cut Line= 6
     3185452.317    13761200.379     3181724.196    13756961.375
     3181576.608    13756857.394     3181383.895     13756741.18
     3181036.435    13756573.123      3179011.16    13754392.298
#Sta/Elev= 30
       0   24.06 1040.37   25.48 1095.08   13.09 1264.42   21.86  4859.5   17.38
 5059.82   15.13  5817.9     2.8 5829.37   -6.41 5848.71   -8.48 5890.52    -.57
 5903.72    5.28 6011.41    9.88 6240.92   12.45 6557.48   22.46 6598.45    4.95
 6635.07   23.06 6651.46   12.18 7237.37   24.37 7322.92   15.36 7604.68     .33
 7886.09    6.27 7920.82    22.7 7985.63    6.78 8013.55   24.48 8064.29   26.19
 8140.58    3.27 8173.25    21.3 8301.67   19.76 8583.97   26.18 9412.92   23.93
#Mann= 15 ,-1 , 0
       0     .15       0 1040.37     .07       0 1264.42     .15       0
  4859.5     .07       0 5059.82     .12       0 5829.37    .061       0
 5890.52     .07       0 6011.41     .12       0 6240.92     .07       0
 6651.46     .15       0 7237.37     .07       0 7322.92     .12       0
 7886.09     .07       0 8301.67     .15       0 8583.97     .07       0
#XS Ineff= 2 ,-1
       0 4964.37   17.37 6205.28 9412.92   18.49
Permanent Ineff=
       F       F
#Block Obstruct= 7 ,-1
   11.38 3572.24   23.31 1007.63 1206.11   22.88 6473.28 6763.36   20.05
 7160.31 7923.66   19.01 7938.93    8000   19.42 8061.07 8167.94   19.21
 9074.54 9364.97   23.37
Bank Sta=5817.9,5903.72
XS Rating Curve= 0
Vertical n Elevations= 2
      12      19
Vertical n for Station=0
     .15     .15
Vertical n for Station=1040.37
     .07      .1
Vertical n for Station=1264.42
     .15     .15
Vertical n for Station=4859.5
     .07      .1
Vertical n for Station=5059.82
     .12     .24
Vertical n for Station=5829.37
    .041    .041
Vertical n for Station=5890.52
     .07      .1
Vertical n for Station=6011.41
     .12     .24
Vertical n for Station=6240.92
     .07      .1
Vertical n for Station=6651.46
     .15     .15
Vertical n for Station=7237.37
     .07      .1
Vertical n for Station=7322.92
     .12     .24
Vertical n for Station=7886.09
     .07      .1
Vertical n for Station=8301.67
     .15     .15
Vertical n for Station=8583.97
     .07      .1
Vertical n Flow= 0
Exp/Cntr=.5,.3

Type RM Length L Ch R = 1 ,93497.69,595.01,788.36,392.17
XS GIS Cut Line= 4
     3186020.942    13761162.259     3181952.628    13756693.122
     3182039.508    13756439.512     3179780.258     13753976.09
#Sta/Elev= 30
       0   26.33  228.39   26.06  239.72   21.87  554.78   27.25 1378.62   26.64
 1412.06   24.25 1445.76   13.09 1536.84   24.25 1615.16   21.86 1626.51   26.03
 1764.13    21.8 2450.39   25.96  5160.5   21.89  5404.1   15.59 5537.81   19.71
 5783.19    15.7 5931.63    2.77 6183.25    3.88 6186.44   -1.27 6216.11   -8.18
 6236.56   -6.44 6257.64    7.04 6261.24    7.93 6559.62   12.03 6707.96    6.55
 6764.12    -.57 6770.82    5.64 6965.65    4.76 7463.39    22.5 9654.17   24.83
#Mann= 8 ,-1 , 0
       0     .07       0  289.91     .15       0 1386.53     .07       0
 1602.59     .15       0 5782.56     .12       0    6189    .061       0
 6257.64     .12       0 7380.71     .07       0
#Block Obstruct= 4 ,-1
   22.75 3959.04   23.14 1206.11 1633.59   23.72 6503.82 7312.98   11.78
 7541.11 9505.57    22.7
Bank Sta=6183.25,6261.24
XS Rating Curve= 0
Vertical n Elevations= 2
      10      17
Vertical n for Station=0
     .07      .1
Vertical n for Station=305.05
     .15     .15
Vertical n for Station=1391.55
     .07      .1
Vertical n for Station=1615.16
     .15     .15
Vertical n for Station=5783.19
     .12     .24
Vertical n for Station=6189.52
    .041    .041
Vertical n for Station=6257.64
     .12     .24
Vertical n for Station=7390.68
     .07      .1
Vertical n Flow= 0
Exp/Cntr=.3,.1

Type RM Length L Ch R = 1 ,92709.32,175.74,412.39,533.6
XS GIS Cut Line= 6
     3186824.641    13761340.153     3184575.194     13758771.34
      3182821.22    13756922.907     3182537.063     13756454.89
     3182286.239    13756134.098     3180316.847    13753886.659
#Sta/Elev= 30
       0   27.01  313.71   21.87  340.79   27.38  836.41   26.85  880.67    21.7
 1929.62   25.41 2075.87   22.68 2113.14   12.06 2214.92   25.03 2227.13   19.73
 2243.77   26.28 2284.06   20.75 2292.28   25.63 3516.53   24.78 5117.31   17.76
 5277.17   22.99 5592.39   16.65 6316.15   21.89  6530.1   15.88 6559.87    6.41
 6581.53   13.08 6780.18   13.58 7004.53    4.72  7060.8   -6.99 7089.31     -.7
 7096.37    6.15 7439.65   20.67 9582.07   26.22 9631.21   20.65 9905.83    22.7
#Mann= 7 ,-1 , 0
       0     .15       0 2051.99     .07       0  2272.6     .15       0
 6530.02     .12       0 7011.45    .061       0 7089.31     .12       0
  7437.6     .07       0
#Block Obstruct= 3 ,-1
   56.88 4596.13    22.3 2030.53 2305.34    23.4 9543.75 9917.19   22.28
Bank Sta=7004.53,7096.37
XS Rating Curve= 0
Vertical n Elevations= 2
      10      17
Vertical n for Station=0
     .15     .15
Vertical n for Station=2061.04
     .07      .1
Vertical n for Station=2284.06
     .15     .15
Vertical n for Station=6530.1
     .12     .24
Vertical n for Station=7012.49
    .041    .041
Vertical n for Station=7089.31
     .12     .24
Vertical n for Station=7439.65
     .07      .1
Vertical n Flow= 0
Exp/Cntr=.3,.1

Type RM Length L Ch R = 1 ,92296.93,192.45,296.7,335.41
XS GIS Cut Line= 6
     3187377.382    13761092.372     3182967.827    13756849.603
     3182729.277    13756462.309     3182610.833    13756134.098
     3182556.734    13755701.305     3180764.004    13753677.985
#Sta/Elev= 30
       0   24.73 2219.75   24.75 2266.62   22.06 2304.79   12.06 2407.35   25.03
 2420.44   19.73 2437.06   26.28 2472.22   20.75 2483.41   25.63 4055.98   24.33
 5178.71   22.42 5315.77   17.76 5344.92   22.08 5589.33   17.76 6043.02   22.08
 6098.22   16.65 6486.39   21.89 6590.29   15.59 6672.42   19.06 6706.18   16.65
 6735.86    6.41 6767.93   12.96 7078.39    4.29 7136.49     .06 7177.75  -12.12
 7207.12   -1.62 7207.66    4.22 7388.98   13.66 8070.96   23.6910063.63   23.94
#Mann= 7 ,-1 , 0
       0     .15       0 2242.38     .07       0  2467.1     .15       0
 6670.37     .12       0  7133.8    .061       0 7206.97     .12       0
 7445.78     .07       0
#Block Obstruct= 3 ,-1
  109.22 5160.41   22.36 2216.79 2418.32   22.93 8097.3310313.12   22.43
Bank Sta=7078.39,7207.66
XS Rating Curve= 0
Vertical n Elevations= 2
      10      17
Vertical n for Station=0
     .15     .15
Vertical n for Station=2244.26
     .07      .1
Vertical n for Station=2472.22
     .15     .15
Vertical n for Station=6672.42
     .12     .24
Vertical n for Station=7136.49
    .041    .041
Vertical n for Station=7207.12
     .12     .24
Vertical n for Station=7509.69
     .07      .1
Vertical n Flow= 0
Exp/Cntr=.5,.3

Type RM Length L Ch R = 1 ,92000.23,176.91,871.51,170.87
XS GIS Cut Line= 6
     3188345.272    13760704.255     3184451.321    13757987.285
     3183041.131    13756746.978     3182899.362     13756440.66
     3182737.064     13755403.76     3181002.488    13753499.123
#Sta/Elev= 30
       0   24.81   95.34   26.88  127.45   14.53  222.37   28.87     342   22.26
  414.18   28.87  621.23   28.87  641.59   22.26 2204.14   22.69 2256.17   12.95
 2407.13   11.28 2756.94    12.6 2829.39   25.03 2894.35      22 6696.79   22.08
 7017.03   15.01 7049.21    6.41  7234.2     .95 7479.95    5.57  7511.4   -4.74
 7549.19   -7.15 7585.67    5.24 7609.62   10.76 7636.68    1.48 7769.02    -.89
 8023.15   21.78  8088.9   16.11 8726.45   22.6610033.69    23.710598.37   24.05
#Mann= 8 ,-1 , 0
       0     .15       0 2204.14     .07       0 2894.35     .15       0
 7017.03     .12       0  7511.4    .061       0 7585.67     .07       0
 8726.45     .15       010033.69     .07       0
#XS Ineff= 2 ,-1
       0 5927.24   20.51 7893.3510598.37   23.86
Permanent Ineff=
       F       F
#Block Obstruct= 5 ,-1
   73.28  201.53   24.14  436.86 5583.62   21.97 2161.83 2912.98   22.67
 8337.18 9599.02   22.13 8338.2210142.32   21.64
Bank Sta=7479.95,7585.67
XS Rating Curve= 0
Vertical n Elevations= 2
      10      17
Vertical n for Station=0
     .15     .15
Vertical n for Station=2204.14
     .07      .1
Vertical n for Station=2894.35
     .15     .15
Vertical n for Station=7017.03
     .12     .24
Vertical n for Station=7511.4
    .041    .041
Vertical n for Station=7585.67
     .07      .1
Vertical n for Station=8726.45
     .15     .15
Vertical n for Station=10033.69
     .07      .1
Vertical n Flow= 0
Exp/Cntr=.5,.3

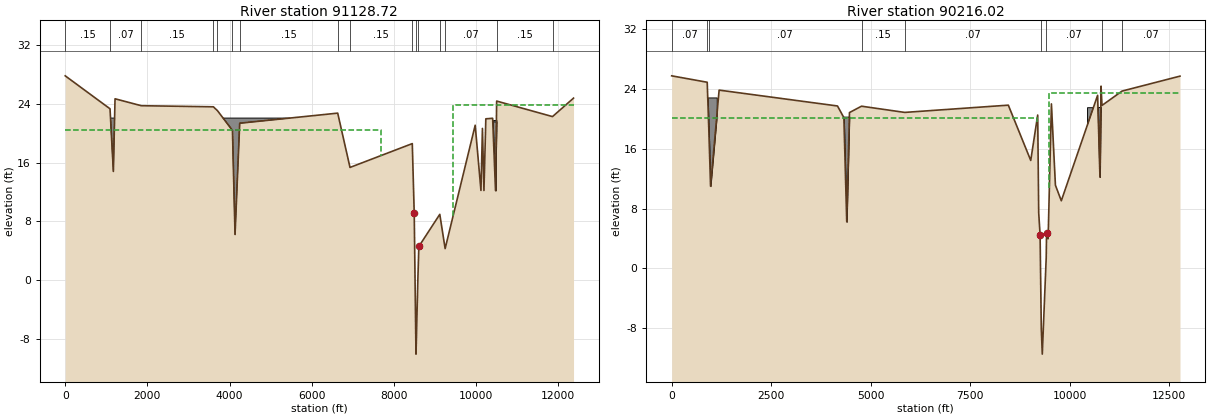
Type RM Length L Ch R = 1 ,91128.72,934.93,912.69,155.44
XS GIS Cut Line= 6
     3190754.188    13759739.109     3184739.305     13757663.93
     3183759.506    13757113.496     3183052.643    13756503.775
     3183219.685    13755728.444      3181121.73    13753439.502
#Sta/Elev= 30
       0   27.79 1090.56   23.31 1172.18    14.8 1212.79   24.67 1851.11   23.73
 3605.58   23.58 3704.85   23.06  4070.2   20.37 4133.17    6.23 4246.62   21.35
 6631.59   22.72 6930.74   15.34  8446.5   18.58 8493.59    9.09 8533.07   -8.55
 8536.98  -10.03 8582.73     .25 8606.25     4.6 9115.75    8.97 9245.86    4.31
 9977.44   21.0810117.58   12.2110153.51   20.6410190.49   12.2110236.27   21.95
10401.92   22.0210471.89   12.2110499.68   24.3611858.64   22.2512370.43   24.76
#Mann= 16 ,-1 , 0
       0     .15       0 1090.56     .07       0 1851.11     .15       0
 3605.58     .07       0 3704.85     .15       0  4070.2     .07       0
 4246.62     .15       0 6631.59     .07       0 6930.74     .15       0
  8446.5     .07       0 8533.07    .061       0 8582.73     .12       0
 9115.75    .042       0 9245.86     .07       010499.68     .15       0
11858.64     .07       0
#XS Ineff= 2 ,-1
       0 7674.24   20.45  9442.112370.43    23.8
Permanent Ineff=
       F       F
#Block Obstruct= 3 ,-1
  238.91 6577.93   22.0510236.2310683.66   21.7810236.45 11182.3   21.59
Bank Sta=8493.59,8606.25
XS Rating Curve= 0
Vertical n Elevations= 2
      10      17
Vertical n for Station=0
     .15     .15
Vertical n for Station=1090.56
     .07      .1
Vertical n for Station=1851.11
     .15     .15
Vertical n for Station=3605.58
     .07      .1
Vertical n for Station=3704.85
     .15     .15
Vertical n for Station=4070.2
     .07      .1
Vertical n for Station=4246.62
     .15     .15
Vertical n for Station=6631.59
     .07      .1
Vertical n for Station=6930.74
     .15     .15
Vertical n for Station=8446.5
     .07      .1
Vertical n for Station=8533.07
    .041    .041
Vertical n for Station=8582.73
     .12     .24
Vertical n for Station=9115.75
    .042    .042
Vertical n for Station=9245.86
     .07      .1
Vertical n for Station=10499.68
     .15     .15
Vertical n for Station=11858.64
     .07      .1
Vertical n Flow= 0
Exp/Cntr=.5,.3

Type RM Length L Ch R = 1 ,90216.02,192.17,144.01,261.75
XS GIS Cut Line= 6
     3192264.939    13758107.906      3185213.18    13757006.867
     3184495.626    13756797.419     3184121.201    13756540.002
     3183394.544    13755657.806     3181149.205    13753263.786
#Sta/Elev= 30
       0   25.74  893.26   24.88  932.31   18.76  977.43   10.99 1192.45   23.83
 4167.42   21.71 4327.85   20.15 4400.12    6.23 4468.63   20.83  4770.8   21.68
 5856.99   20.85 8460.72   21.82 9024.34   14.43 9199.19    20.5 9224.43    7.41
 9259.01    4.51 9289.75   -8.03 9314.42  -11.46 9413.15    1.43 9421.73    4.68
  9461.1    3.96 9543.88   21.99 9644.51   11.12 9792.57    9.04 10705.1   23.14
10763.79   12.2110791.04   24.3610814.49   21.7811318.66    23.712775.49    25.7
#Mann= 9 ,-1 , 0
       0     .07       0  893.26     .15       0  932.31     .07       0
  4770.8     .15       0 5856.99     .07       0 9289.75    .061       0
 9413.15     .07       010814.49     .15       011318.66     .07       0
#XS Ineff= 2 ,-1
       0 9172.04    20.1    949212775.49    23.5
Permanent Ineff=
       F       F
#Block Obstruct= 5 ,-1
  833.59 1132.82   22.85 1254.88 3204.84   21.25 4082.44  4531.3   20.29
 10452.211889.24   21.4810644.2710879.39   21.57
Bank Sta=9259.01,9421.73
XS Rating Curve= 0
Vertical n Elevations= 2
      10      17
Vertical n for Station=0
     .07      .1
Vertical n for Station=893.26
     .15     .15
Vertical n for Station=932.31
     .07      .1
Vertical n for Station=4770.8
     .15     .15
Vertical n for Station=5856.99
     .07      .1
Vertical n for Station=9289.75
    .041    .041
Vertical n for Station=9413.15
     .07      .1
Vertical n for Station=10814.49
     .15     .15
Vertical n for Station=11318.66
     .07      .1
Vertical n Flow= 0
Exp/Cntr=.5,.3