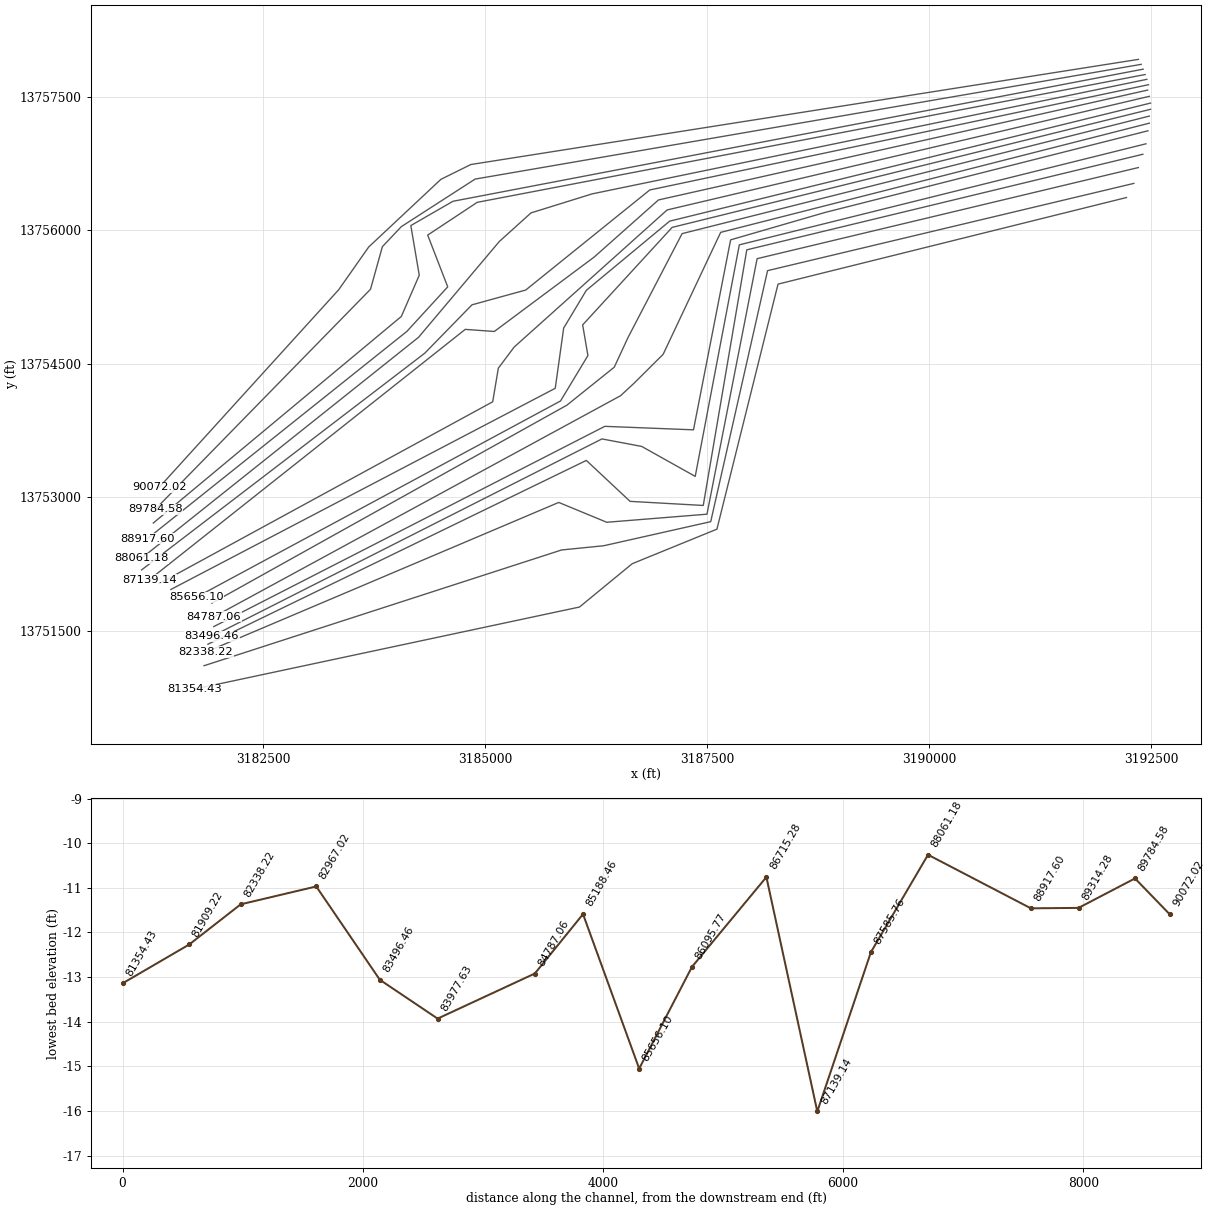
HEC-RAS study A100-00-00.prj: A100-00-00

--- A100-00-00.g01 (geometry) --- (continued)

Type RM Length L Ch R = 3 ,90082   ,,,
BEGIN DESCRIPTION:
FM528
END DESCRIPTION:
Bridge Culvert--1,0,-1,-1, 0
Deck Dist Width WeirC Skew NumUp NumDn MinLoCord MaxHiCord MaxSubmerge Is_Ogee
5,133,2.6,0, 118, 118, , , .95, 0, 0,0,,
       0   52.68   78.16 1009.24 1059.94  1063.6 1115.35 1117.99 1194.82 1381.69
 1555.74 1874.69 1876.31 1882.76 1885.32 2233.78 2523.76 3322.34 3379.31 3384.11
 3440.94 3445.83 3510.13 3513.05  3513.2 3516.12 3612.61 3616.61 3717.31 3719.92
 4428.05 4431.17 4550.01 4551.34  4629.3 4630.95 4632.83 4833.35 4835.92 4839.37
 4903.19 4903.25 4909.89 4989.13  4995.1 5366.43  5367.9 5448.83 5448.96 5745.76
 5838.23 6636.28 6686.82 6690.54 7198.06 7430.23    7436    7437  7587.9 7629.78
 7736.75  7822.4 7877.49 7981.86 8012.49  8154.7 8198.85 8300.32 8536.05    8623
    8721    8722    8737    8851    8917    8919    9047    9171    9172    9236
    9300    9364    9428    9492    9493    9617    9692    9693    9778    9907
    9908   10006   1009610298.1610567.5410568.4610720.72   10762   1076310770.46
10772.1310773.36   1082210822.2410828.6510830.25   11328   1132911551.2411631.98
11632.2411715.5811715.8911775.4211776.43 12448.912449.3312789.92
    23.4    23.4   21.41   21.36   20.53   20.53   19.67   19.76   20.03   20.42
    20.4   20.03   19.99    19.7   19.73   19.68   19.54   19.68      20   19.81
   20.13   19.94   20.01   20.17   20.17   20.23   20.23   20.02   20.07   20.22
    20.1   19.89   19.81   19.84   19.77   19.81   19.77   19.76   19.61   19.76
   19.77   19.61   19.69   19.72    19.8    19.8   19.65   19.67    19.8   19.82
   19.73   19.92   19.84   19.91   19.97   19.58   19.58   31.58   31.77   31.96
    31.8   31.86   31.76   31.91   31.83    31.8   31.88   31.66   31.77   32.26
   32.26   20.26   19.89   20.12   20.81   22.52    24.4   26.19   26.19   26.66
   26.94   26.89   26.67   26.18   26.18   24.34      23    31.5    31.5    31.5
   31.46   31.72   32.04   33.85   33.67   33.66   33.97   33.97   21.97   21.94
   21.97   22.09    22.1    34.1   35.25   35.23   35.35   23.35   23.35   23.43
   23.42   23.31   23.35    23.3   23.38   23.41   23.42   23.33
                                                                                
                                                                                
                                                                                
                                                                                
                                                                                
                                                                                
                                                                                
                                                                   19.44   19.93
   20.18   20.17   19.96   19.49
                                                                                
                                                                                
                                                                
       0       1    2.16  933.24  983.94   987.6 1039.35 1041.99 1118.82 1305.69
 1479.74 1798.69 1800.31 1806.76 1809.32 2157.78 2447.76 3246.34 3303.31 3308.11
 3364.94 3369.83 3434.13 3437.05  3437.2 3440.12 3536.61 3540.61 3641.31 3643.92
 4352.05 4355.17 4474.01 4475.34  4553.3 4554.95 4556.83 4757.35 4759.92 4763.37
 4827.19 4827.25 4833.89 4913.13  4919.1 5290.43  5291.9 5372.83 5372.96 5669.76
 5762.23 6560.28 6610.82 6614.54 7122.06 7354.23    7360    7361  7511.9 7553.78
 7660.75  7746.4 7801.49 7905.86 7936.49  8078.7 8122.85 8224.32 8460.05    8547
    8645    8646    8661    8775    8841    8843    8971    9095    9096    9160
    9224    9288    9352    9416    9417    9541    9616    9617    9702    9831
    9832    9930   1002010222.1610491.5410492.4610644.72   10686   1068710694.46
10696.1310697.36   1074610746.2410752.6510754.25   11252   1125311475.2411555.98
11556.2411639.5811639.8911699.4211700.43 12372.912373.3312713.92
    23.4    23.4   21.41   21.36   20.53   20.53   19.67   19.76   20.03   20.42
    20.4   20.03   19.99    19.7   19.73   19.68   19.54   19.68      20   19.81
   20.13   19.94   20.01   20.17   20.17   20.23   20.23   20.02   20.07   20.22
    20.1   19.89   19.81   19.84   19.77   19.81   19.77   19.76   19.61   19.76
   19.77   19.61   19.69   19.72    19.8    19.8   19.65   19.67    19.8   19.82
   19.73   19.92   19.84   19.91   19.97   19.58   19.58   31.58   31.77   31.96
    31.8   31.86   31.76   31.91   31.83    31.8   31.88   31.66   31.77   32.26
   32.26   20.26   19.89   20.12   20.81   22.52    24.4   26.19   26.19   26.66
   26.94   26.89   26.67   26.18   26.18   24.34      23    31.5    31.5    31.5
   31.46   31.72   32.04   33.85   33.67   33.66   33.97   33.97   21.97   21.94
   21.97   22.09    22.1    34.1   35.25   35.23   35.35   23.35   23.35   23.43
   23.42   23.31   23.35    23.3   23.38   23.41   23.42   23.33
                                                                                
                                                                                
                                                                                
                                                                                
                                                                                
                                                                                
                                                                                
                                                                   19.44   19.93
   20.18   20.17   19.96   19.49
                                                                                
                                                                                
                                                                
Pier Skew, UpSta & Num, DnSta & Num=  ,9236, 2 ,9160, 2 , 0 , 0 , 0 ,,
     2.5     2.5
     -30      23
     2.5     2.5
     -30      23
Pier Skew, UpSta & Num, DnSta & Num=  ,9300, 2 ,9224, 2 , 0 , 0 , 0 ,,
     2.5     2.5
     -30      23
     2.5     2.5
     -30      23
Pier Skew, UpSta & Num, DnSta & Num=  ,9364, 2 ,9288, 2 , 0 , 0 , 0 ,,
     2.5     2.5
     -30      23
     2.5     2.5
     -30      23
Pier Skew, UpSta & Num, DnSta & Num=  ,9428, 2 ,9352, 2 , 0 , 0 , 0 ,,
     2.5     2.5
     -30      23
     2.5     2.5
     -30      23
BR Coef=-1 , 1 , 1 ,1.05, 0 ,,,.8,-1,1.2,0,
WSPro=,,,, 1 ,,,, 0 ,,,, 0 ,,,,-1 ,-1 ,-1 , 0 , 0 , 0 , 0 , 0
BC Design=,, 0 ,, 0 ,,,,,,
BC HTab HWMax=26.27

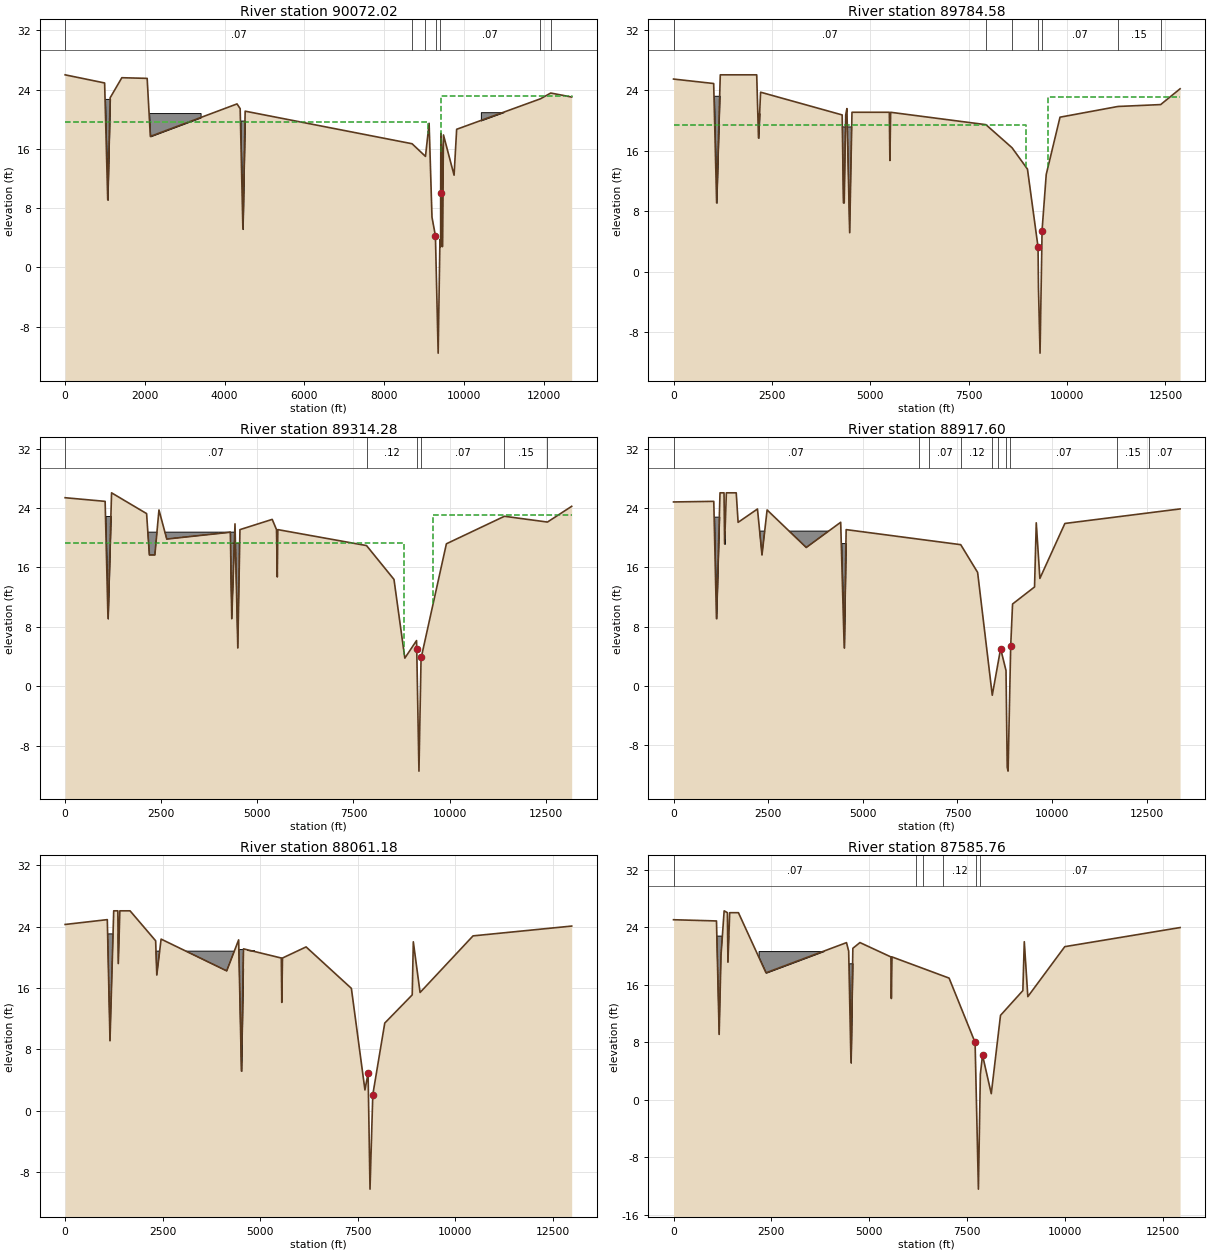
Type RM Length L Ch R = 1 ,90072.02,89.3,287.44,278.72
XS GIS Cut Line= 6
     3192358.546    13757920.693     3184840.286    13756739.355
      3184503.87    13756573.174     3183690.418     13755812.74
     3183352.759    13755332.893     3181330.403    13753111.586
#Sta/Elev= 30
       0   26.01  990.44   24.91 1068.39    9.11 1129.27   22.91 1422.11   25.62
 2056.92   25.53 2136.65   17.69 4310.07   22.08 4388.68   21.44 4457.33    5.16
 4513.86    21.1 8698.55    16.7 9034.85   14.99 9125.59   19.46 9198.06    6.77
 9283.77    4.27 9301.73     .19 9352.75  -11.59 9397.24    3.73  9414.6    2.79
 9415.57    9.99 9420.21   18.11 9456.04   14.59 9458.35    2.79 9485.72   17.89
  9751.8   12.45 9816.38   18.6511917.12   22.7712175.47   23.5512700.25   23.01
#Mann= 7 ,-1 , 0
       0     .07       0 8698.55     .12       0 9034.85     .07       0
 9301.73    .051       0 9397.24     .07       011917.12     .15       0
12175.47     .07       0
#XS Ineff= 2 ,-1
       0    9096    19.6 9418.7612700.25   23.18
Permanent Ineff=
       F       F
#Block Obstruct= 4 ,-1
  812.21 1410.69   22.76 1588.66  3396.1   20.84 4210.69 4509.92   19.83
10422.8512656.72   20.96
Bank Sta=9283.77,9415.57
XS Rating Curve= 0
Vertical n Elevations= 2
      10      17
Vertical n for Station=0
     .07      .1
Vertical n for Station=8698.55
     .12     .24
Vertical n for Station=9034.85
     .07      .1
Vertical n for Station=9301.73
    .041    .041
Vertical n for Station=9397.24
     .07      .1
Vertical n for Station=11917.12
     .15     .15
Vertical n for Station=12175.47
     .07      .1
Vertical n Flow= 0
Exp/Cntr=.5,.3

Type RM Length L Ch R = 1 ,89784.58,247.26,470.3,469.86
XS GIS Cut Line= 6
     3192390.176     13757864.87     3184889.027    13756575.816
     3184057.982    13756041.573     3183844.284    13755816.004
     3183710.701    13755337.807     3181286.719    13752865.601
#Sta/Elev= 30
       0    25.5 1020.27   24.91  1095.6    9.11  1188.3   26.06 2114.07   26.06
 2159.74   17.69 2212.59   23.76 4285.72   20.75 4318.56     9.1 4337.85     9.1
 4375.58   20.75  4406.1   21.59 4476.17    5.16 4535.17    21.1 5484.37    21.1
 5498.19   14.72 5517.68    21.1 7939.18   19.46 8603.37    16.4 8994.29   13.58
 9263.48    3.25 9273.52   -2.08 9314.17  -10.79 9361.47    3.93 9364.02    5.36
 9471.34   12.87 9821.49   20.4511293.91   21.8712379.16   22.1212872.89   24.21
#Mann= 7 ,-1 , 0
       0     .07       0 7939.18     .12       0 8603.37     .12       0
 9273.52    .051       0 9361.47     .07       011293.91     .15       0
12379.16     .07       0
#XS Ineff= 2 ,-1
       0 8969.83   19.39 9509.0812872.89   23.11
Permanent Ineff=
       F       F
#Block Obstruct= 4 ,-1
  790.84 1346.56   23.29 1913.64 3405.76   20.96 4125.19 4616.79   19.16
11514.38 12726.8   20.79
Bank Sta=9263.48,9364.02
XS Rating Curve= 0
Vertical n Elevations= 2
      10      17
Vertical n for Station=0
     .07      .1
Vertical n for Station=7939.18
     .12     .24
Vertical n for Station=8603.37
     .12     .24
Vertical n for Station=9273.52
    .041    .041
Vertical n for Station=9361.47
     .07      .1
Vertical n for Station=11293.91
     .15     .15
Vertical n for Station=12379.16
     .07      .1
Vertical n Flow= 0
Exp/Cntr=.5,.3

Type RM Length L Ch R = 1 ,89314.28,468.25,396.68,172.49
XS GIS Cut Line= 6
     3192412.413    13757810.867     3184639.713    13756326.503
      3184164.83    13756053.445     3184259.807    13755495.458
     3184057.982    13755032.447     3181264.752     13752711.83
#Sta/Elev= 30
       0    25.4 1040.83   24.91 1114.97    9.11 1207.89   26.06 2119.52   23.26
 2191.52   17.69 2334.66   17.69 2441.05   23.75    2644   19.83 4298.15   20.75
 4334.64     9.1 4418.78   21.88  4491.9    5.16 4547.62    21.1 5386.88   22.48
  5498.8    21.1 5518.35   14.72 5533.52    21.1 7840.33   18.95 8554.18   14.39
  8836.6    3.78 9141.15    6.15 9146.03    5.05 9203.71  -11.45 9257.05     3.3
 9263.86    3.88 9917.46   19.1911427.54    22.912545.64   22.1213176.44   24.24
#Mann= 6 ,-1 , 0
       0     .07       0 7840.33     .12       0 9141.15    .051       0
 9257.05     .07       011427.54     .15       012545.64     .07       0
#XS Ineff= 2 ,-1
       0 8825.71   19.32 9572.9513176.44   23.05
Permanent Ineff=
       F       F
#Block Obstruct= 4 ,-1
  812.21 1282.44   22.93 1800.59 4410.53   20.76 4232.06  4531.3   19.27
12430.9312728.87   20.82
Bank Sta=9146.03,9263.86
XS Rating Curve= 0
Vertical n Elevations= 2
      10      17
Vertical n for Station=0
     .07      .1
Vertical n for Station=7840.33
     .12     .24
Vertical n for Station=9141.15
    .041    .041
Vertical n for Station=9257.05
     .07      .1
Vertical n for Station=11427.54
     .15     .15
Vertical n for Station=12545.64
     .07      .1
Vertical n Flow= 0
Exp/Cntr=.5,.3

Type RM Length L Ch R = 1 ,88917.60,741.78,856.42,137.01
XS GIS Cut Line= 6
      3192434.65     13757750.51     3184912.771    13756314.631
     3184354.783    13755946.597     3184580.353    13755364.865
     3184120.485    13754864.613     3181198.851    13752536.093
#Sta/Elev= 30
       0   24.83 1063.27   24.91 1133.94    9.11 1228.15   26.06  1334.1   26.06
 1349.31   19.18 1395.74   26.06 1656.36   26.06 1706.23   22.08 2217.55   23.88
 2336.97   17.69 2472.12   23.75 3506.44   18.69 4415.77   22.09 4508.83    5.16
 4560.07    21.1 7586.88   19.07 8033.11   15.33    8420   -1.23 8640.39    5.05
 8782.88     2.1 8814.82  -10.95 8837.65  -11.46 8906.55    5.39    8956   11.07
 9536.73   13.37 9581.83   22.02 9677.53   14.52 10338.1   21.9313381.21   23.89
#Mann= 10 ,-1 , 0
       0     .07       0 6483.86     .12       0 6760.85     .07       0
 7586.88     .12       0 8413.43    .051       0 8574.01     .12       0
 8783.96    .051       0 8896.23     .07       011707.89     .15       0
12564.28     .07       0
#Block Obstruct= 5 ,-1
  961.83 1282.44   22.85 1202.24 1760.27   20.88 2009.49 4404.15    20.9
 4317.56 4574.05   19.2810393.6612857.59   20.55
Bank Sta=8640.39,8906.55
XS Rating Curve= 0
Vertical n Elevations= 2
      10      17
Vertical n for Station=0
     .07      .1
Vertical n for Station=6542.46
     .12     .24
Vertical n for Station=6794.95
     .07      .1
Vertical n for Station=7586.88
     .12     .24
Vertical n for Station=8420
    .041    .041
Vertical n for Station=8579
     .12     .24
Vertical n for Station=8785.93
    .041    .041
Vertical n for Station=8896.35
     .07      .1
Vertical n for Station=11737.32
     .15     .15
Vertical n for Station=12569.01
     .07      .1
Vertical n Flow= 0
Exp/Cntr=.3,.1

Type RM Length L Ch R = 1 ,88061.18,692.73,475.42,181.57
XS GIS Cut Line= 6
      3192453.71    13757696.506     3186206.827    13756409.607
     3185518.246     13756195.91     3185162.084    13755875.364
     3184252.288    13754798.712     3181132.949    13752316.421
#Sta/Elev= 30
       0   24.28 1081.33   24.91 1150.16    9.11 1245.26   26.06 1351.18   26.06
 1363.05   19.18  1402.9   26.06 1664.27   26.06    2320   22.15 2349.59   17.69
 2459.84   22.37 4140.93   18.22 4447.11   22.27 4518.69    5.16  4571.2    21.1
 5540.59    19.9 5552.84   14.11  5570.6    19.9 6175.77   21.35 7336.29   15.94
 7683.91    2.68 7764.62    4.88 7813.73  -10.26 7884.91    2.06 8191.71   11.41
 8895.62   15.09 8923.58   22.02 9096.55    15.410453.84   22.7912982.17   24.07
#Mann= 0 ,-1 , 0
#Block Obstruct= 4 ,-1
 1004.58 1410.69   23.05 1729.92 4422.98    20.8 4381.68 4595.42   18.57
    4400    4850      21
Bank Sta=7764.62,7884.91
XS Rating Curve= 0
Vertical n Elevations= 2
      10      17
Vertical n for Station=0
     .07      .1
Vertical n for Station=6380.02
     .12     .24
Vertical n for Station=7776.56
    .041    .041
Vertical n for Station=7884.91
     .07      .1
Vertical n for Station=11767.43
     .15     .15
Vertical n for Station=11956.18
     .07      .1
Vertical n Flow= 0
Exp/Cntr=.3,.1

Type RM Length L Ch R = 1 ,87585.76,245.52,446.62,77.24
XS GIS Cut Line= 6
      3192472.77    13757636.149     3186855.691     13756453.42
     3185458.886    13755329.249      3184853.41     13755163.04
     3184321.695    13754619.544     3181132.949    13752184.618
#Sta/Elev= 30
       0   25.08 1097.26   24.91 1165.71    9.11  1212.5   20.13 1292.99   26.32
 1375.95   26.06  1389.5   19.18 1434.86   26.06 1657.86   26.06  2361.5   17.69
 4417.93   21.89 4473.16   20.71 4532.05    5.16 4580.09    21.1 4760.81    21.9
 5551.67    19.9 5563.04   14.11 5580.23    19.9 7037.91   16.95 7701.82    7.99
  7786.5  -12.44 7836.48    3.57 7891.89    6.21 8115.14     .85  8350.8   11.76
 8921.76   15.21 8958.32   22.02 9048.89   14.37 9992.55   21.3312937.27   23.99
#Mann= 6 ,-1 , 0
       0     .07       0 6180.39     .12       0 6369.93     .07       0
 6893.76     .12       0  7735.2    .051       0 7838.44     .07       0
#Block Obstruct= 4 ,-1
  983.21 1474.81    22.8 2172.57 4423.68   20.71 4381.68 4616.79   19.01
 9976.0410310.25   20.61
Bank Sta=7701.82,7891.89
XS Rating Curve= 0
Vertical n Elevations= 2
      10      17
Vertical n for Station=0
     .07      .1
Vertical n for Station=6208.72
     .12     .24
Vertical n for Station=6614.19
     .07      .1
Vertical n for Station=6963.08
     .12     .24
Vertical n for Station=7736.22
    .041    .041
Vertical n for Station=7866.15
     .07      .1
Vertical n Flow= 0
Exp/Cntr=.3,.1

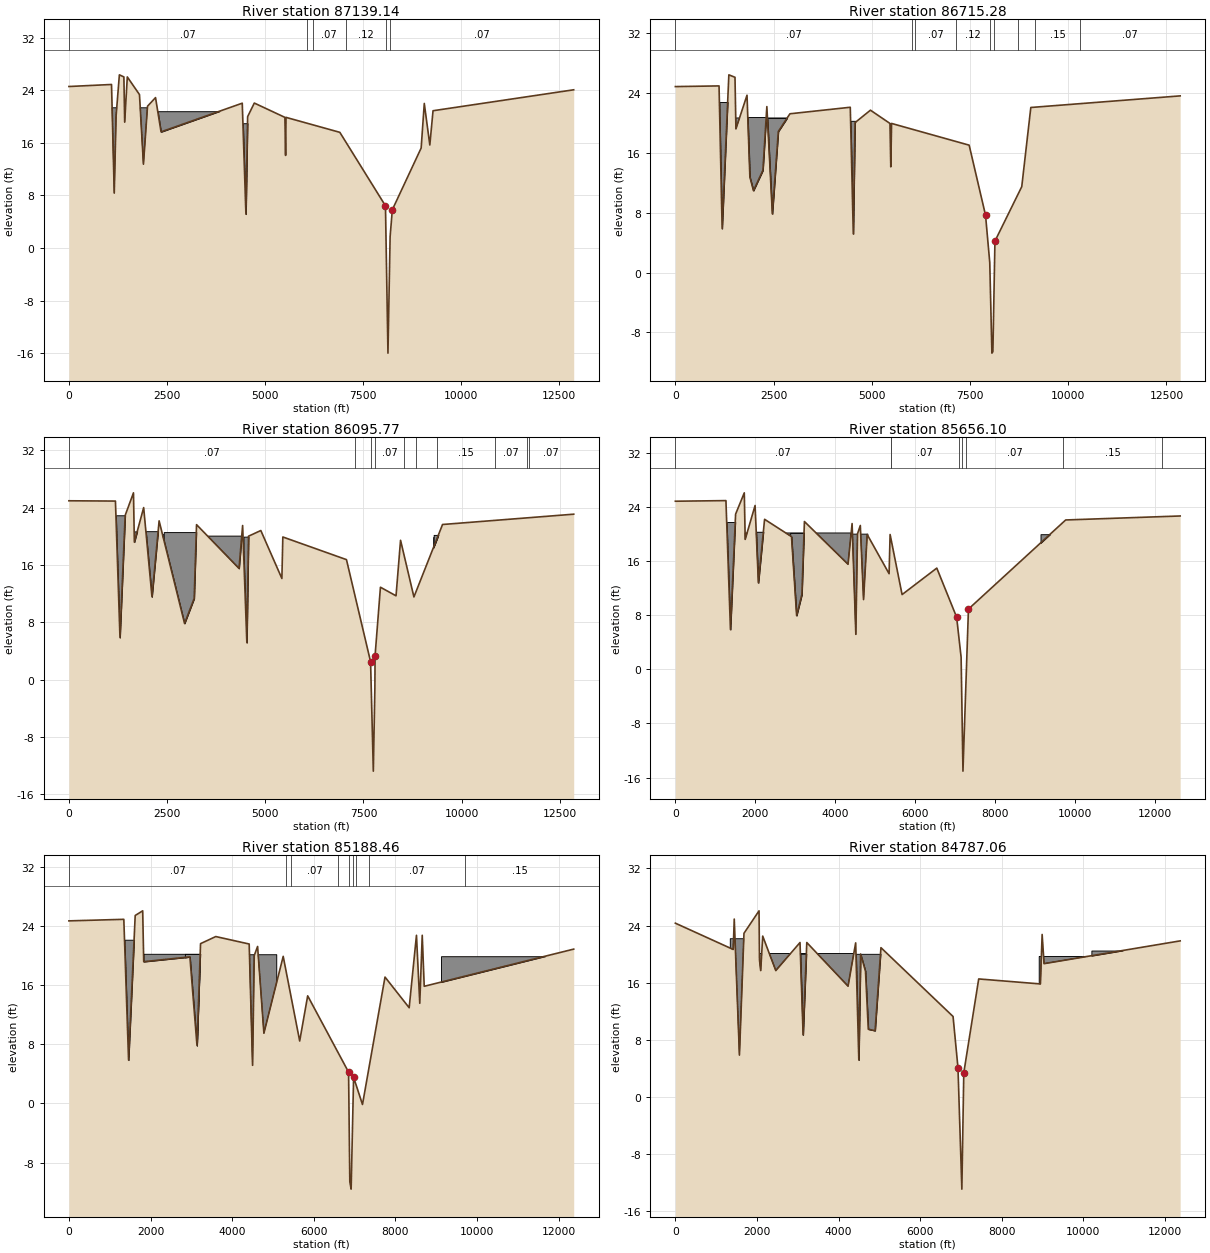
Type RM Length L Ch R = 1 ,87139.14,235.2,423.86,865.51
XS GIS Cut Line= 6
      3192463.24    13757575.793     3186953.763    13756341.338
     3186229.333    13755699.366     3185105.008    13754863.553
     3184777.773    13754887.266     3181220.818    13752074.782
#Sta/Elev= 30
       0    24.6 1087.16   24.91  1156.8    8.38 1203.97   20.13 1287.53   26.38
 1402.55   26.06 1422.86   19.18 1489.72   26.06 1800.41   23.37 1901.35   12.77
 2005.94    21.6 2209.83   22.91 2350.97   17.69 4422.16   22.06 4515.65    5.16
  4559.5   20.01 4729.59   22.08 5510.14    19.9 5527.76   14.11 5538.91    19.9
  6911.4   17.62  8075.5    6.43 8139.12  -16.01 8194.21    1.75 8250.67    5.83
 8986.13   15.23 9065.85   22.02 9206.99   15.69 9289.01   20.9112877.61    24.1
#Mann= 6 ,-1 , 0
       0     .07       0 6063.42     .12       0 6219.63     .07       0
  7056.8     .12       0  8095.9    .051       0 8191.83     .07       0
#Block Obstruct= 4 ,-1
  983.21 2073.28   21.36 2161.88 4408.43   20.84 4403.05 4638.17   19.01
 9999.6810328.16    20.4
Bank Sta=8075.5,8250.67
XS Rating Curve= 0
Vertical n Elevations= 2
      10      17
Vertical n for Station=0
     .07      .1
Vertical n for Station=6275.12
     .07      .1
Vertical n for Station=7091.51
     .12     .24
Vertical n for Station=8100.6
    .041    .041
Vertical n for Station=8193.28
     .07      .1
Vertical n Flow= 0
Exp/Cntr=.3,.1

Type RM Length L Ch R = 1 ,86715.28,603,619.51,706.86
XS GIS Cut Line= 6
       3192482.3    13757505.906     3187051.834    13756229.257
     3185328.293    13754688.157     3185150.212    13754450.716
      3185087.04    13754073.795     3181330.654    13752030.848
#Sta/Elev= 30
       0   24.82 1111.63   24.91 1190.79    5.86 1361.57   26.39 1517.88   26.06
 1541.55   19.18 1823.86   23.67 1896.73   12.77 1988.47   10.93 2228.72   13.64
 2328.92   22.15 2469.23    7.83 2620.86   18.82 2916.34   21.19 4452.39   22.06
 4529.54    5.16 4573.73   20.01 4966.02   21.67 5462.98    19.9 5483.88   14.11
 5503.64    19.9 7479.04      17 7895.75    7.65 8003.22    1.34 8058.11  -10.76
 8083.24  -10.57 8135.42    4.19 8817.97   11.46 9048.59   22.0312850.72   23.58
#Mann= 9 ,-1 , 0
       0     .07       0 6016.71     .12       0 6108.59     .07       0
 7150.52     .12       0 8014.22    .051       0 8118.95     .12       0
 8726.92     .07       0 9154.46     .15       010310.13     .07       0
#Block Obstruct= 6 ,-1
 1090.08 1432.06   22.76 1376.59 4420.51   20.63 1667.18 2329.77   20.75
 2340.66 2923.77   20.62 4452.14 4580.41   20.25 9600.2410307.99   20.19
Bank Sta=7895.75,8135.42
XS Rating Curve= 0
Vertical n Elevations= 2
      10      17
Vertical n for Station=0
     .07      .1
Vertical n for Station=6028.36
     .12     .24
Vertical n for Station=6109.4
     .07      .1
Vertical n for Station=7258.04
     .12     .24
Vertical n for Station=8024.48
    .041    .041
Vertical n for Station=8124.3
     .12     .24
Vertical n for Station=8761.05
     .07      .1
Vertical n for Station=9159.67
     .15     .15
Vertical n for Station=10342.31
     .07      .1
Vertical n Flow= 0
Exp/Cntr=.3,.1

Type RM Length L Ch R = 1 ,86095.77,360.55,439.67,200.04
XS GIS Cut Line= 6
     3192495.006    13757429.665     3187079.854    13756103.166
     3186141.464    13755325.924     3185886.281    13754901.854
     3185791.304    13754225.146     3181462.457    13751964.947
#Sta/Elev= 30
       0   24.95 1185.09   24.91 1300.66    5.86 1432.71   22.91 1644.46   26.06
 1666.68   19.18 1903.94      24 2115.53   11.55 2297.27   22.15  2945.6    7.83
 3190.15   11.32 3250.43   21.62 4332.67   15.51 4423.98    21.5 4531.68    5.16
  4574.5   20.01 4887.28    20.8 5423.66   14.11 5447.99    19.9 7068.32   16.74
 7682.24     2.5 7752.34  -12.77 7792.03   -1.18 7796.77    3.33 7933.64   12.89
 8330.67   11.69 8445.87   19.44 8786.25   11.53 9515.18   21.6412855.38   23.08
#Mann= 10 ,-1 , 0
       0     .07       0 7282.06     .12       0 7682.24    .051       0
 7792.03     .07       0 8539.18     .12       0  8846.3     .07       0
 9382.88     .15       010841.84     .07       011677.18     .15       0
11706.62     .07       0
#Block Obstruct= 9 ,-1
 1047.33 1474.81   22.93 1537.38 1822.01   20.68 1923.66 2287.02   20.71
 2261.88 2404.19   20.34  2415.2 3270.17   20.58 3535.84 4411.83   20.09
 4445.76 4573.97   19.95 9277.4310853.85   19.89 9288.83 10626.1   20.19
Bank Sta=7682.24,7796.77
XS Rating Curve= 0
Vertical n Elevations= 2
      10      17
Vertical n for Station=0
     .07      .1
Vertical n for Station=7285.24
     .12     .24
Vertical n for Station=7682.24
    .041    .041
Vertical n for Station=7792.03
     .07      .1
Vertical n for Station=8600.96
     .12     .24
Vertical n for Station=8902.59
     .07      .1
Vertical n for Station=9402.37
     .15     .15
Vertical n for Station=10865.53
     .07      .1
Vertical n for Station=11678.1
     .15     .15
Vertical n for Station=11730.53
     .07      .1
Vertical n Flow= 0
Exp/Cntr=.3,.1

Type RM Length L Ch R = 1 ,85656.10,431.31,467.64,205.8
XS GIS Cut Line= 6
     3192495.006    13757359.779     3187107.874    13756033.115
     3186099.978    13754937.471     3186159.338     13754593.18
     3185850.664    13754082.681      3181748.03    13751877.078
#Sta/Elev= 30
       0   24.82 1266.14   24.91 1379.64    5.86 1508.26   22.91 1725.78   26.06
 1748.63   19.18 1996.05   24.19 2079.11   12.77 2233.89   22.15  2908.2   19.59
 3037.09    7.92 3168.03   11.03 3231.71   21.82 4323.52   15.51 4425.32   21.52
 4519.02    5.16 4561.32   20.01 4631.29   21.24  4712.1   10.29 4803.51    19.9
 5351.95   14.11 5376.91    19.9  5677.3   11.03 6546.34   14.94 7042.53     7.7
 7155.37    1.77  7201.5  -15.05 7338.98    8.89 9773.57   22.0512640.71   22.64
#Mann= 8 ,-1 , 0
       0     .07       0 5399.48     .12       0 5400.74     .07       0
 7097.88     .12       0 7167.91    .051       0  7279.4     .07       0
 9701.87     .15       012184.51     .07       0
#Block Obstruct= 6 ,-1
 1175.57 1624.43   21.75 1519.17 4403.08   20.13 1880.92 2265.65   20.31
 2874.54 3259.34   20.14 4392.24 4819.57   19.96 9143.3512563.78   19.95
Bank Sta=7042.53,7338.98
XS Rating Curve= 0
Vertical n Elevations= 2
       9      16
Vertical n for Station=0
     .07      .1
Vertical n for Station=5400.9
     .07      .1
Vertical n for Station=7117.74
     .12     .24
Vertical n for Station=7171.88
    .041    .041
Vertical n for Station=7282.72
     .07      .1
Vertical n for Station=9716.8
     .15     .15
Vertical n for Station=12198.31
     .07      .1
Vertical n Flow= 0
Exp/Cntr=.3,.1

Type RM Length L Ch R = 1 ,85188.46,492.84,401.4,276.77
XS GIS Cut Line= 6
       3192482.3    13757283.538     3187219.956    13755963.064
     3186610.477    13754795.006      3186456.14    13754462.588
     3185921.897    13754035.193     3181923.767    13751811.176
#Sta/Elev= 30
       0    24.7 1345.61   24.91 1461.83    5.86 1624.28   25.43 1808.07   26.06
 1833.07   19.18  2964.7   19.83 3138.78    7.83 3225.56   21.62 3598.88   22.58
 4417.05   21.57  4500.1    5.16 4541.17   20.01 4623.25   21.24  4777.9    9.51
 5250.75    19.9 5654.84    8.45 5850.63   14.56  6852.4    4.24 6882.88  -10.58
  6915.2  -11.59 6975.69    3.54 7193.35    -.14 7745.08    17.1 8337.25   12.95
 8515.86   22.75 8597.01   13.55  8657.3   22.75 8705.97   15.8512368.73   20.88
#Mann= 9 ,-1 , 0
       0     .07       0 5326.47     .12       0 5442.24     .07       0
 6594.39     .12       0  6852.4    .051       0 6973.12     .07       0
 7024.08     .12       0  7347.4     .07       0 9713.16     .15       0
#Block Obstruct= 5 ,-1
 1218.32 1688.55   22.15 1701.82 4375.85   20.25 2842.37 3291.19   20.23
 4429.51 5092.08   20.12 9118.0412652.73   19.92
Bank Sta=6852.4,6975.69
XS Rating Curve= 0
Vertical n Elevations= 2
       9      16
Vertical n for Station=0
     .07      .1
Vertical n for Station=5330.73
     .12     .24
Vertical n for Station=5453.49
     .07      .1
Vertical n for Station=6609.16
     .12     .24
Vertical n for Station=6852.4
    .041    .041
Vertical n for Station=6973.3
     .07      .1
Vertical n for Station=7047.31
     .12     .24
Vertical n for Station=7379.87
     .07      .1
Vertical n for Station=9794.51
     .15     .15
Vertical n Flow= 0
Exp/Cntr=.3,.1

Type RM Length L Ch R = 1 ,84787.06,975.59,809.43,567.65
XS GIS Cut Line= 6
       3192482.3    13757204.121     3187654.271    13755977.074
     3187006.767    13754607.456     3186679.514    13754282.919
     3186527.372    13754142.042     3181945.735    13751657.406
#Sta/Elev= 30
       0   24.33 1417.81   20.65 1443.51   24.91 1570.74    5.86 1682.04   22.91
 2051.18   26.06 2062.42   19.18  2092.3   17.69 2141.42   22.52 2462.06   17.69
 3055.69   21.62 3132.37    8.68 3222.21   21.62 4233.78   15.51 4420.43   21.57
 4498.04    5.16 4542.02   20.01 4661.12    17.6 4729.97    9.48 4896.59    9.27
 5040.63    20.9 6808.41   11.26 6928.79    4.08 7023.99  -12.92 7071.35    3.37
 7437.13   16.52 8950.19   15.82 8992.38   22.75 9039.48   18.6612376.71   21.85
#Mann= 0 ,-1 , 0
#Block Obstruct= 6 ,-1
 1346.56 1795.42   22.15 1916.34 4392.84   20.08 2992.37 3248.85   20.05
 4413.58  5097.5   20.04 8921.0412655.29   19.67   10200   12500    20.5
Bank Sta=6928.79,7071.35
XS Rating Curve= 0
Vertical n Elevations= 2
       9      16
Vertical n for Station=0
     .07      .1
Vertical n for Station=5278.41
     .12     .24
Vertical n for Station=6953.81
    .041    .041
Vertical n for Station=7071.35
     .07      .1
Vertical n for Station=7137.65
     .12     .24
Vertical n for Station=7269.21
     .07      .1
Vertical n for Station=9956.36
     .15     .15
Vertical n Flow= 0
Exp/Cntr=.3,.1

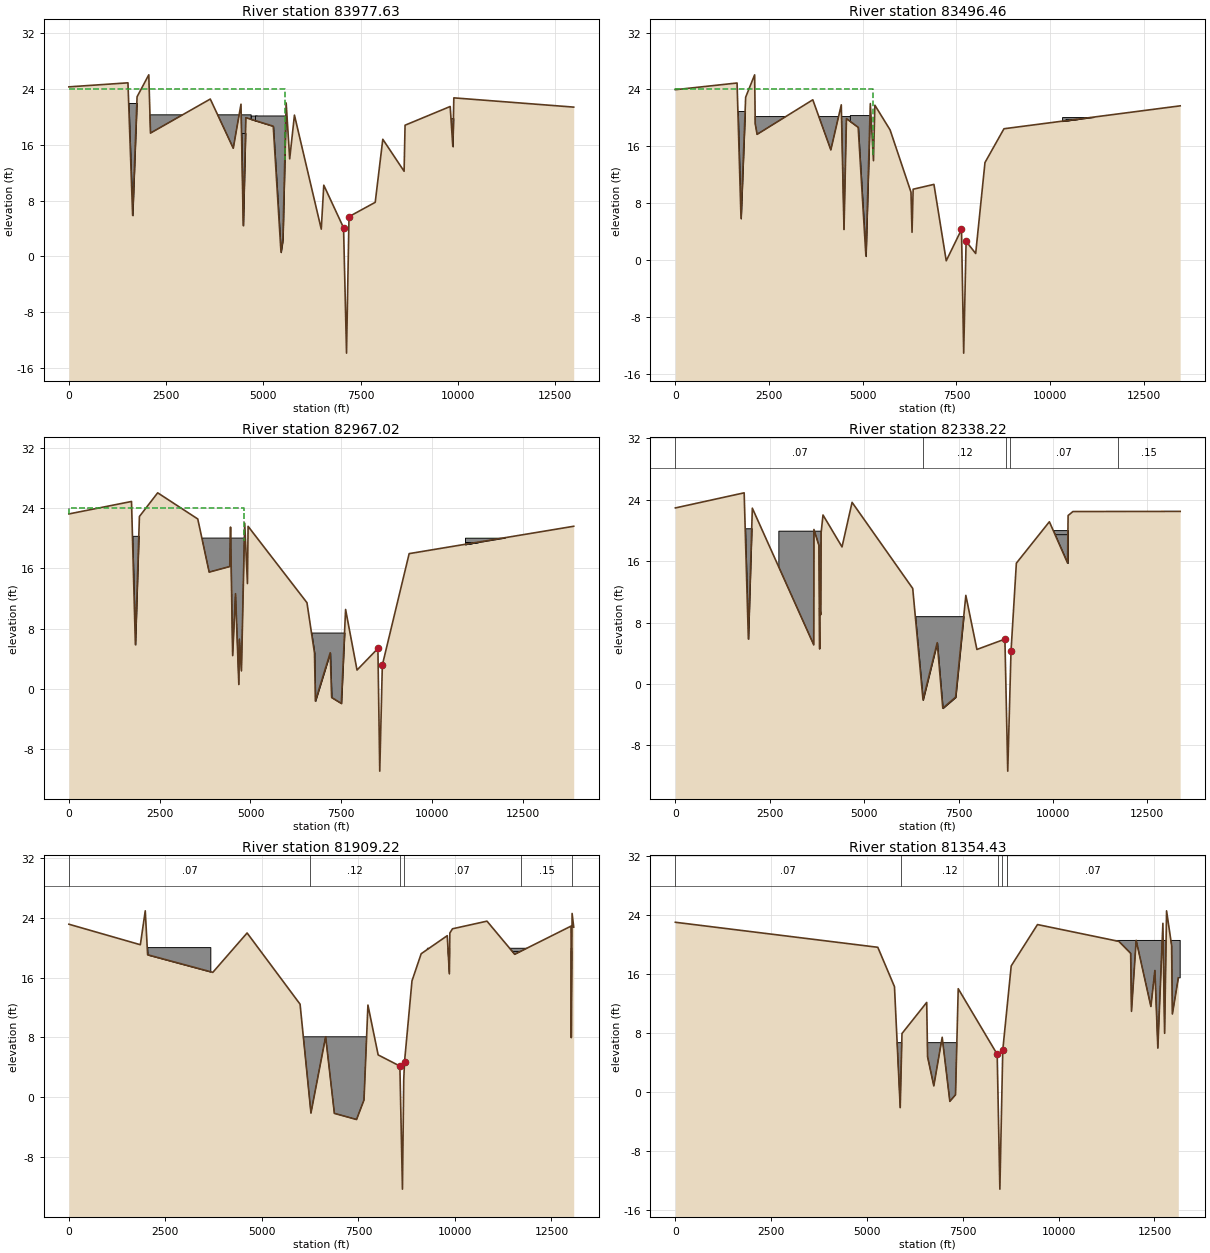
Type RM Length L Ch R = 1 ,83977.63,179.07,481.18,242.6
XS GIS Cut Line= 6
     3192466.416    13757118.351     3188831.125    13756201.237
     3187766.352    13755893.013      3187348.23    13753758.541
     3186349.291    13753797.752     3181945.735     13751547.57
#Sta/Elev= 30
       0   24.33 1518.08   24.91 1638.75    5.86 1752.69   22.91 2053.57   26.06
 2097.65   17.69 3634.73   22.58 4225.77   15.51 4424.07   21.84 4482.88     4.4
 4549.44    19.9  5253.3   18.68 5452.84     .56 5500.96    2.37 5585.27   22.02
 5676.36   13.99 5798.37   20.27 6487.87    3.89 6552.81    10.2 7061.05    4.09
 7137.39  -13.93 7200.87    5.68 7875.05    7.74 8069.85    16.8 8617.56    12.2
 8642.28   18.82 9802.55   21.51  9870.1   15.76 9896.22   22.7512977.95   21.42
#Mann= 0 ,-1 , 0
#XS Ineff= 2 , 0
       0    5550      24               0
Permanent Ineff=
       F       F
#Block Obstruct= 6 ,-1
 1453.44 1859.54   22.02 1858.82    4685   20.31 4360.31 4616.79    17.7
 4677.23 4827.31   20.21 4784.85 5584.07   20.22 9744.6112929.76   19.83
Bank Sta=7061.05,7200.87
XS Rating Curve= 0
Vertical n Elevations= 2
       9      16
Vertical n for Station=0
     .07      .1
Vertical n for Station=7086.87
    .041    .041
Vertical n for Station=7187.7
     .07      .1
Vertical n for Station=10957.29
     .15     .15
Vertical n Flow= 0
Exp/Cntr=.3,.1

Type RM Length L Ch R = 1 ,83496.46,1422.88,529.43,939.49
XS GIS Cut Line= 6
      3192444.18    13756972.224     3187864.423    13755836.972
     3187367.755    13753235.508     3186764.814    13753572.182
     3186317.202    13753656.419     3181923.767    13751437.734
#Sta/Elev= 30
       0   23.97 1646.21   24.91 1751.51    5.86 1875.21   22.91 2114.88   26.06
  2130.9   19.18 2180.57   17.69 3666.63   22.55 4147.79   15.51 4426.73   21.84
 4499.02    4.32  4564.4    19.9 4877.29   18.68 5084.16     .56  5201.6   22.02
 5285.51   13.99 5322.48   21.79 5728.68   18.32 6286.25    9.57 6314.14    3.93
 6343.65    9.98 6898.64   10.66 7226.79    -.08 7633.71    4.32  7692.5  -13.06
 7756.87    2.66 8012.36     .94 8260.36   13.73 8766.93   18.4813468.18    21.7
#Mann= 0 ,-1 , 0
#XS Ineff= 2 , 0
       0    5280      24               0
Permanent Ineff=
       F       F
#Block Obstruct= 6 ,-1
 1538.93 1966.41   20.97  2001.5 4379.52   20.19  4349.4  4712.7   20.19
 4655.36  5215.2    20.410317.5713478.76   20.1210410.5113865.22   19.86
Bank Sta=7633.71,7756.87
XS Rating Curve= 0
Vertical n Elevations= 2
       9      16
Vertical n for Station=0
     .07      .1
Vertical n for Station=7126.8
     .12     .24
Vertical n for Station=7655.44
    .041    .041
Vertical n for Station=7755.51
     .07      .1
Vertical n for Station=7828.91
     .12     .24
Vertical n for Station=8084.34
     .07      .1
Vertical n for Station=11686.96
     .15     .15
Vertical n Flow= 0
Exp/Cntr=.3,.1

Type RM Length L Ch R = 1 ,82967.02,274.45,628.81,395.1
XS GIS Cut Line= 6
     3192409.236    13756854.687     3187948.484    13755780.932
     3187458.129    13752908.848     3186634.221    13752954.835
     3186141.464     13753414.78     3181879.833    13751349.866
#Sta/Elev= 30
       0   23.25 1724.16   24.91 1830.56    5.86 1941.74   22.91 2444.86   26.06
 3548.46   22.58 3862.43   15.51 4428.97   16.25 4450.71    21.5 4509.09     4.4
 4588.16   12.64 4679.35     .56 4694.35    6.59 4751.07    2.37 4840.59   22.02
 4916.48   13.99 4934.37    21.6 6555.62   11.44 6763.06    4.74 6786.79   -1.65
    7196    4.78 7234.27   -1.17 7501.81   -1.96 7619.12   10.54 7934.01    2.48
 8508.61    5.35 8559.86  -10.97 8630.88    3.14 9369.63   17.9713900.61   21.61
#Mann= 0 ,-1 , 0
#XS Ineff= 2 , 0
       0    4830      24               0
Permanent Ineff=
       F       F
#Block Obstruct= 7 ,-1
 1624.43 2051.91   20.34 3496.86  3696.2   20.01 3680.14 4846.48   20.04
  6588.6 7700.16    7.4710906.4713564.91   20.0910915.4513829.04   19.51
10915.4513829.04   19.51
Bank Sta=8508.61,8630.88
XS Rating Curve= 0
Vertical n Elevations= 2
       8      15
Vertical n for Station=0
     .07      .1
Vertical n for Station=6863.57
     .12     .24
Vertical n for Station=8527.98
    .041    .041
Vertical n for Station=8619.08
     .07      .1
Vertical n for Station=12275.58
     .15     .15
Vertical n Flow= 0
Exp/Cntr=.3,.1

Type RM Length L Ch R = 1 ,82338.22,238.19,429,552.04
XS GIS Cut Line= 6
     3192358.409    13756705.383     3188064.726    13755681.636
     3187500.159    13752810.776     3186371.267    13752719.924
     3185830.617    13752942.824     3181857.866    13751261.997
#Sta/Elev= 30
       0   22.94 1822.03   24.91 1933.45    5.86 2038.69   22.91 3665.19    5.09
 3670.36   20.13 3802.88   18.05 3822.27    4.56 3822.77    9.89 3851.53    9.03
 3861.31   19.75  3910.5   22.02 4414.04   17.86 4680.46   23.67 6287.05   12.44
 6559.62    -2.1  6935.7    5.37 7083.65   -3.17 7423.66   -1.73 7693.66   11.54
 7986.65    4.49 8728.62    5.84 8803.81  -11.37 8890.19    4.24 9032.06   15.74
 9906.51   21.1410388.24   15.7610402.47   21.9510530.96   22.4713370.92   22.49
#Mann= 5 ,-1 , 0
       0     .07       0 6571.54     .12       0 8751.13    .051       0
 8870.13     .07       011723.36     .15       0
#Block Obstruct= 5 ,-1
  1731.3 2094.66   20.29 2740.91  3916.5   19.91 6273.88 7663.21    8.83
 9910.2413374.39   20.05  9913.413394.64   19.52
Bank Sta=8728.62,8890.19
XS Rating Curve= 0
Vertical n Elevations= 2
       8      15
Vertical n for Station=0
     .07      .1
Vertical n for Station=6573.81
     .12     .24
Vertical n for Station=8751.29
    .041    .041
Vertical n for Station=8871.54
     .07      .1
Vertical n for Station=11735.81
     .15     .15
Vertical n Flow= 0
Exp/Cntr=.3,.1

Type RM Length L Ch R = 1 ,81909.22,314.04,554.79,680.67
XS GIS Cut Line= 6
     3192307.583     13756527.49     3188182.477    13755547.063
      3187542.19    13752726.715     3186337.419    13752456.208
     3185862.536    13752408.719     3181835.899    13751108.227
#Sta/Elev= 30
       0   23.12 1850.88   20.38  1977.9   24.91 2038.72   19.04 3727.62   16.69
 4615.79   21.95 5987.63   12.44  6269.7    -2.1 6650.17    8.09 6876.16   -2.15
 7450.82   -2.97 7643.72    -.36 7745.41   12.32 8010.62    5.66    8573    4.17
 8639.62  -12.27 8672.77    2.32 8693.78    4.77 8886.61   15.55 9125.04   19.18
 9800.08   21.59 9855.33    16.5 9867.52   21.95 9936.18   22.5110829.42   23.53
11547.38    19.113006.81   22.8713013.27    7.9713034.14   24.5613075.58   22.73
#Mann= 6 ,-1 , 0
       0     .07       0  6246.6     .12       0 8576.79    .051       0
 8672.77     .07       011707.22     .15       013029.03     .07       0
#Block Obstruct= 4 ,-1
 1226.39 3663.25   20.06 5968.87  7721.5    8.08 9284.1513773.14   19.91
 9310.9913269.85   19.46
Bank Sta=8573,8693.78
XS Rating Curve= 0
Vertical n Elevations= 2
       8      15
Vertical n for Station=0
     .07      .1
Vertical n for Station=6266.98
     .12     .24
Vertical n for Station=8579.24
    .041    .041
Vertical n for Station=8672.77
     .07      .1
Vertical n for Station=11717.07
     .15     .15
Vertical n for Station=13034.14
     .07      .1
Vertical n Flow= 0
Exp/Cntr=.3,.1

Type RM Length L Ch R = 1 ,81354.43,261.86,599.91,633.93
XS GIS Cut Line= 6
     3192224.989    13756368.656     3188300.228    13755395.669
      3187612.24    13752642.654     3186657.965    13752254.382
     3186064.362    13751767.628     3181728.111    13750845.092
#Sta/Elev= 30
       0   23.01 5282.05   19.62 5717.06   14.29 5866.92    -2.1 5913.23    7.94
 6557.81   12.15 6580.95    4.78 6743.52     .85 6962.07    7.43 7161.89   -1.25
 7309.88    -.36  7380.5   14.01 8397.07    5.13  8467.2  -13.14  8542.8     5.7
 8763.13    17.1 9448.71    22.711573.18   20.4211880.26    18.811901.42   10.94
12023.86   20.5612407.74    11.612512.29   16.4812589.23    5.9712721.13   22.87
12765.56    7.9712816.69   24.5612948.94   19.8612968.68   10.5913124.43   15.48
#Mann= 6 ,-1 , 0
       0     .07       0 5874.36     .12       0 8425.23    .051       0
 8520.64     .07       0 8647.03     .12       0 8658.71     .07       0
#Block Obstruct= 2 ,-1
 5535.88 7374.05     6.711117.1813171.79   20.55
Bank Sta=8397.07,8542.8
XS Rating Curve= 0
Vertical n Elevations= 2
       7      14
Vertical n for Station=0
     .07      .1
Vertical n for Station=5881.96
     .12     .24
Vertical n for Station=8425.69
    .041    .041
Vertical n for Station=8542.8
     .07      .1
Vertical n for Station=8659.43
     .07      .1
Vertical n Flow= 0
Exp/Cntr=.3,.1