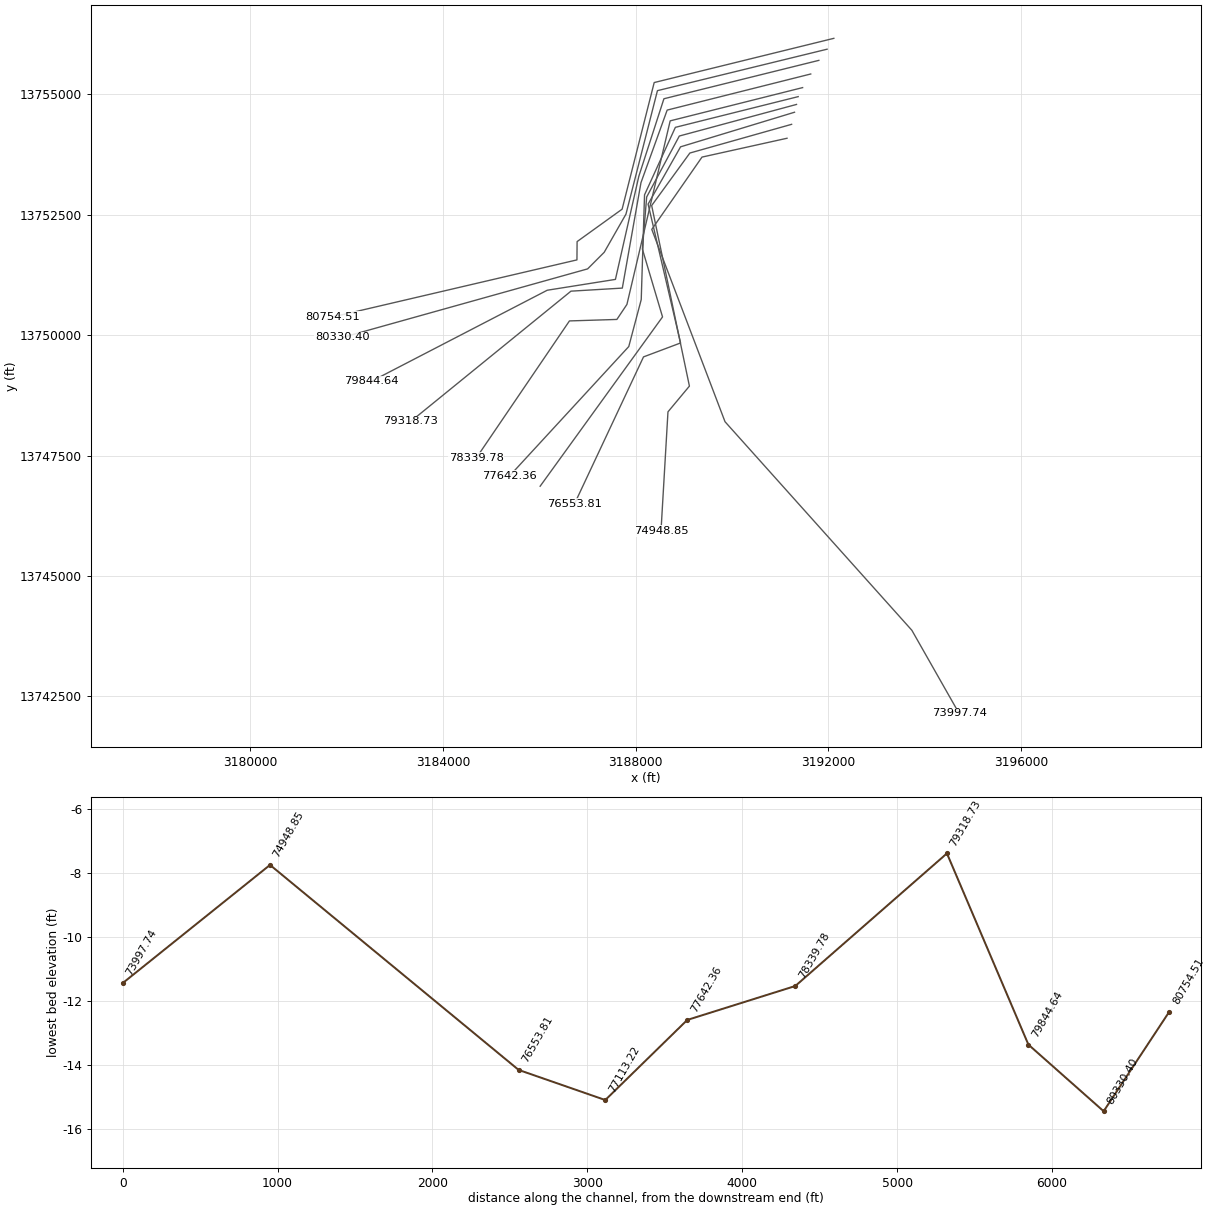
HEC-RAS study A100-00-00.prj: A100-00-00

--- A100-00-00.g01 (geometry) --- (continued)

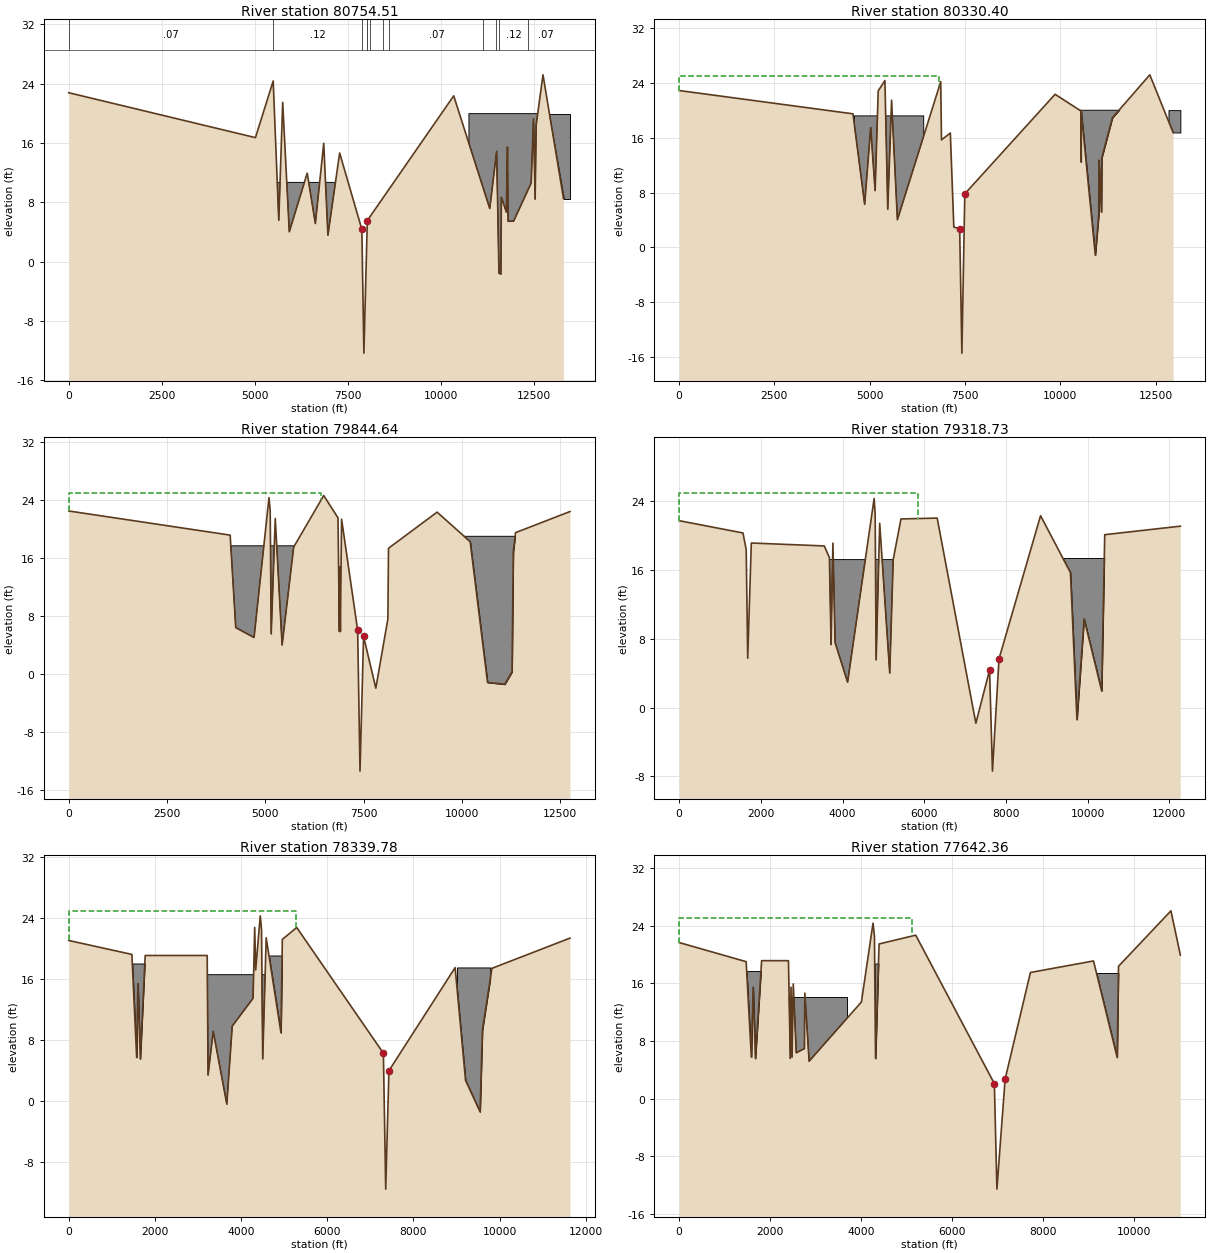
Type RM Length L Ch R = 1 ,80754.51,553.31,424.11,257.64
XS GIS Cut Line= 6
     3192113.805    13756162.172     3188384.335    13755244.275
      3187718.31    13752615.295     3186783.786    13751942.398
     3186780.471    13751562.492     3181715.161    13750378.912
#Sta/Elev= 30
       0   22.76 5015.89   16.71 5492.95   24.34 5642.53    5.57 5747.75   21.46
 5925.62    4.03 6406.86   11.93 6625.55    5.14 6850.43   15.95 6963.07    3.57
 7277.91   14.64 7874.11    4.36  7929.1  -12.32 8021.35    5.5410342.25   22.34
11310.78    7.1611495.05   14.8711557.96   -1.5511610.51   -1.6811621.69    8.68
 11758.1    6.6711786.89   15.4411802.43    5.4511950.37    5.4512422.87   10.58
12486.21   19.2612529.35    8.4312558.41   18.4512740.71   25.1713292.42    8.48
#Mann= 12 ,-1 , 0
       0     .07       0 5496.02     .12       0 7890.38    .051       0
 8011.74     .07       0 8024.37     .12       0 8087.77     .07       0
 8455.17     .12       0 8617.08     .07       011141.57     .12       0
11485.45     .07       011567.19     .12       012348.66     .07       0
#Block Obstruct= 3 ,-1
 1449.32 1857.08   19.79 5535.88 7203.05   10.6810751.1713465.64   19.94
Bank Sta=7874.11,8021.35
XS Rating Curve= 0
Vertical n Elevations= 2
       7      14
Vertical n for Station=0
     .07      .1
Vertical n for Station=5542.35
     .12     .24
Vertical n for Station=7891.71
    .041    .041
Vertical n for Station=8021.35
     .07      .1
Vertical n for Station=8027.55
     .12     .24
Vertical n for Station=8091.71
     .07      .1
Vertical n for Station=8518.55
     .12     .24
Vertical n for Station=8660.18
     .07      .1
Vertical n for Station=11201.54
     .12     .24
Vertical n for Station=11495.05
     .07      .1
Vertical n for Station=11610.51
     .12     .24
Vertical n for Station=12352.17
     .07      .1
Vertical n Flow= 0
Exp/Cntr=.3,.1

Type RM Length L Ch R = 1 ,80330.40,640.19,485.77,277.99
XS GIS Cut Line= 6
     3191974.032    13755936.628     3188451.622    13755076.059
     3187798.357    13752512.776     3187346.545    13751720.139
     3187002.255    13751375.849     3181909.403     13749951.58
#Sta/Elev= 30
       0   22.88 4561.61   19.48 4868.05    6.28 5026.26   17.47 5142.39    8.28
 5223.52   22.82 5399.31   24.34 5473.97    5.57 5573.85   21.46 5727.17    4.03
 6863.62   24.17 6883.39   15.68 7115.77   16.68 7207.03    2.97 7360.66    2.68
  7418.5  -15.43  7495.1    7.81 9864.21   22.3310543.75   19.8910545.04   12.47
10546.79   12.6810546.82    19.910918.78   -1.1311009.55    4.7511013.14   12.73
11078.53    5.1711088.64   13.0611366.67    18.912347.91   25.1712958.76   16.76
#Mann= 0 ,-1 , 0
#XS Ineff= 2 , 0
       0    6830      25               0
Permanent Ineff=
       F       F
#Block Obstruct= 4 ,-1
 4600.41 6417.22   19.1810387.3911776.72   20.0812838.6713149.83   20.02
   12200   12500      20
Bank Sta=7360.66,7495.1
XS Rating Curve= 0
Vertical n Elevations= 2
       7      14
Vertical n for Station=0
     .07      .1
Vertical n for Station=5101.55
     .12     .24
Vertical n for Station=6345.47
     .07      .1
Vertical n for Station=7115.77
     .12     .24
Vertical n for Station=7372.92
    .041    .041
Vertical n for Station=7486.84
     .07      .1
Vertical n for Station=7584.05
     .12     .24
Vertical n for Station=7655.61
     .07      .1
Vertical n for Station=10609.62
     .12     .24
Vertical n for Station=11406.79
     .07      .1
Vertical n Flow= 0
Exp/Cntr=.3,.1

Type RM Length L Ch R = 1 ,79844.64,226.41,525.9,156.76
XS GIS Cut Line= 6
     3191802.491    13755704.731     3188586.194    13754907.844
       3188065.1    13753298.185     3187579.401    13751157.392
     3186163.431    13750932.489     3182516.881    13749043.313
#Sta/Elev= 30
       0    22.5 4104.47   19.17  4246.5    6.43 4711.93    5.06 5091.98   24.34
 5122.54   22.52 5147.86    5.57 5251.07   21.46 5425.34    4.03 5719.17   17.52
  6483.2   24.63 6846.35   21.55 6882.31    5.89 6886.06   14.79 6906.98    5.89
 6937.44   21.37 7346.41    6.06 7405.85  -13.35 7496.76    5.21  7808.1   -1.92
 8114.62    7.63 8130.46   17.36 9366.72   22.3410206.54   18.27 10648.4   -1.13
11086.79   -1.3811271.08     .3411303.55   16.8411359.64   19.5112744.66   22.42
#Mann= 0 ,-1 , 0
#XS Ineff= 2 , 0
       0    6415      25               0
Permanent Ineff=
       F       F
#Block Obstruct= 3 ,-1
 4039.69 5813.74    17.7 9933.4711429.67   19.0811428.91 11506.6   19.08
Bank Sta=7346.41,7496.76
XS Rating Curve= 0
Vertical n Elevations= 2
       7      14
Vertical n for Station=0
     .07      .1
Vertical n for Station=4690.94
     .12     .24
Vertical n for Station=5880.64
     .07      .1
Vertical n for Station=7117.13
     .12     .24
Vertical n for Station=7306.23
     .07      .1
Vertical n for Station=7353
    .041    .041
Vertical n for Station=7478.04
     .07      .1
Vertical n for Station=7757.19
    .041    .041
Vertical n for Station=7805.32
     .07      .1
Vertical n for Station=10053.45
     .12     .24
Vertical n for Station=11271.08
     .07      .1
Vertical n Flow= 0
Exp/Cntr=.3,.1

Type RM Length L Ch R = 1 ,79318.73,416.71,978.95,666.93
XS GIS Cut Line= 6
     3191634.127    13755422.006     3188653.481    13754672.342
     3188109.557    13753164.814     3187722.611    13750977.052
     3186656.488    13750913.403     3183329.666     13748208.56
#Sta/Elev= 30
       0   21.76 1563.45   20.33 1642.32   18.39 1679.32    5.76 1767.62   19.16
 3554.12   18.82 3679.02   17.46 3720.03    7.34 3764.54   19.14 3818.89    7.57
 4124.43    2.97  4773.6   24.34 4798.89   22.52 4822.89    5.57 4909.84   21.46
 5155.86    4.03 5240.52   17.23 5430.65   21.96 6317.01   22.06 7263.49   -1.81
 7599.09    4.38 7669.99   -7.38    7830    5.68 8847.41   22.34 9578.39   15.72
 9737.92   -1.38 9913.28   10.3410343.46    1.9510417.82   20.1312268.67   21.12
#Mann= 0 ,-1 , 0
#XS Ineff= 2 , 0
       0    5849      25               0
Permanent Ineff=
       F       F
#Block Obstruct= 4 ,-1
  616.05 1069.89   19.77  3462.6 5407.63   17.23  9287.310655.13   17.42
 11773.412457.45   19.28
Bank Sta=7599.09,7830
XS Rating Curve= 0
Vertical n Elevations= 2
       7      14
Vertical n for Station=0
     .07      .1
Vertical n for Station=4160.15
     .12     .24
Vertical n for Station=5406.02
     .07      .1
Vertical n for Station=6466.64
     .12     .24
Vertical n for Station=7105.39
     .07      .1
Vertical n for Station=7255.87
    .041    .041
Vertical n for Station=7762.98
     .07      .1
Vertical n for Station=9426.05
     .12     .24
Vertical n for Station=10135.89
     .07      .1
Vertical n Flow= 0
Exp/Cntr=.3,.1

Type RM Length L Ch R = 1 ,78339.78,335.5,697.42,1570.4
XS GIS Cut Line= 6
     3191465.764    13755139.282     3188716.045    13754448.969
     3187818.085     13750637.59     3187609.548    13750326.295
     3186624.742    13750295.441     3184689.682    13747448.278
#Sta/Elev= 30
       0   21.11 1466.01   19.28 1577.07    5.76 1606.68   15.46  1661.2    5.57
 1774.99   19.14 3214.18   19.14 3234.37    3.45 3354.22    9.19 3669.84    -.37
 3794.97    9.87  4278.6   13.52  4316.7   22.82  4339.4   17.24 4445.96   24.34
 4475.36   22.52  4502.7    5.57 4583.39   21.46  4926.5       9 4957.83   21.25
 5292.22   22.81 7303.69    6.32 7357.76  -11.52 7432.57    4.02 8968.95   17.55
 9210.74    2.76 9548.36   -1.38 9602.76    9.36 9822.43   17.45   11635   21.42
#Mann= 0 ,-1 , 0
#XS Ineff= 2 , 0
       0    5270      25               0
Permanent Ineff=
       F       F
#Block Obstruct= 5 ,-1
 1429.01 1813.74   18.09 3059.54 4598.47   16.62 4635.11 5001.53   19.14
 9013.38  9782.8   17.5711189.6911619.38   19.31
Bank Sta=7303.69,7432.57
XS Rating Curve= 0
Vertical n Elevations= 2
       7      14
Vertical n for Station=0
     .07      .1
Vertical n for Station=3450.06
     .12     .24
Vertical n for Station=4957.83
     .07      .1
Vertical n for Station=5835.2
     .12     .24
Vertical n for Station=7318.53
    .041    .041
Vertical n for Station=7428.67
     .07      .1
Vertical n for Station=8504.09
     .12     .24
Vertical n for Station=9627.48
     .07      .1
Vertical n Flow= 0
Exp/Cntr=.3,.1

Type RM Length L Ch R = 1 ,77642.36,379.22,529.14,455.4
XS GIS Cut Line= 6
      3191373.64    13754951.859     3188823.908     13754314.14
     3188183.652     13752912.89     3188115.115    13750738.368
     3187856.447    13749763.366     3185386.172    13747081.933
#Sta/Elev= 30
       0   21.66 1473.83      19 1588.22    5.76 1627.19   15.46  1677.6    5.57
 1814.13   19.14 2403.88   19.14 2443.36    5.57 2459.54   15.46 2482.38    5.76
 2509.15   15.92 2575.45    6.35 2754.13    6.93 2763.72   14.64 2857.84    5.18
 4007.06    13.4 4262.22   24.34 4293.65   22.52 4317.69    5.57  4394.9   21.46
 5200.43   22.68 6928.89    2.07 6984.96  -12.58 7165.53     2.7 7721.85    17.5
 9108.43    19.1 9627.98    5.71 9657.57   18.3610809.73   26.0611016.68   19.92
#Mann= 0 ,-1 , 0
#XS Ineff= 2 , 0
       0    5110      25               0
Permanent Ineff=
       F       F
#Block Obstruct= 7 ,-1
  794.56    1021    19.6 1147.77 1281.11   19.07 1392.37 1923.66    17.7
 2271.76 3700.76   14.03 4250.38 4488.55   18.74 9123.66 9948.09   17.43
 9936.1510014.55   19.24
Bank Sta=6928.89,7165.53
XS Rating Curve= 0
Vertical n Elevations= 2
       7      14
Vertical n for Station=0
     .07      .1
Vertical n for Station=2941.22
     .12     .24
Vertical n for Station=4646.18
     .07      .1
Vertical n for Station=5315.97
     .12     .24
Vertical n for Station=6940.73
    .041    .041
Vertical n for Station=7136.79
     .12     .24
Vertical n for Station=7576.5
     .07      .1
Vertical n Flow= 0
Exp/Cntr=.3,.1

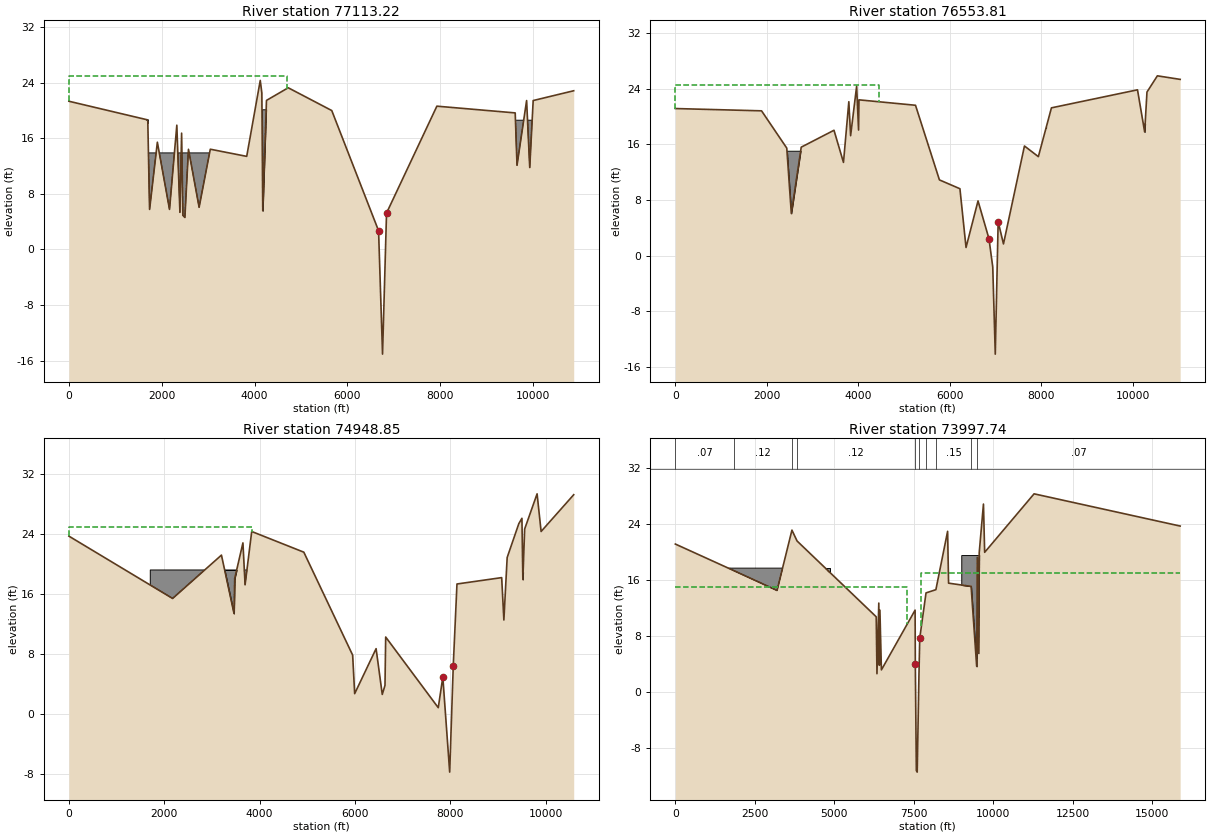
Type RM Length L Ch R = 1 ,77113.22,216.51,559.41,408.61
XS GIS Cut Line= 6
     3191338.697    13754789.848     3188905.804    13754134.051
      3188228.11    13752868.433     3188139.195    13751786.643
     3188557.497    13750378.595      3186016.49    13746863.834
#Sta/Elev= 30
       0   21.34 1698.97   18.65 1738.06    5.76 1905.59   15.44 2167.39    5.76
 2324.83   17.89 2391.69    5.34 2427.94   16.74 2454.81    4.91  2498.5     4.6
 2575.76   14.42 2804.96    6.07 3046.19   14.43 3830.51    13.4 4122.27   24.34
 4156.47   22.52 4176.17    5.57 4256.29   21.46 4724.93   23.28 5662.56      20
 6670.99    2.69 6756.55  -15.08 6842.51    5.23 7927.14   20.63 9614.28   19.66
 9653.64   12.12 9860.15   21.44 9927.64   11.7910001.61   21.4410874.75   22.85
#Mann= 0 ,-1 , 0
#XS Ineff= 2 , 0
       0    4690      25               0
Permanent Ineff=
       F       F
#Block Obstruct= 4 ,-1
 1518.84 1700.23   18.71 1612.21 3242.75    13.9 4067.18 4305.34   20.18
 9325.1910406.11   18.61
Bank Sta=6670.99,6842.51
XS Rating Curve= 0
Vertical n Elevations= 2
       7      14
Vertical n for Station=0
     .07      .1
Vertical n for Station=2650.98
     .12     .24
Vertical n for Station=4433.97
     .07      .1
Vertical n for Station=4960.27
     .12     .24
Vertical n for Station=6681.58
    .041    .041
Vertical n for Station=6803.79
     .12     .24
Vertical n for Station=7651.63
     .07      .1
Vertical n Flow= 0
Exp/Cntr=.5,.3

Type RM Length L Ch R = 1 ,76553.81,97.67,1604.97,1666.16
XS GIS Cut Line= 6
       3191297.4    13754627.838     3188931.771    13753909.653
     3188257.748    13752720.243     3188931.771    13749837.818
     3188162.444    13749548.558     3186729.048     13746496.27
#Sta/Elev= 30
       0   21.14 1884.73   20.81 2435.86   15.46 2535.48    6.07 2751.99   15.59
 3468.62   18.02 3676.07    13.4 3793.11   22.12 3832.18   17.24 3963.63   24.34
 4006.22   18.05  4014.9   22.39 5251.04   21.61 5774.08   10.89 6222.49    9.62
 6356.21    1.18 6618.18    7.87 6857.52    2.44  6940.3   -1.62  6995.5  -14.14
 7058.59    4.88 7174.74    1.69 7633.51   15.76 7937.58   14.23 8223.68   21.24
10105.65   23.8310262.35   17.7810312.86   23.5110540.26   25.84 11038.7   25.33
#Mann= 0 ,-1 , 0
#XS Ineff= 2 , 0
       0    4450    24.5 9609.74       0    17.5
Permanent Ineff=
       F       F
#Block Obstruct= 4 ,-1
 1704.17 2053.95    18.7 2326.72 2912.98   15.08 8104.82 8287.14   18.45
10182.3410387.45   18.99
Bank Sta=6857.52,7058.59
XS Rating Curve= 0
Vertical n Elevations= 2
       7      14
Vertical n for Station=0
     .07      .1
Vertical n for Station=2293.75
     .12     .24
Vertical n for Station=4176.18
     .07      .1
Vertical n for Station=4643.8
     .12     .24
Vertical n for Station=6919.57
    .041    .041
Vertical n for Station=7058.59
     .12     .24
Vertical n for Station=7953.76
     .07      .1
Vertical n Flow= 0
Exp/Cntr=.5,.3

Type RM Length L Ch R = 1 ,74948.85,1513.79,951.11,1164.21
XS GIS Cut Line= 6
     3191237.043     13754376.88     3189124.484    13753780.799
     3188331.843    13752690.604     3189115.484    13748942.075
     3188670.281    13748407.831      3188525.52    13745934.873
#Sta/Elev= 30
       0   23.72 2174.92   15.41 3199.43   21.19 3463.17    13.4 3477.36   18.07
 3649.93   22.82 3695.12   17.24 3834.17   24.34 4927.06   21.58 5951.18    7.86
 5993.52    2.72 6442.77    8.72 6572.26    2.62 6629.29    3.82 6644.04   10.27
 7746.74     .85 7842.34    4.93 7986.25   -7.74 8061.33    6.45 8139.04   17.34
  9076.7   18.19 9122.79   12.54 9191.88   20.87 9435.89   25.38 9501.38    26.1
 9520.84   17.94 9558.86   24.67 9819.39   29.36 9903.82   24.3410587.42   29.24
#Mann= 0 ,-1 , 0
#XS Ineff= 2 , 0
       0    3840      25    8900       0    17.4
Permanent Ineff=
       F       F
#Block Obstruct= 3 ,-1
 1706.48 3918.09   19.21 3132.82  3645.8   19.21 9378.81 9731.99   18.93
Bank Sta=7842.34,8061.33
XS Rating Curve= 0
Vertical n Elevations= 2
       7      14
Vertical n for Station=0
     .07      .1
Vertical n for Station=2071.02
     .12     .24
Vertical n for Station=3945.12
     .07      .1
Vertical n for Station=4179.1
     .12     .24
Vertical n for Station=7899.25
    .041    .041
Vertical n for Station=8032.53
     .12     .24
Vertical n for Station=8114.73
     .07      .1
Vertical n for Station=9546.43
     .15     .15
Vertical n Flow= 0
Exp/Cntr=.5,.3

Type RM Length L Ch R = 1 ,73997.74,188.82,105.04,185.82
XS GIS Cut Line= 6
     3191141.743    13754087.803     3189376.808    13753696.691
     3188334.148    13752195.712     3189854.599    13748202.838
     3193733.594    13743872.895     3194713.893    13742147.816
#Sta/Elev= 30
       0   21.12 1851.85    17.3 3197.01    14.5 3665.21   23.11 3825.98   21.56
 6315.11   10.74 6338.64    2.62 6396.31   12.69 6414.54    3.82 6431.13   11.69
 6478.18    3.16 7537.65   11.69 7544.59    4.01 7576.66   -11.2 7603.58  -11.43
    7659    2.49 7683.81    7.71 7881.34   14.15 8191.34   14.61 8559.93   22.94
 8589.98   15.54 9298.68   15.08 9474.02    3.66  9494.7   19.22 9529.41    5.53
 9554.35   19.92 9687.09   26.83 9724.66   19.9411278.89   28.2915872.23   23.69
#Mann= 10 ,-1 , 0
       0     .07       0 1851.85     .12       0 3665.21     .07       0
 3825.98     .12       0 7537.65    .041       0    7659     .12       0
 7881.34     .07       0 8191.34     .15       0 9298.68     .12       0
  9494.7     .07       0
#XS Ineff= 2 ,-1
       0 7288.05      15 7735.0115872.23      17
Permanent Ineff=
       F       F
#Block Obstruct= 3 ,-1
 1596.91 4833.33   17.41 1652.91 4850.78   17.69 8989.31 9624.43   19.55
Bank Sta=7544.59,7683.81
XS Rating Curve= 0
Vertical n Elevations= 2
       7      14
Vertical n for Station=0
     .07      .1
Vertical n for Station=1851.85
     .12     .24
Vertical n for Station=3665.21
     .07      .1
Vertical n for Station=3825.98
     .12     .24
Vertical n for Station=7537.65
    .041    .041
Vertical n for Station=7659
     .12     .24
Vertical n for Station=7881.34
     .07      .1
Vertical n for Station=8191.34
     .15     .15
Vertical n for Station=9298.68
     .12     .24
Vertical n for Station=9494.7
     .07      .1
Vertical n Flow= 0
Exp/Cntr=.5,.3