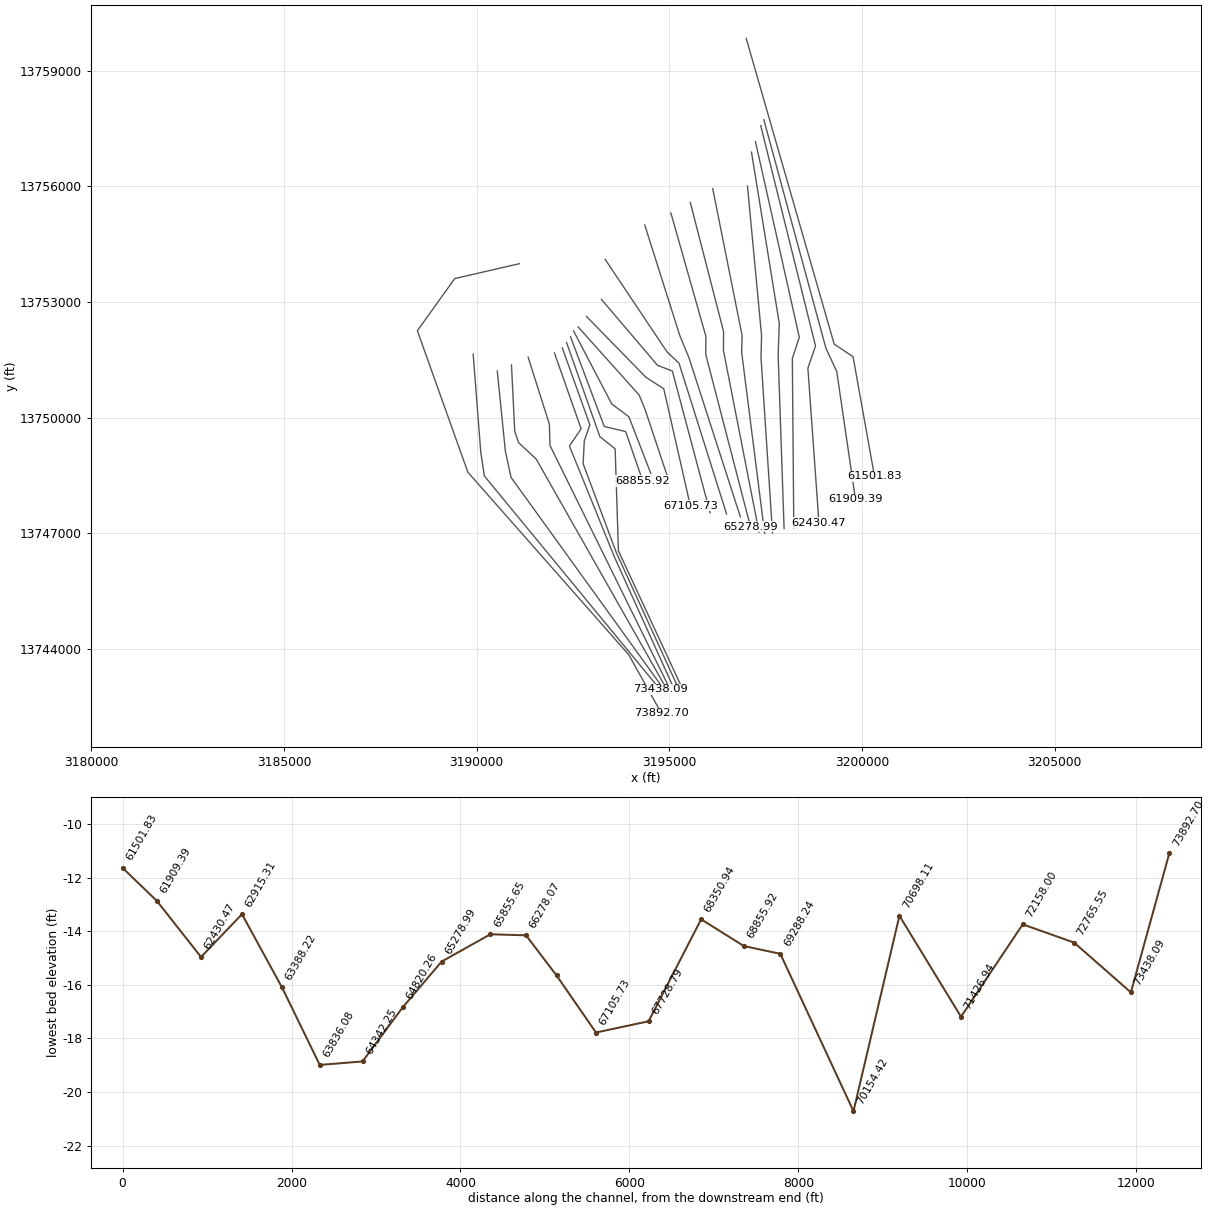
HEC-RAS study A100-00-00.prj: A100-00-00

--- A100-00-00.g01 (geometry) --- (continued)

Type RM Length L Ch R = 3 ,73902   ,,,
BEGIN DESCRIPTION:
W Bay Area Blvd.
END DESCRIPTION:
Bridge Culvert--1,0,-1,-1, 0
Deck Dist Width WeirC Skew NumUp NumDn MinLoCord MaxHiCord MaxSubmerge Is_Ogee
5,95,2.6,0, 81, 81, , , .95, 0, 0,0,,
    3737    4219    4471    4680    4818    4935    5180    5342    6248    6661
    6945    7089    7090    7169    7287    7288    7370    7452    7533    7534
    7634    7734    7735    7833    7959    7962    8062    8139    8139    8162
    8531    8531  8555.3 8556.23    8574    8574    9147    9147 9300.38 9321.78
 9588.23 9598.57  9612.2 9615.72 9791.52 9823.2511189.2411250.1911258.0411457.01
11475.9511759.4911798.0211968.2412628.9913142.8313853.8113882.4613904.3513916.59
14119.43 14188.714203.1214516.2714848.3114848.5314848.6114967.8314993.5315105.42
15118.3615247.3515350.5415464.0915636.8115688.5415706.4915730.2715763.3815810.12
15834.71
    23.5      24    23.3      22      20      18    16.1      16    14.6   15.81
   15.88   18.13   19.43   20.63   22.62   22.62      24    25.1   25.54   25.54
    25.2   23.64   23.64   21.43   18.22   18.37   16.65    16.3    28.3   28.27
      31      19   19.19   18.82      19      31      31      19   19.43   19.79
   20.54   23.94   26.07   24.96   24.46   25.96   25.93   27.18   26.79   27.22
    26.1   23.94   22.95   24.38   22.93   24.11   23.64   24.64   24.15   24.87
   22.35   22.85   21.49    21.9   22.43   21.69   22.43   23.26   22.43   22.79
   23.26   23.81   23.18   24.25    23.6   26.99   21.26   30.11   25.81    29.6
   24.27
                                                                                
                                           15.71   17.05    18.2   18.61   17.46
   17.19   15.55
                                                                                
                                                                                
                                                                                
                                                                                
                                                                                
        
    3496    3978    4230    4439    4577    4694    4939    5101    6007    6420
    6704    6848    6849    6928    7046    7047    7129    7211    7292    7293
    7393    7483    7484    7592    7718    7721    7821    7898    7898    7921
    8290    8290  8314.3 8315.23    8333    8333    8906    8906 9059.38 9080.78
 9347.23 9357.57  9371.2 9374.72 9550.52 9582.2510948.2411009.1911017.0411216.01
11234.9511518.4911557.0211727.2412387.9912901.8313612.8113641.4613663.3513675.59
13878.43 13947.713962.1214275.2714607.3114607.5314607.6114726.8314752.5314864.42
14877.3615006.3515109.5415223.0915395.8115447.5415465.4915489.2715522.3815569.12
15593.71
    23.5      24    23.3      22      20      18    16.1      16    14.6   15.81
   15.88   18.13   19.43   20.63   22.62   22.62      24    25.1   25.54   25.54
    25.2   23.64   23.64   21.43   18.22   18.37   16.65    16.3    28.3   28.27
      31      19   19.19   18.82      19      31      31      19   19.43   19.79
   20.54   23.94   26.07   24.96   24.46   25.96   25.93   27.18   26.79   27.22
    26.1   23.94   22.95   24.38   22.93   24.11   23.64   24.64   24.15   24.87
   22.35   22.85   21.49    21.9   22.43   21.69   22.43   23.26   22.43   22.79
   23.26   23.81   23.18   24.25    23.6   26.99   21.26   30.11   25.81    29.6
   24.27
                                                                                
                                           15.71   17.05    18.2   18.61   17.46
   17.19   15.55
                                                                                
                                                                                
                                                                                
                                                                                
                                                                                
        
Pier Skew, UpSta & Num, DnSta & Num=  ,7370, 2 ,7129, 2 , 0 , 0 , 0 ,,
     2.5     2.5
     -30      20
     2.5     2.5
     -30      20
Pier Skew, UpSta & Num, DnSta & Num=  ,7452, 2 ,7211, 2 , 0 , 0 , 0 ,,
     2.5     2.5
     -30      20
     2.5     2.5
     -30      20
Pier Skew, UpSta & Num, DnSta & Num=  ,7533, 2 ,7292, 2 , 0 , 0 , 0 ,,
     2.5     2.5
     -30      20
     2.5     2.5
     -30      20
Pier Skew, UpSta & Num, DnSta & Num=  ,7634, 2 ,7393, 2 , 0 , 0 , 0 ,,
     2.5     2.5
     -30      20
     2.5     2.5
     -30      20
Abutment Skew #Up #Dn= , 2 , 2
    7288    7315
      14       4
    7047    7070
      14       4
Abutment Skew #Up #Dn= , 2 , 2
    7710    7736
       4      14
    7460    7484
       4      14
BR Coef=-1 , 1 , 1 ,1.05, 0 ,,,.8,-1,1.2,0,
WSPro=,,,, 1 ,,,, 0 ,,,, 0 ,,,,-1 ,-1 ,-1 , 0 , 0 , 0 , 0 , 0
BC Design=,, 0 ,, 0 ,,,,,,
BC HTab HWMax=29.6

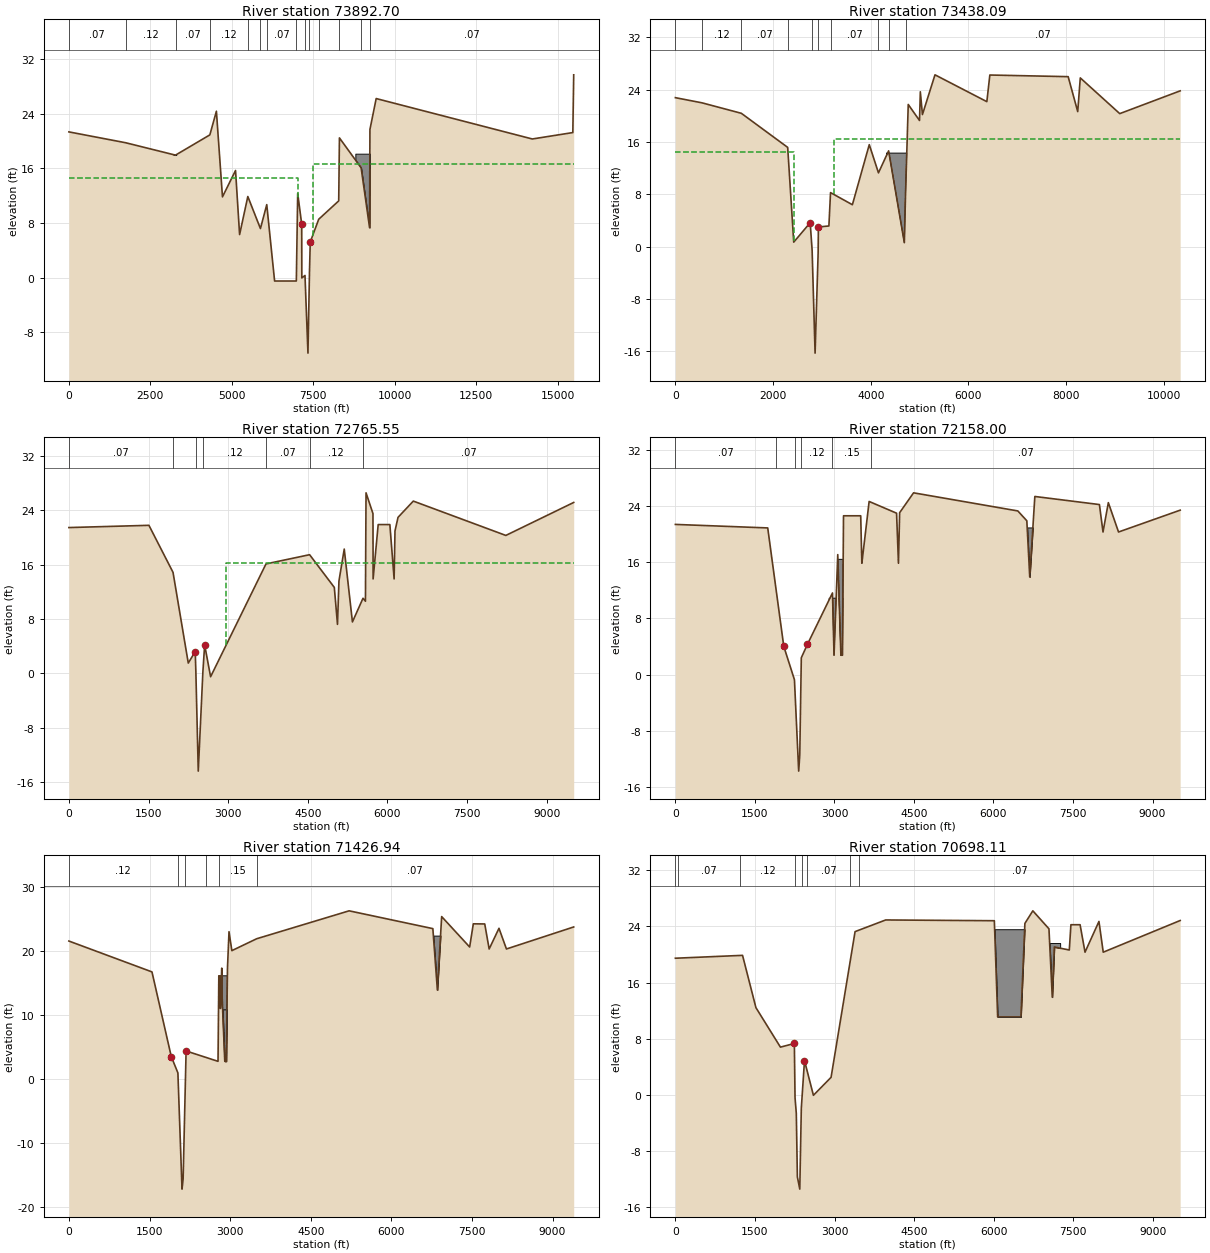
Type RM Length L Ch R = 1 ,73892.70,632.16,454.61,365.45
XS GIS Cut Line= 6
     3191109.976    13753995.679     3189433.562    13753609.356
     3188464.213    13752257.248     3189774.893     13748587.93
     3193947.838    13743858.269     3194799.011    13742334.264
#Sta/Elev= 30
       0   21.36 1740.43   19.77 3272.41   17.95 4326.93   20.92 4528.22   24.39
 4714.46   11.83 5115.48    15.7 5240.33     6.3 5492.65   11.88 5880.14    7.18
 6074.03   10.69 6315.06    -.51 6982.01    -.51 7023.96   12.34 7147.04    7.81
 7150.78    -.06 7247.86      .3 7338.94  -11.09 7385.81     .83 7409.63    5.21
 7669.71    8.55 8283.27   11.24 8305.21   20.48 8971.25   16.09 9230.75    7.31
 9241.79   21.72 9433.69   26.2514226.43   20.3215470.29   21.2615497.48   29.73
#Mann= 14 ,-1 , 0
       0     .07       0 1740.43     .12       0 3272.41     .07       0
 4326.93     .12       0 5492.65     .07       0 5880.14     .12       0
 6074.03     .07       0 6982.01     .12       0 7247.86    .035       0
 7385.81     .12       0 7669.71     .07       0 8283.27     .15       0
 8971.25     .12       0 9230.75     .07       0
#XS Ineff= 2 ,-1
       0    7047   14.61 7483.7315497.48   16.58
Permanent Ineff=
       F       F
#Block Obstruct= 2 ,-1
 1274.18  3640.5   18.03 8793.89 9404.58   18.17
Bank Sta=7147.04,7409.63
XS Rating Curve= 0
Vertical n Elevations= 2
       7      14
Vertical n for Station=0
     .07      .1
Vertical n for Station=1740.43
     .12     .24
Vertical n for Station=3272.41
     .07      .1
Vertical n for Station=4326.93
     .12     .24
Vertical n for Station=5492.65
     .07      .1
Vertical n for Station=5880.14
     .12     .24
Vertical n for Station=6074.03
     .07      .1
Vertical n for Station=6982.01
     .12     .24
Vertical n for Station=7247.86
    .035    .035
Vertical n for Station=7385.81
     .12     .24
Vertical n for Station=7669.71
     .07      .1
Vertical n for Station=8283.27
     .15     .15
Vertical n for Station=8971.25
     .12     .24
Vertical n for Station=9230.75
     .07      .1
Vertical n Flow= 0
Exp/Cntr=.5,.3

Type RM Length L Ch R = 1 ,73438.09,715.47,672.54,572.16
XS GIS Cut Line= 4
     3189912.369    13751648.116      3190109.77    13749105.316
      3190203.24    13748489.578     3194758.085    13742959.494
#Sta/Elev= 30
       0   22.76  545.39   21.97 1350.98   20.37 2300.24   15.16 2423.86     .68
 2760.91    3.65 2800.37    -.54 2861.15  -16.28 2923.59    -.98 2929.06       3
 3143.81    3.15 3177.56    8.25 3624.94     6.4 3970.78   15.58 4159.09   11.27
 4367.13   14.63 4689.01      .6 4713.69    8.12 4768.89   21.72 4999.88   19.27
 5016.28   23.66 5059.65   20.18  5316.7   26.25 6378.57   22.15 6439.91   26.22
 8043.91   25.97 8239.68   20.63 8292.06   25.78 9100.26   20.3210337.63    23.8
#Mann= 10 ,-1 , 0
       0     .07       0  545.39     .12       0 1350.98     .07       0
 2300.24     .12       0 2800.37    .035       0 2923.59     .12       0
 3177.56     .07       0 4159.09     .15       0 4367.13     .12       0
 4713.69     .07       0
#XS Ineff= 2 ,-1
 3242.0910337.63   16.49       0 2436.79   14.52
Permanent Ineff=
       F       F
#Block Obstruct= 1 ,-1
 4323.66    4800   14.29
Bank Sta=2760.91,2929.06
XS Rating Curve= 0
Vertical n Elevations= 2
       7      14
Vertical n for Station=0
     .07      .1
Vertical n for Station=545.39
     .12     .24
Vertical n for Station=1350.98
     .07      .1
Vertical n for Station=2300.24
     .12     .24
Vertical n for Station=2800.37
    .035    .035
Vertical n for Station=2923.59
     .12     .24
Vertical n for Station=3177.56
     .07      .1
Vertical n for Station=4159.09
     .15     .15
Vertical n for Station=4367.13
     .12     .24
Vertical n for Station=4713.69
     .07      .1
Vertical n Flow= 0
Exp/Cntr=.5,.3

Type RM Length L Ch R = 1 ,72765.55,361.1,607.55,810.18
XS GIS Cut Line= 4
     3190538.174    13751212.911     3190747.894    13749134.996
     3190896.295    13748452.352     3194831.524    13743001.459
#Sta/Elev= 30
       0   21.48 1507.44   21.81 1961.49   14.88 2248.78    1.51 2379.73     3.2
 2391.59      .3 2437.02  -14.42 2523.94      .2 2557.32    4.18 2669.38    -.51
  3712.9   16.12 4534.37   17.48 5000.01   12.66 5059.92    7.21 5087.37    13.6
 5187.06   18.31 5341.32    7.57 5540.67   11.06 5586.59   10.62 5597.72    26.6
 5728.19   23.54  5731.1   13.91 5826.67   21.92 6046.57   21.92  6126.7   13.91
 6143.06   20.98 6200.75   22.99 6488.33   25.38 8231.33   20.32 9510.02   25.18
#Mann= 7 ,-1 , 0
       0     .07       0 1961.49     .12       0 2391.59    .035       0
 2523.94     .12       0  3712.9     .07       0 4534.37     .12       0
 5540.67     .07       0
#XS Ineff= 2 ,-1
 2959.33 9510.02   16.27       0 1588.36   14.28
Permanent Ineff=
       F       F
Bank Sta=2379.73,2557.32
XS Rating Curve= 0
Vertical n Elevations= 2
       7      14
Vertical n for Station=0
     .07      .1
Vertical n for Station=1961.49
     .12     .24
Vertical n for Station=2391.59
    .035    .035
Vertical n for Station=2523.94
     .12     .24
Vertical n for Station=3712.9
     .07      .1
Vertical n for Station=4534.37
     .12     .24
Vertical n for Station=5540.67
     .07      .1
Vertical n Flow= 0
Exp/Cntr=.5,.3

Type RM Length L Ch R = 1 ,72158.00,1011.64,731.06,505.83
XS GIS Cut Line= 5
     3190906.669    13751368.568     3190990.717    13749652.902
     3191089.216    13749357.597     3191549.259    13748927.234
     3194936.436    13742959.494
#Sta/Elev= 30
       0    21.4 1741.95    20.9 2044.67    4.03 2245.77    -.72 2325.88  -13.74
 2346.23  -11.45 2375.28    2.41 2490.31    4.31 2963.35   11.64 2992.54    2.77
 3062.62    17.1 3121.96    2.77 3151.75    2.77 3171.16   22.63 3495.57   22.63
 3517.16   15.87 3654.46   24.67 4171.77      23  4207.8   15.87 4229.84   23.07
 4492.38    25.9 6458.86   23.32 6628.67   21.92 6683.81   13.91 6779.95   25.38
 7997.84   24.23 8065.64   20.32 8166.16    24.5 8358.51   20.32 9520.97   23.43
#Mann= 6 ,-1 , 0
       0     .07       0 1897.34     .12       0 2252.76    .035       0
 2377.77     .12       0 2957.31     .15       0 3694.04     .07       0
#Block Obstruct= 3 ,-1
 2900.76 3236.64   10.89 3061.32 5730.62   16.43 6503.82 6839.69   20.97
Bank Sta=2044.67,2490.31
XS Rating Curve= 0
Vertical n Elevations= 2
       7      14
Vertical n for Station=0
     .07      .1
Vertical n for Station=1915.3
     .12     .24
Vertical n for Station=2258.13
    .035    .035
Vertical n for Station=2386.47
     .12     .24
Vertical n for Station=2963.35
     .15     .15
Vertical n for Station=3711.82
     .07      .1
Vertical n Flow= 0
Exp/Cntr=.3,.1

Type RM Length L Ch R = 1 ,71426.94,826.67,728.82,571.45
XS GIS Cut Line= 4
     3191338.697    13751571.876     3191890.581     13749832.48
     3191905.421    13749283.397     3195007.982    13742986.625
#Sta/Elev= 30
       0   21.56 1545.78   16.74 1905.43     3.5  2028.3     .96 2104.96  -17.19
 2125.38  -15.63 2180.89    4.39 2774.93    2.77 2789.84   16.14 2811.29   16.05
 2819.35   11.03 2844.39   17.32 2851.79   12.71 2900.85    2.77  2929.3    2.77
 2951.04   17.37 2979.35   23.02 3032.26   20.06 3494.48   21.92 5214.37   26.28
 6772.61    23.5 6856.84   13.91 6936.62   25.38 7457.32   20.63 7525.58   24.25
 7738.11   24.23 7820.46   20.32 8003.22   23.55  8142.1   20.32 9393.76   23.76
#Mann= 6 ,-1 , 0
       0     .12       0 2022.95    .035       0 2169.02     .12       0
 2556.23     .07       0 2798.31     .15       0 3494.48     .07       0
#Block Obstruct= 3 ,-1
 2790.36 3189.71   16.13 2854.96 3007.63   10.89 6656.49 6916.03   22.41
Bank Sta=1905.43,2180.89
XS Rating Curve= 0
Vertical n Elevations= 2
       7      14
Vertical n for Station=0
     .12     .24
Vertical n for Station=2028.3
    .035    .035
Vertical n for Station=2169.13
     .12     .24
Vertical n for Station=2566.45
     .07      .1
Vertical n for Station=2811.29
     .15     .15
Vertical n for Station=3494.48
     .07      .1
Vertical n Flow= 0
Exp/Cntr=.3,.1

Type RM Length L Ch R = 1 ,70698.11,255.3,543.7,191.8
XS GIS Cut Line= 5
     3192021.682    13751679.883     3192714.206    13749713.759
     3192409.984    13749268.557      3193578.05    13746388.128
     3195137.975    13742943.293
#Sta/Elev= 30
       0   19.46 1265.94   19.87 1518.24   12.42  1980.1     6.8 2242.37    7.32
 2255.07    -.38 2279.15   -2.64 2299.19  -11.68 2344.73  -13.42  2373.5   -1.89
 2433.53    4.88 2601.66    -.06 2934.44     2.5 3386.73   23.25 3963.92   24.91
 6011.28    24.8 6073.97    11.1 6512.68    11.1 6587.17   24.42  6736.8   26.21
  7040.6   23.65 7103.32   13.91 7142.48   21.06 7424.04   20.63 7454.58   24.23
 7627.48   24.23 7720.33   20.32 7982.79    24.7 8063.61   20.32 9513.56   24.83
#Mann= 8 ,-1 , 0
       0     .12       0   51.56     .07       0 1211.55     .12       0
 2258.33    .035       0 2391.71     .12       0 2489.79     .07       0
 3282.27     .15       0 3465.89     .07       0
#Block Obstruct= 2 ,-1
 5832.06 6641.22   23.59 6992.37 7251.91   21.62
Bank Sta=2242.37,2433.53
XS Rating Curve= 0
Vertical n Elevations= 2
       7      14
Vertical n for Station=0
     .12     .24
Vertical n for Station=57.19
     .07      .1
Vertical n for Station=1231.5
     .12     .24
Vertical n for Station=2265.15
    .035    .035
Vertical n for Station=2391.92
     .12     .24
Vertical n for Station=2503.85
     .07      .1
Vertical n for Station=3303.62
     .15     .15
Vertical n for Station=3565.02
     .07      .1
Vertical n Flow= 0
Exp/Cntr=.3,.1

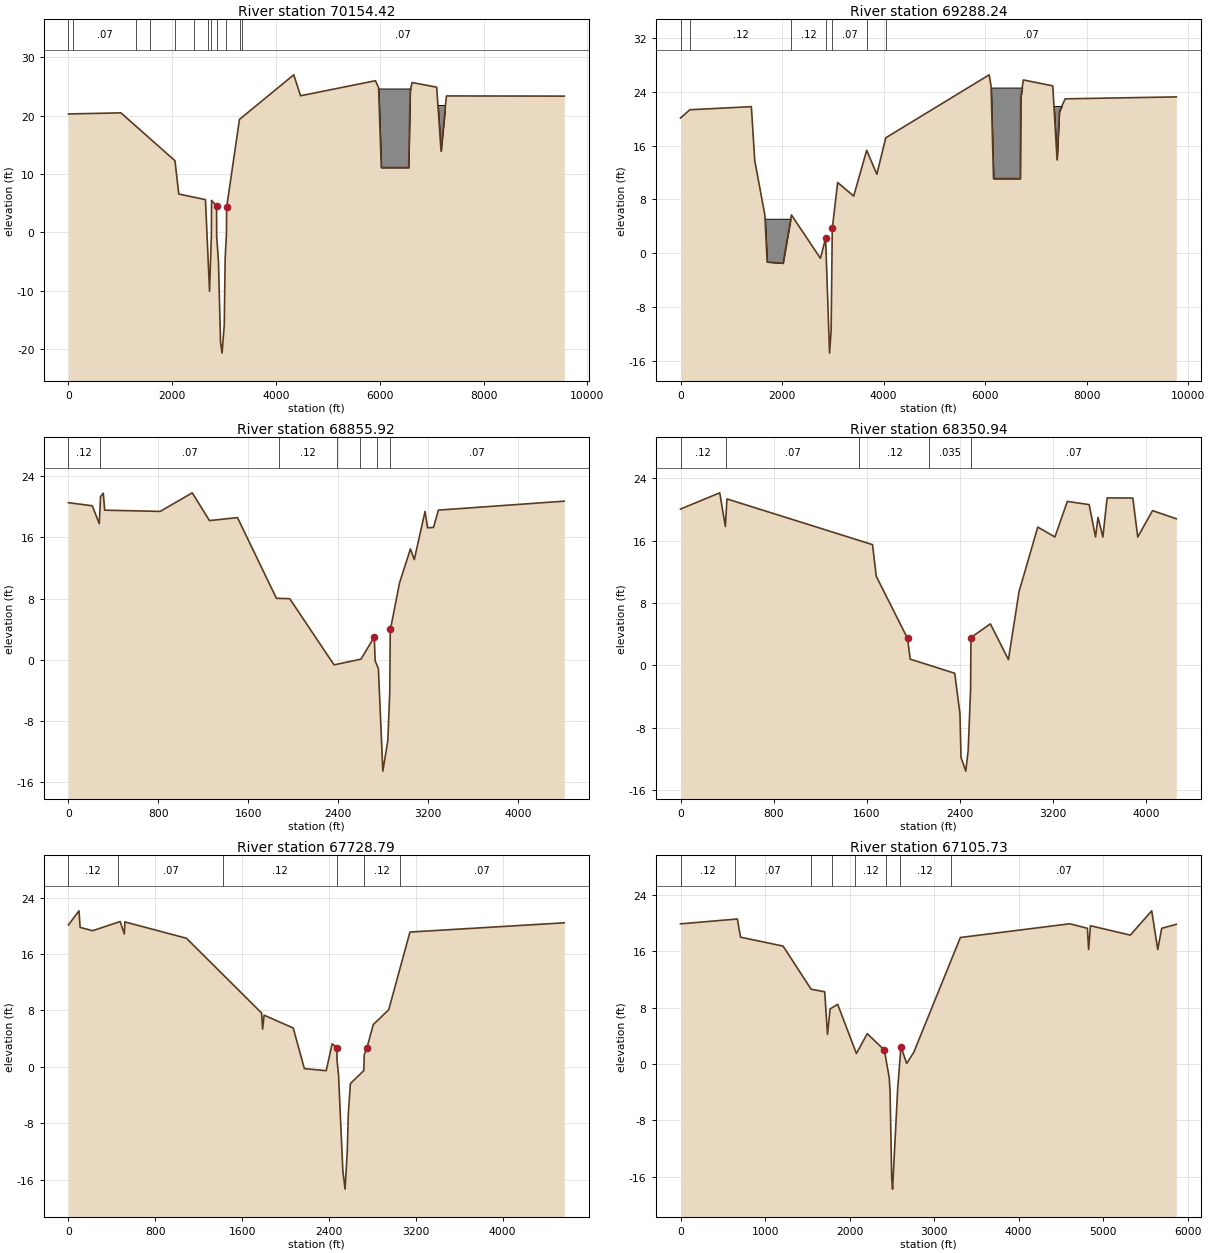
Type RM Length L Ch R = 1 ,70154.42,157.03,866.18,1038.88
XS GIS Cut Line= 6
     3192224.989    13751813.303     3192940.304    13749817.656
     3192795.826    13749402.117     3192766.146    13748808.514
     3193621.381    13746518.122     3195267.969    13742921.628
#Sta/Elev= 30
       0   20.29 1011.11   20.48 2052.62   12.27 2126.51    6.56 2640.17     5.6
 2718.86  -10.11 2754.23    -.54 2758.13    5.47 2853.92     4.5 2856.69    -.69
 2890.86   -4.99 2931.23  -18.92 2960.11  -20.72 3002.94  -15.85  3020.3   -4.41
 3044.69    -.28 3048.33    4.26 3296.04   19.36 4342.29      27 4472.94   23.41
 5916.04   25.99  5976.9    24.8 6028.93    11.1 6556.44    11.1 6586.41   24.29
 6622.36   25.68 7096.75   24.88 7180.69   13.91 7283.97   23.38 9554.62   23.35
#Mann= 12 ,-1 , 0
       0     .12       0   95.64     .07       0 1306.59     .12       0
 1573.07     .07       0 2052.62     .12       0 2410.92     .07       0
 2682.46    .035       0 2737.49     .12       0 2863.33    .035       0
 3042.76     .07       0 3312.68     .12       0 3340.77     .07       0
#Block Obstruct= 2 ,-1
 5847.33 6687.02   24.66  6931.3 7251.91   21.83
Bank Sta=2853.92,3048.33
XS Rating Curve= 0
Vertical n Elevations= 2
       7      14
Vertical n for Station=0
     .12     .24
Vertical n for Station=98.43
     .07      .1
Vertical n for Station=1329.81
     .12     .24
Vertical n for Station=1595.29
     .07      .1
Vertical n for Station=2052.62
     .12     .24
Vertical n for Station=2432.59
     .07      .1
Vertical n for Station=2689.74
    .035    .035
Vertical n for Station=2741.31
     .12     .24
Vertical n for Station=2865.17
    .035    .035
Vertical n for Station=3044.69
     .07      .1
Vertical n for Station=3312.78
     .12     .24
Vertical n for Station=3390.19
     .07      .1
Vertical n Flow= 0
Exp/Cntr=.3,.1

Type RM Length L Ch R = 1 ,69288.24,200.71,432.32,512.81
XS GIS Cut Line= 5
     3192336.173      13751949.9     3193200.526    13749509.224
     3193597.191    13749194.356     3193681.696    13746550.039
     3195376.297    13742899.962
#Sta/Elev= 30
       0    20.1  184.44   21.33 1395.82   21.79 1461.95    13.8 1661.47    5.68
 1706.62    -1.3 2019.81   -1.48 2184.62     5.7  2756.7    -.75 2857.54    2.22
  2871.8     -.8 2935.88  -14.84 2966.68  -11.53 2989.78    3.69 3095.65   10.52
 3410.96     8.5 3667.31    15.3 3867.02   11.74 4043.28   17.16 6079.96   26.52
  6117.1   24.85 6165.82    11.1 6692.08    11.1 6701.82    23.1 6752.72   25.76
  7332.4   24.88 7417.38   13.91 7462.94   21.06 7577.16   22.95 9765.58   23.24
#Mann= 7 ,-1 , 0
       0     .12       0  184.44     .12       0 2184.62     .12       0
  2871.8    .035       0 2989.78     .07       0 3667.31     .12       0
 4043.28     .07       0
#Block Obstruct= 3 ,-1
 1587.79 2229.01    5.13 5984.73 6778.63   24.63 7190.84 7587.79   21.88
Bank Sta=2857.54,2989.78
XS Rating Curve= 0
Vertical n Elevations= 2
       6      13
Vertical n for Station=0
     .12     .24
Vertical n for Station=184.44
     .12     .24
Vertical n for Station=2184.62
     .12     .24
Vertical n for Station=2871.8
    .035    .035
Vertical n for Station=2989.78
     .07      .1
Vertical n for Station=3667.31
     .12     .24
Vertical n for Station=4043.28
     .07      .1
Vertical n Flow= 0
Exp/Cntr=.3,.1

Type RM Length L Ch R = 1 ,68855.92,367.9,504.98,293.81
XS GIS Cut Line= 4
     3192437.826    13752102.381     3193314.347    13749774.806
     3193869.225    13749642.015     3194313.252     13748362.33
#Sta/Elev= 30
       0   20.54  211.92   20.14  274.35    17.8  285.43   21.33  309.72   21.79
   322.8   19.56  816.27    19.4 1101.58   21.83 1255.09    18.2 1504.15   18.59
 1851.09    8.04 1969.39    7.99 2363.65    -.66 2603.85     .09 2721.91    3.01
 2729.49    -.13  2758.4   -1.16 2797.91  -14.55 2842.17  -10.56 2859.36   -4.22
 2863.99       4 2865.42    3.97 2946.55   10.06 3043.61    14.5  3077.8    13.1
 3173.51    19.4 3195.82   17.26 3248.84   17.31 3292.49   19.57 4412.22   20.74
#Mann= 7 ,-1 , 0
       0     .12       0  279.56     .07       0 1874.05     .12       0
  2386.7    .035       0 2591.03     .12       0 2748.02    .035       0
  2857.4     .07       0
Bank Sta=2721.91,2865.42
XS Rating Curve= 0
Vertical n Elevations= 2
       5      12
Vertical n for Station=0
     .12     .24
Vertical n for Station=285.43
     .07      .1
Vertical n for Station=1928.72
     .12     .24
Vertical n for Station=2394.55
    .035    .035
Vertical n for Station=2603.85
     .12     .24
Vertical n for Station=2754.58
    .035    .035
Vertical n for Station=2859.36
     .07      .1
Vertical n Flow= 0
Exp/Cntr=.3,.1

Type RM Length L Ch R = 1 ,68350.94,570.91,622.15,478.64
XS GIS Cut Line= 4
     3192517.243    13752251.684     3193508.791    13750358.139
     3193953.353    13750025.401     3194519.849    13748563.139
#Sta/Elev= 30
       0   20.03  337.22   22.11  385.55    17.8  399.09   21.33 1650.44   15.47
  1682.2   11.42 1951.04    3.46 1974.15      .8 2356.79   -1.01 2401.82   -6.22
 2410.69  -11.79 2451.66  -13.55 2472.22  -10.92 2493.21   -3.03 2496.09    3.57
 2663.07    5.32 2818.32     .74  2909.1    9.43 3070.55   17.72 3217.75   16.45
 3324.73   21.01  3511.9    20.6 3566.96   16.45 3588.13   18.96 3630.07   16.45
 3666.43   21.46 3887.29   21.44 3929.74   16.45 4056.72   19.83  4260.9   18.79
#Mann= 5 ,-1 , 0
       0     .12       0  387.53     .07       0 1537.55     .12       0
 2139.27    .035       0 2495.78     .07       0
Bank Sta=1951.04,2496.09
XS Rating Curve= 0
Vertical n Elevations= 2
       5      12
Vertical n for Station=0
     .12     .24
Vertical n for Station=399.09
     .07      .1
Vertical n for Station=1540.04
     .12     .24
Vertical n for Station=2141.24
    .035    .035
Vertical n for Station=2496.09
     .07      .1
Vertical n Flow= 0
Exp/Cntr=.3,.1

Type RM Length L Ch R = 1 ,67728.79,481.95,623.06,694.91
XS GIS Cut Line= 4
     3192637.957    13752353.338     3194220.475    13750589.324
     3194376.676    13750206.378     3194941.574     13748512.75
#Sta/Elev= 30
       0   20.11   97.13   22.11  107.44   19.76   222.6   19.29  476.37   20.59
  514.77   18.83  519.87   20.54 1087.17   18.22 1779.74    7.62 1789.11    5.33
 1802.83    7.31 2071.42    5.49 2173.99    -.27 2375.31    -.56 2430.08    3.25
 2473.94    2.71 2474.91     .94 2489.02   -1.21 2528.65  -14.76 2549.16  -17.36
 2569.09  -12.06 2578.95   -6.76 2598.17   -2.39 2721.88    -.54 2725.78    1.67
 2750.37    2.67 2809.13    5.98 2951.46    8.08 3146.93    19.1 4568.77   20.41
#Mann= 6 ,-1 , 0
       0     .12       0  458.11     .07       0 1423.81     .12       0
 2473.35    .035       0 2722.71     .12       0 3056.23     .07       0
Bank Sta=2473.94,2750.37
XS Rating Curve= 0
Vertical n Elevations= 2
       5      12
Vertical n for Station=0
     .12     .24
Vertical n for Station=461.87
     .07      .1
Vertical n for Station=1441.34
     .12     .24
Vertical n for Station=2473.94
    .035    .035
Vertical n for Station=2725.78
     .12     .24
Vertical n for Station=3093.6
     .07      .1
Vertical n Flow= 0
Exp/Cntr=.3,.1

Type RM Length L Ch R = 1 ,67105.73,458.41,466.18,371.51
XS GIS Cut Line= 4
     3192853.971    13752626.532     3194400.389    13751045.807
     3194858.598    13750752.565      3195547.46    13747719.722
#Sta/Elev= 30
       0    19.9  672.84   20.59  710.07   18.01 1213.55   16.74 1544.84   10.62
 1705.82   10.25 1739.04     4.2 1769.68    7.82 1859.49    8.47 2081.06    1.48
 2209.02     4.3 2411.43    1.99 2469.57   -1.96 2479.22   -3.93 2498.85  -16.32
  2508.9  -17.78 2569.46   -3.48 2608.16    2.43 2676.15     .07 2759.64    1.65
 3310.95   17.96 4605.48   19.91 4813.78   19.27 4828.32   16.26 4850.18   19.63
 5321.38    18.3 5574.85   21.75 5646.15   16.26 5693.07   19.27 5865.46   19.83
#Mann= 8 ,-1 , 0
       0     .12       0  646.08     .07       0 1544.84     .12       0
 1797.23     .07       0  2065.4     .12       0 2434.87    .035       0
  2596.4     .12       0 3196.26     .07       0
Bank Sta=2411.43,2608.16
XS Rating Curve= 0
Vertical n Elevations= 2
       5      12
Vertical n for Station=0
     .12     .24
Vertical n for Station=655.39
     .07      .1
Vertical n for Station=1544.84
     .12     .24
Vertical n for Station=1808.74
     .07      .1
Vertical n for Station=2073.43
     .12     .24
Vertical n for Station=2439.95
    .035    .035
Vertical n for Station=2601.45
     .12     .24
Vertical n for Station=3218.2
     .07      .1
Vertical n Flow= 0
Exp/Cntr=.3,.1

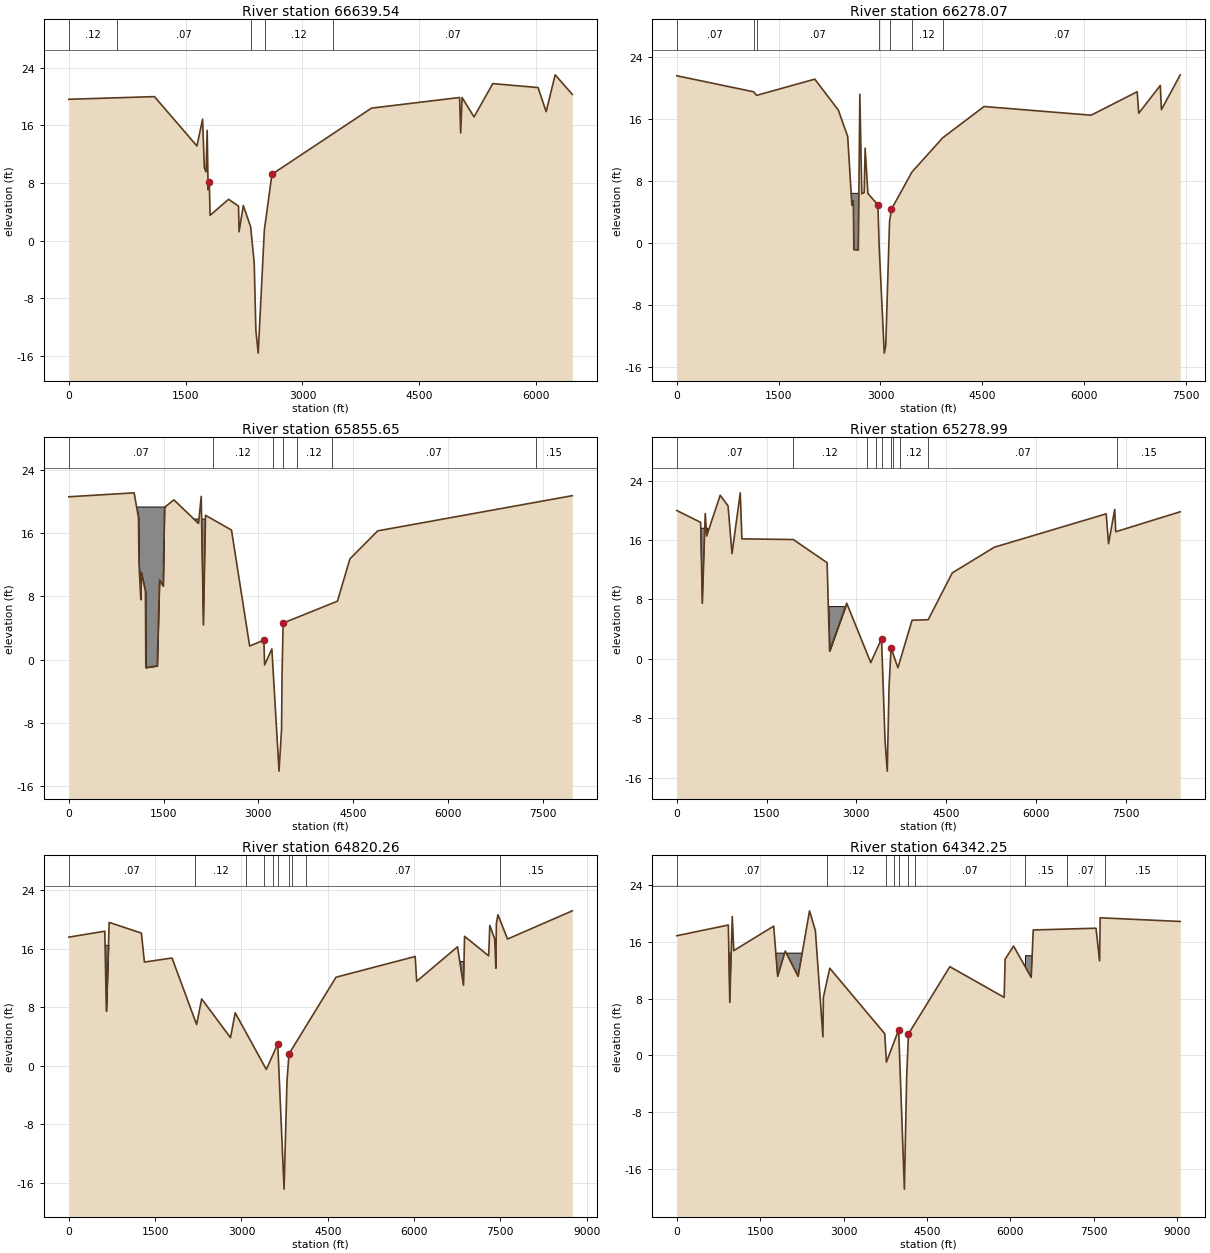
Type RM Length L Ch R = 1 ,66639.54,520.32,361.48,244.87
XS GIS Cut Line= 4
     3193240.182    13753071.056     3194695.357    13751361.009
       3195081.2    13751212.608     3196061.265    13747535.528
#Sta/Elev= 30
       0   19.64 1099.31   20.01 1644.71   13.15 1717.62   16.88  1739.2   10.12
 1761.62    9.55 1775.95   15.32  1788.5    7.08 1803.73     8.2 1813.23    3.51
  2050.7    5.73 2178.55     4.8 2185.59    1.22 2239.94    4.86 2334.31    1.92
 2380.11   -3.11 2401.43  -12.49 2431.37  -15.65 2510.44    1.48 2607.64    9.21
 3886.01   18.41 5016.92   19.89 5031.16   14.96 5048.53   19.89 5202.54   17.19
 5443.26   21.82 6024.53   21.27  6128.4   17.92 6244.25   23.04 6464.24   20.32
#Mann= 5 ,-1 , 0
       0     .12       0  616.95     .07       0 2338.12    .035       0
 2513.82     .12       0 3391.53     .07       0
Bank Sta=1803.73,2607.64
XS Rating Curve= 0
Vertical n Elevations= 2
       5      12
Vertical n for Station=0
     .12     .24
Vertical n for Station=620
     .07      .1
Vertical n for Station=2343.82
    .035    .035
Vertical n for Station=2522.24
     .12     .24
Vertical n for Station=3437.13
     .07      .1
Vertical n Flow= 0
Exp/Cntr=.3,.1

Type RM Length L Ch R = 1 ,66278.07,701.3,422.42,292.93
XS GIS Cut Line= 4
     3193337.126    13754108.361     3194945.781    13751705.021
     3195254.047    13751415.726     3196487.821    13747506.445
#Sta/Elev= 30
       0   21.64 1132.11   19.57 1175.54   19.11 2032.66    21.2 2378.81   17.22
 2516.87   13.81  2578.9    4.93 2600.33    5.52 2607.22     -.8 2673.37    -.84
    2696   19.24 2724.53    6.41 2759.66    6.57 2774.02    12.3 2814.42    6.45
  2961.9    4.98 2980.49    -.38 3055.58  -14.15 3077.22  -13.22 3133.33    2.84
 3161.94    4.42 3463.19    9.22 3917.03   13.64 4525.24   17.67 6102.01   16.55
 6780.18   19.58 6802.78    16.8 7120.61   20.39  7137.1   17.27 7414.13   21.76
#Mann= 7 ,-1 , 0
       0     .07       0 1132.11     .12       0 1175.54     .07       0
 2980.49    .035       0 3133.33     .07       0 3463.19     .12       0
 3917.03     .07       0
#Block Obstruct= 2 ,-1
 2454.96 2760.31    6.47 4051.98 4197.73   14.44
Bank Sta=2961.9,3161.94
XS Rating Curve= 0
Vertical n Elevations= 2
       5      12
Vertical n for Station=0
     .07      .1
Vertical n for Station=1132.11
     .12     .24
Vertical n for Station=1175.54
     .07      .1
Vertical n for Station=2980.49
    .035    .035
Vertical n for Station=3133.33
     .07      .1
Vertical n for Station=3463.19
     .12     .24
Vertical n for Station=3917.03
     .07      .1
Vertical n Flow= 0
Exp/Cntr=.3,.1

Type RM Length L Ch R = 1 ,65855.65,670.11,576.66,415.5
XS GIS Cut Line= 4
     3194364.738     13755000.25     3195274.121    13752132.694
     3195512.149    13751556.854     3196846.515    13747428.889
#Sta/Elev= 30
       0   20.58 1033.58   21.08 1102.25   17.97 1110.32   12.19 1139.49    7.59
  1146.5   11.01 1212.56    8.63 1218.52   -1.02 1399.26     -.8 1435.26   10.06
 1493.41    9.29    1514   19.24 1663.03   20.19  2052.8   17.21 2095.54   20.63
 2130.76    4.37 2163.51   18.24 2574.78   16.37 2862.11    1.71 3087.12    2.45
 3099.46    -.68 3213.79    1.34 3327.34  -14.11 3367.12   -8.79 3375.23   -1.78
 3392.02    4.61 4251.47    7.38 4449.86   12.73 4889.49   16.27 7969.67   20.72
#Mann= 7 ,-1 , 0
       0     .07       0 2279.64     .12       0 3224.85    .035       0
 3391.17     .07       0 3607.31     .12       0 4165.35     .07       0
 7388.52     .15       0
#Block Obstruct= 2 ,-1
 1013.74 1551.15   19.35 1941.98 2186.26   17.77
Bank Sta=3087.12,3392.02
XS Rating Curve= 0
Vertical n Elevations= 2
       5      12
Vertical n for Station=0
     .07      .1
Vertical n for Station=2574.78
     .12     .24
Vertical n for Station=3232.15
    .035    .035
Vertical n for Station=3392.02
     .07      .1
Vertical n for Station=3611.35
     .12     .24
Vertical n for Station=4203
     .07      .1
Vertical n for Station=7484.46
     .15     .15
Vertical n Flow= 0
Exp/Cntr=.3,.1

Type RM Length L Ch R = 1 ,65278.99,523.85,458.73,449.36
XS GIS Cut Line= 4
     3195043.349    13755310.472       3195951.2    13752112.879
     3195947.685    13751644.887     3197108.265    13747176.833
#Sta/Elev= 30
       0   19.97  398.97   18.37  427.08    7.47  475.47   19.57  499.48   16.55
  725.58   22.02  856.47   20.59  922.86   14.16 1060.32   22.35 1088.14   16.15
 1946.19   16.06 2510.45   12.94 2552.14    1.05 2837.61    7.49 3239.51    -.51
 3419.97    2.69 3478.43  -11.05 3515.11  -15.13 3545.04   -3.79 3579.19    1.45
 3692.73   -1.21 3929.77    5.19 4198.77    5.26 4601.34   11.57 5304.54   15.03
 7171.58   19.52 7211.11   15.49 7313.63   20.11 7331.41   17.11  8408.3    19.8
#Mann= 10 ,-1 , 0
       0     .07       0 1946.19     .12       0 3172.87     .07       0
 3325.15     .12       0 3432.77    .035       0 3575.38     .12       0
 3617.59     .07       0 3726.56     .12       0 4198.77     .07       0
 7347.68     .15       0
#Block Obstruct= 2 ,-1
  305.34  519.08   17.58 2458.02 2854.96    7.09
Bank Sta=3419.97,3579.19
XS Rating Curve= 0
Vertical n Elevations= 2
       5      12
Vertical n for Station=0
     .07      .1
Vertical n for Station=1946.19
     .12     .24
Vertical n for Station=3178.26
     .07      .1
Vertical n for Station=3330.63
     .12     .24
Vertical n for Station=3441.35
    .035    .035
Vertical n for Station=3575.66
     .12     .24
Vertical n for Station=3626.19
     .07      .1
Vertical n for Station=3733.29
     .12     .24
Vertical n for Station=4198.77
     .07      .1
Vertical n for Station=7398.15
     .15     .15
Vertical n Flow= 0
Exp/Cntr=.3,.1

Type RM Length L Ch R = 1 ,64820.26,526.17,478,456.24
XS GIS Cut Line= 4
      3195547.46    13755581.917     3196411.227    13752231.443
     3196406.484    13751747.703     3197331.238    13747031.417
#Sta/Elev= 30
       0   17.56  624.91   18.37  651.97    7.47  700.98   19.57 1260.85   18.11
 1313.54   14.16 1793.22   14.71 2220.75    5.64 2308.66    9.13 2809.34    3.84
 2891.31    7.23 3431.82    -.49 3630.94    2.98 3740.63  -16.83  3791.3   -2.12
 3825.82    1.62 4643.05   12.09 6018.74   14.92 6045.61   11.53 6754.71   16.24
 6859.02   10.99 6877.11   17.67 7296.27   15.01 7315.95   19.17 7401.38    17.3
 7421.23   13.32 7429.86   19.39 7457.25   20.62 7623.82    17.3 8749.88   21.15
#Mann= 10 ,-1 , 0
       0     .07       0 2194.38     .12       0  3087.4     .07       0
  3392.5    .035       0 3551.75     .12       0 3630.94    .035       0
 3820.46     .07       0 3876.72     .12       0 4113.23     .07       0
 7492.44     .15       0
#Block Obstruct= 2 ,-1
  534.35  717.56   16.52 6651.99 7754.05   14.22
Bank Sta=3630.94,3825.82
XS Rating Curve= 0
Vertical n Elevations= 2
       5      12
Vertical n for Station=0
     .07      .1
Vertical n for Station=2220.75
     .12     .24
Vertical n for Station=3091.59
     .07      .1
Vertical n for Station=3393.9
    .035    .035
Vertical n for Station=3559.07
     .12     .24
Vertical n for Station=3630.94
    .035    .035
Vertical n for Station=3822.27
     .07      .1
Vertical n for Station=3877.35
     .12     .24
Vertical n for Station=4137.21
     .07      .1
Vertical n for Station=7504.33
     .15     .15
Vertical n Flow= 0
Exp/Cntr=.3,.1

Type RM Length L Ch R = 1 ,64342.25,671.38,506.18,486.11
XS GIS Cut Line= 4
     3196129.126    13755940.611     3196891.691    13752132.694
     3196878.992    13751705.121     3197476.654    13747002.333
#Sta/Elev= 30
       0   16.86  927.28   18.37   952.9    7.47  997.68   19.57 1024.64   14.76
 1742.61   18.21 1814.03   11.13 1950.34    14.7 2181.99   11.13 2386.73   20.37
 2491.96   17.59 2627.84     2.6 2635.78    8.18  2750.7   12.28 3739.26    3.05
 3769.24    -.96 3989.38     3.6 4092.34  -18.86 4133.03   -3.14 4165.27    3.01
 4909.66    12.5 5885.99    8.17 5903.75   13.56 6055.73    15.4 6372.35   10.99
 6408.92   17.67  7537.8   17.92 7601.74   13.32 7611.98   19.39 9051.89   18.87
#Mann= 10 ,-1 , 0
       0     .07       0 2705.34     .12       0 3757.98    .035       0
 3907.43     .12       0 4000.94    .035       0 4164.23     .12       0
 4288.97     .07       0 6260.11     .15       0 7010.24     .07       0
 7696.92     .15       0
#Block Obstruct= 2 ,-1
  705.35 2354.95   14.41 6269.41 7734.92   14.04
Bank Sta=3989.38,4165.27
XS Rating Curve= 0
Vertical n Elevations= 2
       5      12
Vertical n for Station=0
     .07      .1
Vertical n for Station=2706.38
     .12     .24
Vertical n for Station=3769.24
    .035    .035
Vertical n for Station=3910.63
     .12     .24
Vertical n for Station=4011.19
    .035    .035
Vertical n for Station=4164.56
     .12     .24
Vertical n for Station=4295.02
     .07      .1
Vertical n for Station=6270.57
     .15     .15
Vertical n for Station=7017.08
     .07      .1
Vertical n for Station=7732.2
     .15     .15
Vertical n Flow= 0
Exp/Cntr=.3,.1

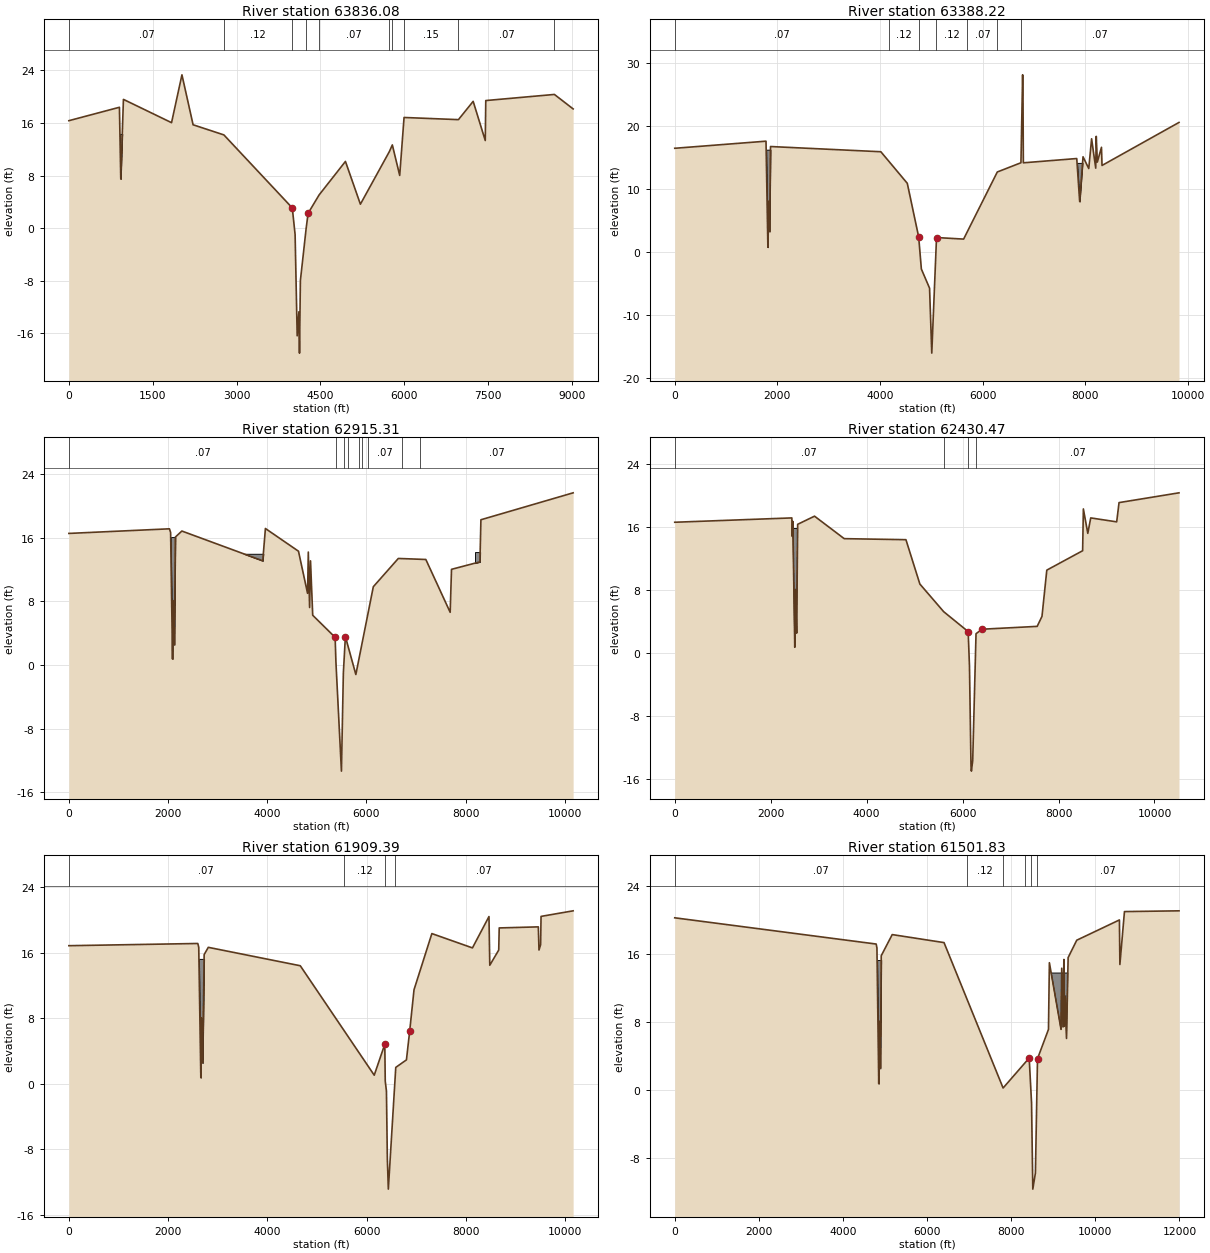
Type RM Length L Ch R = 1 ,63836.08,510.57,447.85,453.9
XS GIS Cut Line= 4
      3197030.71    13756008.472     3197396.254    13752132.694
     3197381.414     13751568.77     3197680.238    13747012.028
#Sta/Elev= 30
       0   16.33  904.61   18.37  928.66    7.47  976.19   19.57 1837.19   16.03
 2023.39    23.3 2222.82   15.71  2773.9   14.17 3998.61    3.07 4000.71    2.85
 4048.36    -.98 4085.68  -16.36 4116.61   -12.7 4126.89  -18.99 4142.83   -7.97
 4246.18    -.01 4281.06    2.26  4477.9    5.05 4949.16   10.14 5216.65    3.64
 5734.76   11.63 5788.29   12.65 5920.02    8.01 5997.95   16.82 6971.14   16.49
 7234.63   19.27 7451.17   13.32 7460.46   19.39 8688.42   20.32 9023.62   18.12
#Mann= 10 ,-1 , 0
       0     .07       0  2773.9     .12       0 4000.71    .035       0
 4246.18     .12       0  4477.9     .07       0 5734.76     .12       0
 5788.29     .07       0 5997.95     .15       0 6971.14     .07       0
 8688.42     .15       0
#Block Obstruct= 1 ,-1
  614.33 1171.79   14.31
Bank Sta=3998.61,4281.06
XS Rating Curve= 0
Vertical n Elevations= 2
       5      12
Vertical n for Station=0
     .07      .1
Vertical n for Station=2773.9
     .12     .24
Vertical n for Station=4000.71
    .035    .035
Vertical n for Station=4246.18
     .12     .24
Vertical n for Station=4477.9
     .07      .1
Vertical n for Station=5734.76
     .12     .24
Vertical n for Station=5788.29
     .07      .1
Vertical n for Station=5997.95
     .15     .15
Vertical n for Station=6971.14
     .07      .1
Vertical n for Station=8688.42
     .15     .15
Vertical n Flow= 0
Exp/Cntr=.3,.1

Type RM Length L Ch R = 1 ,63388.22,453.91,472.92,365.15
XS GIS Cut Line= 4
     3197134.661    13756888.339     3197856.296    13752444.336
     3197826.616    13751628.131     3197980.765    13747128.361
#Sta/Elev= 30
       0   16.48 1777.62   17.61 1814.06     .75 1826.19    8.07 1847.49    3.24
 1865.21   16.76 4014.25   15.93  4529.4   10.91 4751.18    2.38 4803.46   -2.72
    4963   -5.76 5006.03  -16.09 5098.61    2.29 5626.18    2.04 6282.43   12.71
 6742.94   14.18  6775.7   28.16 6783.18   24.38 6789.71   14.17  7829.7   14.85
  7886.9    8.01  7951.9   15.13 8063.93   13.26 8118.95   17.99 8199.53   13.32
 8209.56   18.38 8230.69   14.28 8311.28   16.64    8322   13.75 9821.37   20.59
#Mann= 7 ,-1 , 0
       0     .07       0 4177.22     .12       0 4751.18    .035       0
  5091.4     .12       0 5700.52     .07       0 6282.43     .12       0
 6749.24     .07       0
#Block Obstruct= 2 ,-1
 1694.66 1938.93   16.26 7786.26  7954.2   14.16
Bank Sta=4751.18,5098.61
XS Rating Curve= 0
Vertical n Elevations= 2
       5      12
Vertical n for Station=0
     .07      .1
Vertical n for Station=4232.11
     .12     .24
Vertical n for Station=4751.18
    .035    .035
Vertical n for Station=5096.52
     .12     .24
Vertical n for Station=5718.19
     .07      .1
Vertical n for Station=6282.43
     .12     .24
Vertical n for Station=6768.77
     .07      .1
Vertical n Flow= 0
Exp/Cntr=.3,.1

Type RM Length L Ch R = 1 ,62915.31,349.99,484.84,440.13
XS GIS Cut Line= 4
     3197237.632    13757162.928     3198375.699    13752088.173
     3198194.868     13751538.32     3198232.821     13747147.75
#Sta/Elev= 30
       0   16.56 2027.84   17.14 2051.78   16.69  2090.6     .75 2104.25    8.07
  2127.7    2.54 2147.45    16.1 2279.23   16.86 3910.45   13.11 3963.93   17.18
 4630.99   14.32 4814.04    9.02 4829.08   14.21 4855.08    7.24 4873.53   13.11
 4917.92    6.26 5369.98    3.48 5386.22     .35 5497.13  -13.36 5536.02      -1
 5576.85    3.58 5787.92    -1.2 6140.18    9.85 6644.72   13.41 7199.54   13.28
 7690.41    6.63 7717.27   12.04 8290.51   12.98  8310.4   18.2810170.36   21.67
#Mann= 9 ,-1 , 0
       0     .07       0 5386.22    .035       0 5553.01     .12       0
 5621.26    .035       0 5851.62     .07       0 5902.47     .12       0
 6031.73     .07       0 6727.08     .12       0 7088.64     .07       0
#Block Obstruct= 3 ,-1
 1923.66 2290.08    16.1 3360.97 4279.42      14 8191.13 8436.86   14.21
Bank Sta=5369.98,5576.85
XS Rating Curve= 0
Vertical n Elevations= 2
       5      12
Vertical n for Station=0
     .07      .1
Vertical n for Station=5386.22
    .035    .035
Vertical n for Station=5562.71
     .12     .24
Vertical n for Station=5635.19
    .035    .035
Vertical n for Station=5888.16
     .07      .1
Vertical n for Station=5938
     .12     .24
Vertical n for Station=6039.46
     .07      .1
Vertical n for Station=7028.41
     .12     .24
Vertical n for Station=7199.54
     .07      .1
Vertical n Flow= 0
Exp/Cntr=.3,.1

Type RM Length L Ch R = 1 ,62430.47,229.3,521.08,655.57
XS GIS Cut Line= 4
     3197374.927    13757574.813     3198796.725    13751861.524
     3198598.301    13751286.809     3198885.326     13747280.96
#Sta/Elev= 30
       0   16.59 2440.99   17.14 2450.83    14.8 2461.58   16.69 2502.18     .75
 2514.95    8.07    2541    2.54 2562.67   16.33 2914.05   17.36 3532.85   14.51
  4819.3   14.38 5109.57    8.76 5606.51    5.25 6116.72    2.73 6143.85   -1.63
 6175.56  -14.27  6183.9  -14.96 6211.05  -13.66 6280.56    2.46  6407.7    3.03
  7555.3    3.39 7655.53    4.66 7755.81   10.52 8502.83   12.98 8518.12   18.28
 8610.48   15.18 8671.38   17.14 9212.86   16.64 9261.67   19.0810511.67   20.32
#Mann= 4 ,-1 , 0
       0     .07       0 5606.51     .12       0 6123.26    .035       0
 6272.84     .07       0
#Block Obstruct= 1 ,-1
 2271.76 2619.85   15.79
Bank Sta=6116.72,6407.7
XS Rating Curve= 0
Vertical n Elevations= 2
       5      12
Vertical n for Station=0
     .07      .1
Vertical n for Station=5606.51
     .12     .24
Vertical n for Station=6128.83
    .035    .035
Vertical n for Station=6276.86
     .07      .1
Vertical n Flow= 0
Exp/Cntr=.3,.1

Type RM Length L Ch R = 1 ,61909.39,266.34,407.55,556.51
XS GIS Cut Line= 4
     3197456.464    13757726.732     3199065.764    13751806.212
     3199347.725    13751197.768      3199833.71    13747881.845
#Sta/Elev= 30
       0   16.87 2596.51   17.14 2615.91   16.69 2657.93     .75 2669.56    8.07
 2695.23    2.54  2724.9   15.78 2808.08   16.67 4660.94   14.42 6150.79    1.05
 6363.43    4.83 6372.77     .31  6396.6    -.88 6414.94   -9.16 6434.93  -12.87
 6584.56       2 6799.49    2.92 6865.25    6.46 6952.35   11.49 7311.66   18.35
 8129.09    16.6  8462.1   20.43 8478.37   14.48 8658.47   16.34 8668.38   19.04
  9456.1   19.17 9469.42   16.34  9502.4   16.99 9511.05   20.4510157.29   21.13
#Mann= 4 ,-1 , 0
       0     .07       0 5536.33     .12       0 6370.75    .035       0
 6576.54     .07       0
#Block Obstruct= 1 ,-1
 2473.28 2821.37   15.26
Bank Sta=6363.43,6865.25
XS Rating Curve= 0
Vertical n Elevations= 2
       5      12
Vertical n for Station=0
     .07      .1
Vertical n for Station=5632.49
     .12     .24
Vertical n for Station=6372.77
    .035    .035
Vertical n for Station=6579.14
     .07      .1
Vertical n Flow= 0
Exp/Cntr=.3,.1

Type RM Length L Ch R = 1 ,61501.83,236.7,468.94,240.96
XS GIS Cut Line= 4
     3196997.366    13759840.177     3199280.945    13751910.092
     3199770.668     13751583.61     3200326.821    13748485.583
#Sta/Elev= 30
       0   20.22  4789.1   17.14 4806.95   16.69  4850.4     .75 4865.44    8.07
 4888.52    2.54 4909.47   15.77 5170.28   18.25 6402.07   17.31 7806.53     .24
 8426.71    3.76 8482.71   -1.49 8512.78  -11.63 8574.86   -9.74 8624.42    3.68
 8885.37    7.12 8906.82   14.95 9184.09    7.12  9200.4    14.3 9231.18    7.42
 9251.21   15.33 9260.77    7.48 9283.68   11.02 9314.01    6.06 9352.56   15.55
 9557.48   17.5910571.98   19.9710583.03   14.7410691.78   20.9511988.46   21.04
#Mann= 6 ,-1 , 0
       0     .07       0 6953.55     .12       0 7808.57    .035       0
 8335.82     .12       0 8461.46    .035       0 8616.35     .07       0
#Block Obstruct= 2 ,-1
 4598.47 4928.24   15.26 8945.91 9415.65   13.74
Bank Sta=8426.71,8624.42
XS Rating Curve= 0
Vertical n Elevations= 2
       5      12
Vertical n for Station=0
     .07      .1
Vertical n for Station=8339.76
     .12     .24
Vertical n for Station=8062.89
    .035    .035
Vertical n for Station=6964.91
     .12     .24
Vertical n for Station=8461.67
    .035    .035
Vertical n for Station=8619.21
     .07      .1
Vertical n Flow= 0
Exp/Cntr=.3,.1