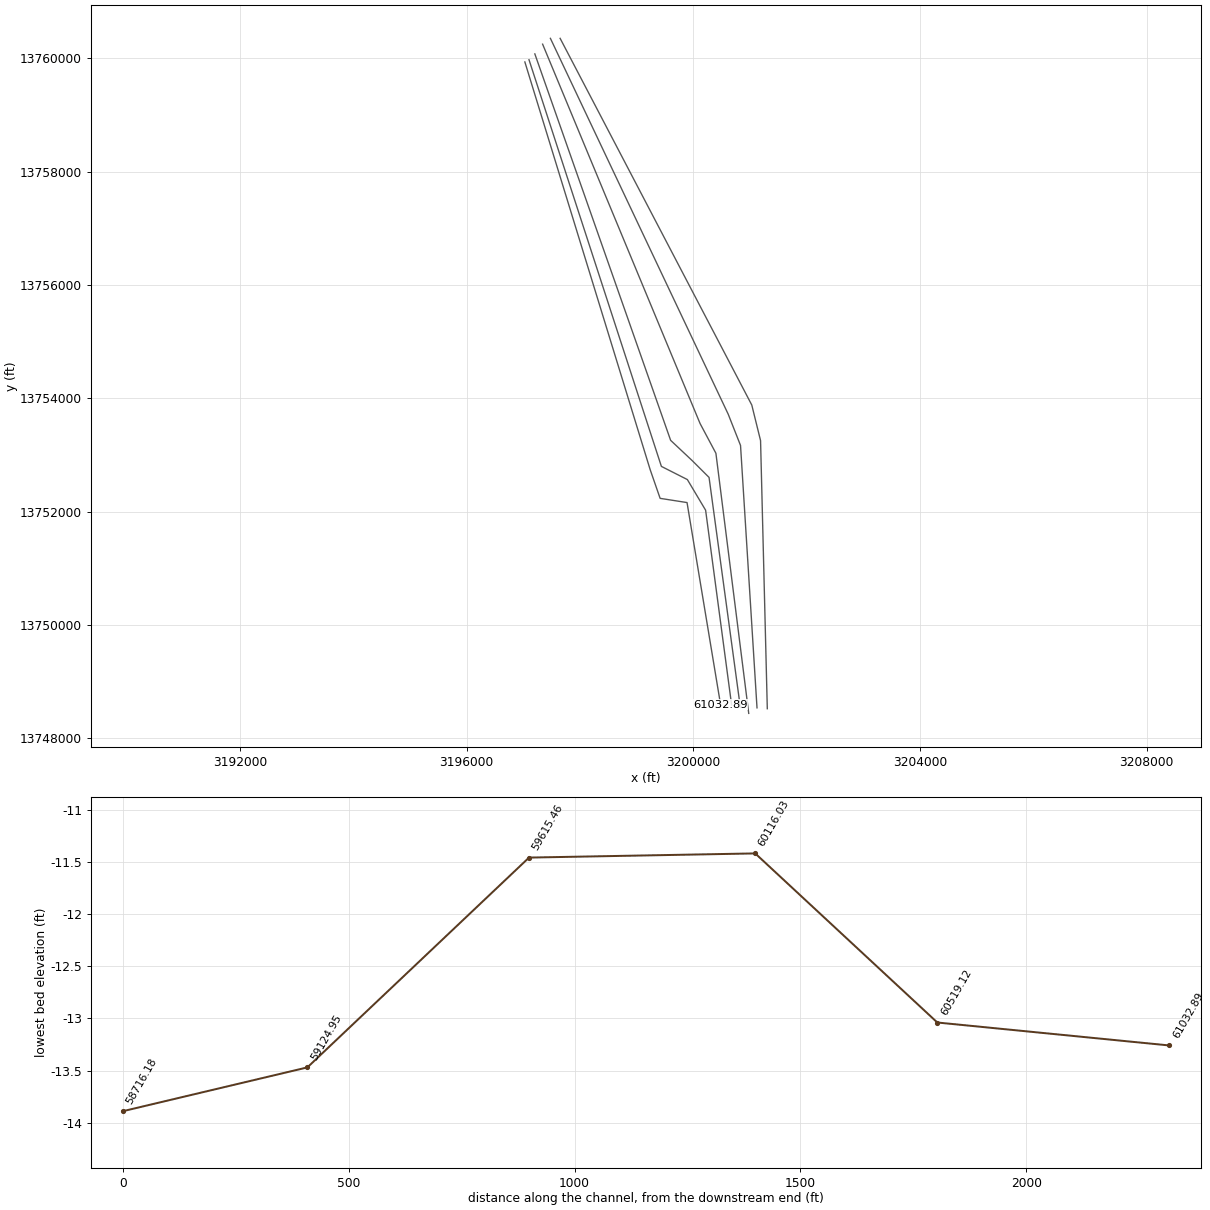
HEC-RAS study A100-00-00.prj: A100-00-00

--- A100-00-00.g01 (geometry) --- (continued)

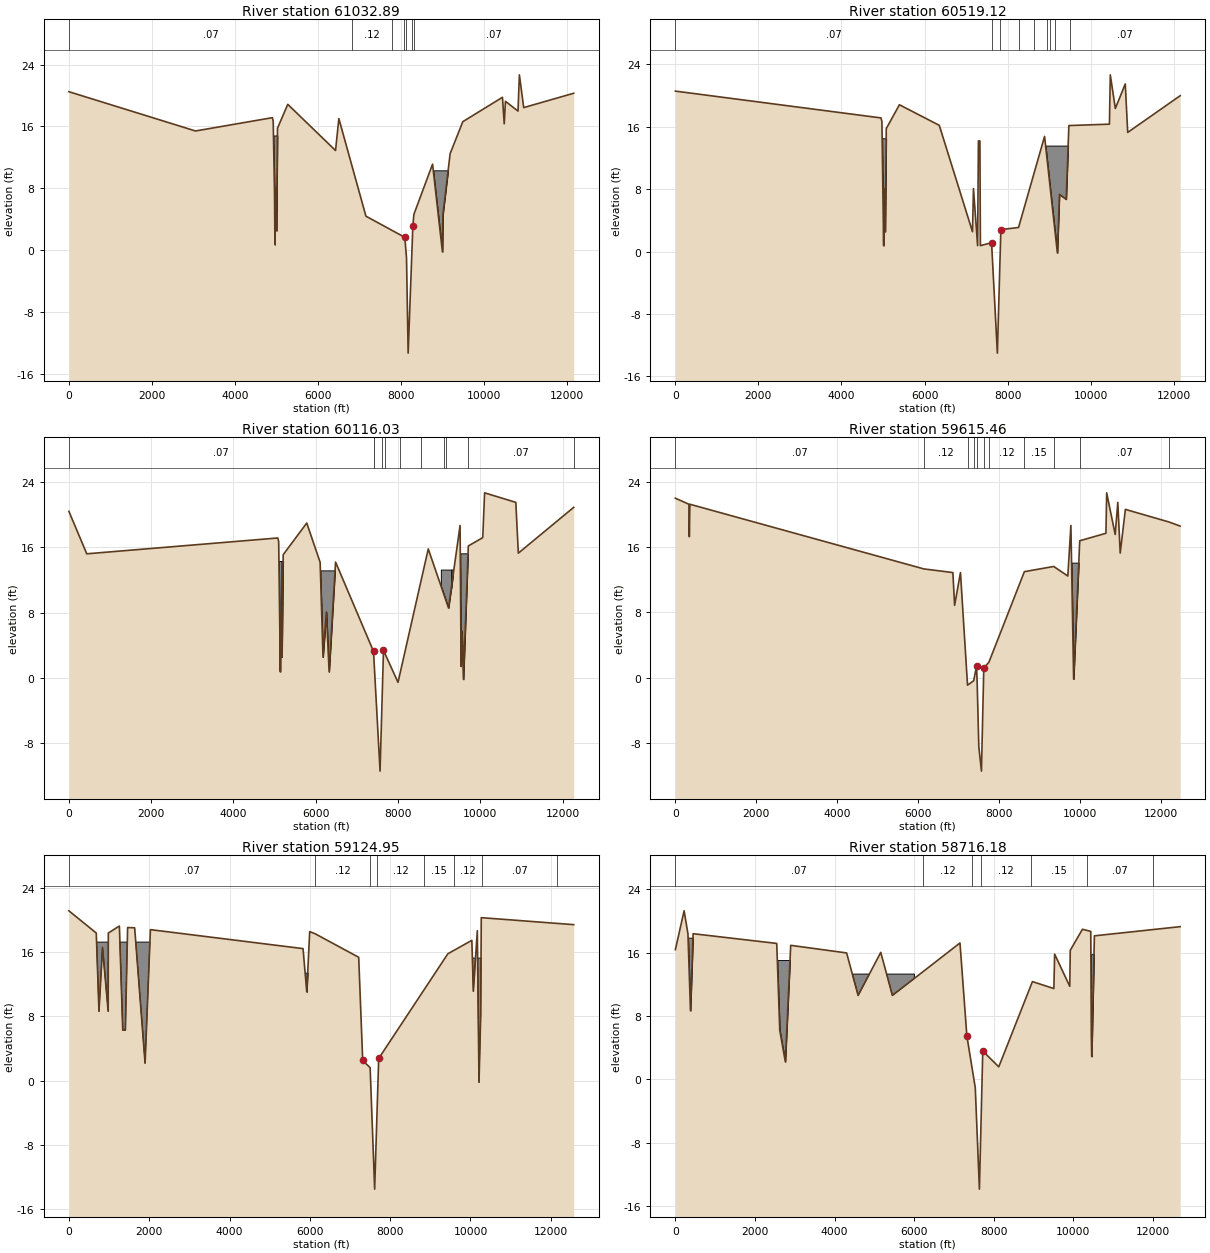
Type RM Length L Ch R = 1 ,61032.89,252.94,513.78,480.11
XS GIS Cut Line= 5
     3197027.341    13759938.365     3199238.974    13752742.305
     3199414.506    13752236.574     3199889.389    13752162.374
     3200481.932    13748592.222
#Sta/Elev= 30
       0   20.49 3051.28   15.42 4903.64   17.14 4922.56   16.69 4954.17    7.47
 4964.13     .75 4977.89    8.07 5004.39    2.54 5025.61   15.77 5273.84   18.86
 6424.62    12.9 6504.44   17.02 7156.93    4.42 8093.65    1.69 8134.65    -.95
 8174.02  -13.26 8287.83    3.21 8313.56    4.67 8762.31   11.14 9000.21    -.18
 9012.17    4.64 9185.48   12.49 9491.02   16.62 10446.9   19.7710489.11   16.34
10518.39   19.2510821.09   17.9910854.06   22.6710958.65   18.4412163.22   20.29
#Mann= 7 ,-1 , 0
       0     .07       0 6822.23     .12       0 7788.48    .035       0
 8068.84     .12       0 8119.44    .035       0 8273.06     .12       0
 8313.56     .07       0
#Block Obstruct= 2 ,-1
 4766.41 5129.77   14.84 8720.61 9297.71   10.34
Bank Sta=8093.65,8287.83
XS Rating Curve= 0
Vertical n Elevations= 2
       5      12
Vertical n for Station=0
     .07      .1
Vertical n for Station=6840.13
     .12     .24
Vertical n for Station=7788.63
    .035    .035
Vertical n for Station=8070.96
     .12     .24
Vertical n for Station=8120.29
    .035    .035
Vertical n for Station=8277.9
     .12     .24
Vertical n for Station=8313.56
     .07      .1
Vertical n Flow= 0
Exp/Cntr=.3,.1

Type RM Length L Ch R = 1 ,60519.12,332.32,403.08,417.81
XS GIS Cut Line= 5
     3197100.337    13759977.472     3199436.766    13752800.498
     3199895.238    13752568.137     3200217.242     13752027.65
     3200675.821    13748592.222
#Sta/Elev= 30
       0   20.58 4951.21   17.14  4973.8   16.69    5016     .75 5028.92    8.07
 5054.54    2.54 5079.06   15.77 5395.24   18.83 6355.46   16.19 7155.19    2.54
 7178.83    8.07 7278.56     .75 7297.73   14.19  7333.5   14.19 7346.26     .75
 7614.75    1.13  7754.3  -13.04  7838.5    2.81 8264.15    3.08  8891.2   14.77
  9199.8    -.18 9249.51    7.32 9412.01     6.7 9476.44   16.1610453.07   16.34
10473.89   22.6710595.33   18.3510834.51    21.510893.15   15.2812156.73   19.99
#Mann= 9 ,-1 , 0
       0     .07       0  7633.7    .035       0 7827.72     .07       0
 8264.15     .12       0 8638.33     .15       0  8943.1     .12       0
  9029.9     .07       0 9145.51     .12       0 9492.34     .07       0
#Block Obstruct= 2 ,-1
 4894.66 5236.64   14.53 8870.23 9639.69   13.59
Bank Sta=7614.75,7838.5
XS Rating Curve= 0
Vertical n Elevations= 2
       5      12
Vertical n for Station=0
     .07      .1
Vertical n for Station=7640.58
    .035    .035
Vertical n for Station=7830.84
     .07      .1
Vertical n for Station=8264.15
     .12     .24
Vertical n for Station=8657.96
     .15     .15
Vertical n for Station=8946.44
     .12     .24
Vertical n for Station=9062.78
     .07      .1
Vertical n for Station=9145.78
     .12     .24
Vertical n for Station=9499.74
     .07      .1
Vertical n Flow= 0
Exp/Cntr=.3,.1

Type RM Length L Ch R = 1 ,60116.03,593.64,500.57,257.27
XS GIS Cut Line= 5
     3197203.308    13760080.443     3199600.007     13753260.54
     3199979.183     13752903.92     3200278.121    13752605.993
     3200830.932     13748543.75
#Sta/Elev= 30
       0    20.4  434.21    15.2 5078.32   17.14 5099.38   16.69 5139.72     .75
 5152.59    8.07 5178.89    2.54 5209.09   15.09 5781.66   18.97    6107   14.16
 6177.33    2.54 6258.34    8.07 6325.65     .75 6482.15   14.19 7404.64    3.25
  7563.7  -11.42 7647.16    3.37 8000.21    -.55  8735.7    15.8 9227.82    8.57
 9508.67   18.67 9533.54    1.42 9554.11    5.76 9590.94    -.18 9708.84   16.16
10059.71   17.1810105.21   22.6710863.81    21.510925.05   15.2812271.05   20.89
#Mann= 11 ,-1 , 0
       0     .07       0 7407.42     .12       0 7422.76    .035       0
 7612.71     .12       0 7689.04     .07       0 8041.59     .12       0
 8567.16     .15       0 9116.16     .07       0 9160.22     .12       0
 9694.13     .07       012267.86     .15       0
#Block Obstruct= 6 ,-1
 5001.53 5172.52   14.32 5170.64 5282.13   14.32 5963.36 6497.71   13.17
 9041.22 9297.71   13.27  9295.8 9333.52   13.27 9425.95 9746.56   15.26
Bank Sta=7404.64,7647.16
XS Rating Curve= 0
Vertical n Elevations= 2
       5      12
Vertical n for Station=0
     .07      .1
Vertical n for Station=7426.5
    .035    .035
Vertical n for Station=7616.37
     .12     .24
Vertical n for Station=7733.42
     .07      .1
Vertical n for Station=8046.61
     .12     .24
Vertical n for Station=8567.42
     .15     .15
Vertical n for Station=9121.44
     .07      .1
Vertical n for Station=9177.54
     .12     .24
Vertical n for Station=9698.82
     .07      .1
Vertical n for Station=12271.05
     .15     .15
Vertical n Flow= 0
Exp/Cntr=.3,.1

Type RM Length L Ch R = 1 ,59615.46,551.4,490.52,440.98
XS GIS Cut Line= 4
     3197340.603    13760252.062      3200119.41    13753557.342
     3200398.911    13753032.307      3200978.22    13748441.924
#Sta/Elev= 30
       0   22.01  334.66   21.27  344.62   17.29  358.62   21.27 6137.12   13.34
 6855.14   12.89 6898.06    8.87 7042.73   12.89 7217.19    -.92 7370.04    -.37
 7439.85    1.42 7455.59    -.68 7495.94   -8.46 7560.79  -11.46 7618.87    1.19
 7744.87    1.89 8621.34      13 9345.57   13.64 9694.76   12.47 9770.67   18.67
 9838.43    -.18 9989.06   16.7910636.34   17.7110654.34   22.6710865.09   17.56
10929.22    21.510989.01   15.28 11116.4   20.6412195.93   19.0912470.12   18.59
#Mann= 11 ,-1 , 0
       0     .07       0 6137.12     .12       0 7217.19    .035       0
 7370.04     .12       0 7455.59    .035       0 7618.87     .12       0
 7744.87     .12       0 8621.34     .15       0 9345.57     .12       0
 9989.06     .07       012195.93     .15       0
#Block Obstruct= 1 ,-1
 9746.5610024.43   14.11
Bank Sta=7439.85,7618.87
XS Rating Curve= 0
Vertical n Elevations= 2
       5      12
Vertical n for Station=0
     .07      .1
Vertical n for Station=6137.12
     .12     .24
Vertical n for Station=7217.19
    .035    .035
Vertical n for Station=7370.04
     .12     .24
Vertical n for Station=7455.59
    .035    .035
Vertical n for Station=7618.87
     .12     .24
Vertical n for Station=7744.87
     .12     .24
Vertical n for Station=8621.34
     .15     .15
Vertical n for Station=9345.57
     .12     .24
Vertical n for Station=9989.06
     .07      .1
Vertical n for Station=12195.93
     .15     .15
Vertical n Flow= 0
Exp/Cntr=.3,.1

Type RM Length L Ch R = 1 ,59124.95,455.88,408.77,345.38
XS GIS Cut Line= 4
     3197477.898    13760355.033     3200616.553    13753720.583
     3200833.454    13753170.571     3201124.328    13748539.329
#Sta/Elev= 30
       0   21.14  681.38   18.38  748.99    8.65  836.72   16.59  978.21    8.65
  981.72   18.38 1257.16   19.25 1340.92    6.31 1406.39    6.31  1462.3   19.06
  1637.5   19.03 1897.25     2.2 2029.63    18.8 5830.61   16.44 5923.22   11.06
 5996.55   18.55 6131.39   18.29 7216.67   15.36 7316.41    2.53 7501.51    1.63
 7613.98  -13.47 7714.76    2.78 9437.21    15.810034.43   17.4710071.88   11.14
10170.64   18.6710212.57    -.1810255.72    8.3410268.81   20.2912571.02   19.42
#Mann= 8 ,-1 , 0
       0     .07       0 6131.39     .12       0 7494.09    .035       0
 7676.24     .12       0 8854.65     .15       0 9587.16     .12       0
 10284.1     .07       012163.85     .15       0
#Block Obstruct= 3 ,-1
   491.6 2051.91   17.25 5686.01 6307.17   13.45 9981.6810323.66   15.26
Bank Sta=7316.41,7714.76
XS Rating Curve= 0
Vertical n Elevations= 2
       5      12
Vertical n for Station=0
     .07      .1
Vertical n for Station=6131.39
     .12     .24
Vertical n for Station=7501.51
    .035    .035
Vertical n for Station=7693.35
     .12     .24
Vertical n for Station=8858.29
     .15     .15
Vertical n for Station=9590.69
     .12     .24
Vertical n for Station=10294.11
     .07      .1
Vertical n for Station=12177.22
     .15     .15
Vertical n Flow= 0
Exp/Cntr=.3,.1

Type RM Length L Ch R = 1 ,58716.18,673.31,578.15,278.7
XS GIS Cut Line= 4
     3197649.516    13760355.033     3201032.075    13753883.824
     3201186.966    13753255.832      3201305.96    13748524.361
#Sta/Elev= 30
       0   16.37  219.61   21.27  315.69   18.38  379.75    8.65  445.97   18.38
  2546.5   17.15 2623.02    6.16 2762.74     2.2 2897.51   16.91 4302.13   15.95
 4591.13   10.58 5159.83   16.02 5452.38   10.58 7150.07   17.21 7322.59    5.48
  7534.4   -1.09 7638.09  -13.89 7722.57    3.56 8124.38    1.56 8970.09   12.33
 9508.74   11.45 9528.02    15.8 9908.17   11.73 9920.39   16.2810226.03   18.94
10435.62   18.6710449.48    5.5710460.02    2.8710527.14   18.1112681.72   19.27
#Mann= 7 ,-1 , 0
       0     .07       0 6223.17     .12       0 7455.33    .035       0
 7687.66     .12       0  8938.2     .15       010331.04     .07       0
12009.46     .15       0
#Block Obstruct= 4 ,-1
  192.37  555.73   17.88 2479.39 2970.99   15.05 3854.38 6004.55   13.28
10323.66 10537.4   15.79
Bank Sta=7322.59,7722.57
XS Rating Curve= 0
Vertical n Elevations= 2
       5      12
Vertical n for Station=0
     .07      .1
Vertical n for Station=6224.88
     .12     .24
Vertical n for Station=7506.86
    .035    .035
Vertical n for Station=7689.92
     .12     .24
Vertical n for Station=8941.01
     .15     .15
Vertical n for Station=10370.54
     .07      .1
Vertical n for Station=12013.91
     .15     .15
Vertical n Flow= 0
Exp/Cntr=.3,.1