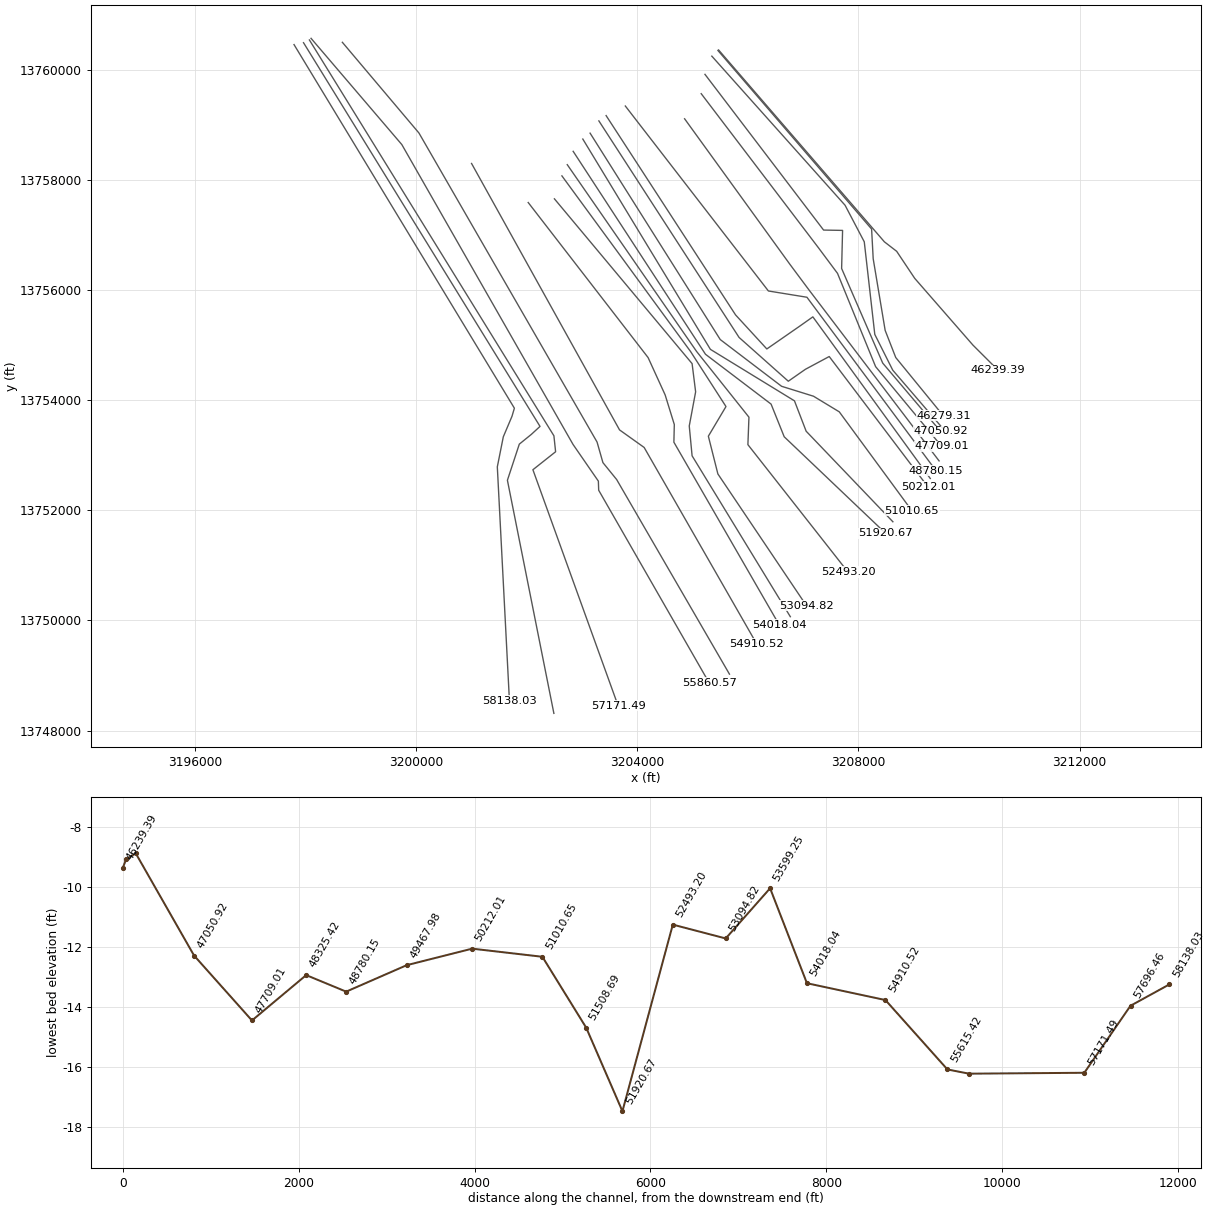
HEC-RAS study A100-00-00.prj: A100-00-00

--- A100-00-00.g01 (geometry) --- (continued)

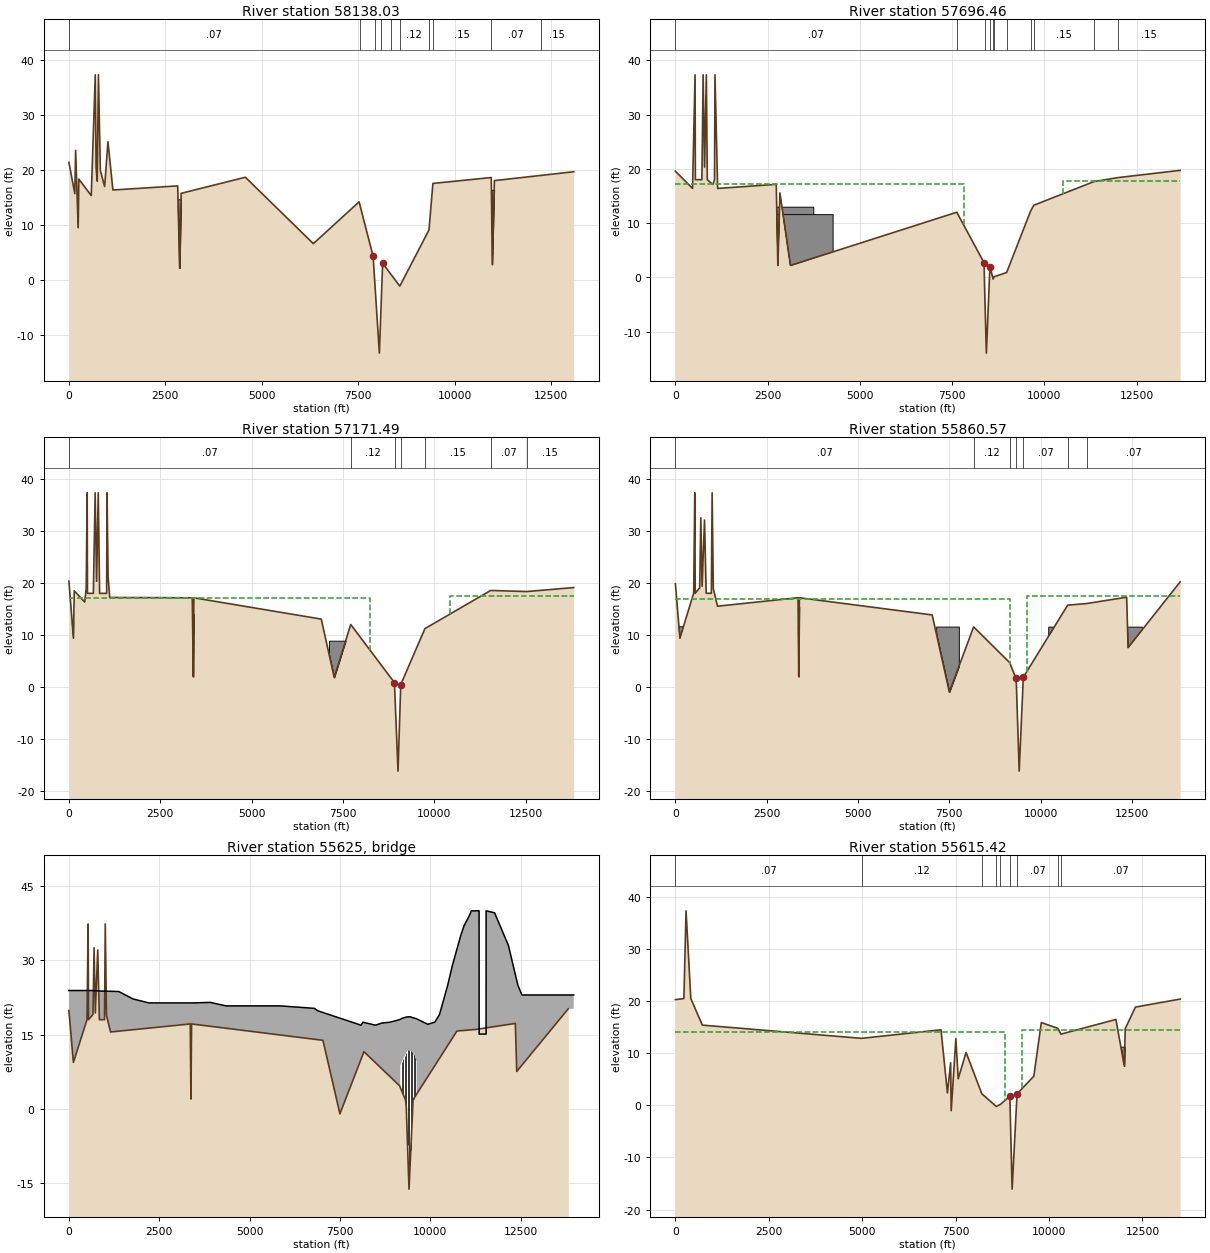
Type RM Length L Ch R = 1 ,58138.03,500.38,441.57,236.55
XS GIS Cut Line= 6
     3197786.811    13760458.004      3201774.08    13753854.144
     3201730.595    13753706.315     3201573.739    13753334.741
     3201465.245    13752788.627     3201684.407    13748539.329
#Sta/Elev= 30
       0   21.41  153.17   15.75  174.11   23.61   240.5    9.56  257.78   18.38
  579.13    15.4  683.33   37.34  705.55   20.41   734.1   18.01  765.19   37.34
  815.43   19.91  926.21   17.04 1011.97   25.17 1140.37    16.4 2819.29   17.15
 2870.16     2.2 2910.73    15.8 4574.03   18.72 6335.44    6.65 7521.05   14.25
  7884.5    4.36 8046.39  -13.25 8131.31    3.08 8576.41   -1.07 9332.67    9.14
  9434.4    17.610946.81   18.6710972.28    2.8711028.01   18.1113083.37   19.72
#Mann= 10 ,-1 , 0
       0     .07       0 7534.45     .12       0  7934.8    .035       0
 8089.45     .12       0 8352.03     .07       0 8576.41     .12       0
 9325.57     .07       0 9426.83     .15       010929.98     .07       0
12231.78     .15       0
#Block Obstruct= 3 ,-1
   95.56 4204.78   13.64 2629.01 2970.99   14.7110601.5311071.76   16.44
Bank Sta=7884.5,8131.31
XS Rating Curve= 0
Vertical n Elevations= 2
       5      12
Vertical n for Station=0
     .07      .1
Vertical n for Station=7564.71
     .12     .24
Vertical n for Station=7936.2
    .035    .035
Vertical n for Station=8095.13
     .12     .24
Vertical n for Station=8373.88
     .07      .1
Vertical n for Station=8576.41
     .12     .24
Vertical n for Station=9331.23
     .07      .1
Vertical n for Station=9434.4
     .15     .15
Vertical n for Station=10931.99
     .07      .1
Vertical n for Station=12286.84
     .15     .15
Vertical n Flow= 0
Exp/Cntr=.5,.3

Type RM Length L Ch R = 1 ,57696.46,494.04,524.97,548.19
XS GIS Cut Line= 6
      3197958.43    13760492.328     3202237.907    13753523.188
     3202079.527    13753377.181      3201863.12     13753201.18
      3201647.88    13752545.115     3202488.682    13748311.083
#Sta/Elev= 30
       0   19.58  465.31   16.41  533.72   37.34  542.03   18.01  718.75   18.01
  752.41   37.34  791.36   20.34  839.36   37.34  865.33   18.01 1018.18   17.13
 1061.18   18.01 1072.96   37.34  1145.6    16.4 2733.72   17.15 2777.44     2.2
 2833.66   15.58 3118.91     2.2 7625.98   12.01 8365.32     2.7 8378.18   -1.39
 8427.92  -13.96  8523.7    1.96 8611.47     -.3 8634.82     .11 8977.37      .9
  9628.4   12.26 9713.33    13.3 11347.6   17.6712002.02    18.413679.72   19.73
#Mann= 11 ,-1 , 0
       0     .07       0 7625.98     .12       0 8378.18    .035       0
  8523.7     .12       0 8611.47     .12       0 8634.82     .07       0
 8977.37     .12       0  9628.4     .07       0 9713.33     .15       0
 11347.6     .07       012002.02     .15       0
#XS Ineff= 2 ,-1
       0 7809.34   17.1910497.6813679.72   17.68
Permanent Ineff=
       F       F
#Block Obstruct= 5 ,-1
   43.49 3751.21   12.94 2458.02 4274.81   11.57 6818.32 7416.79    9.21
10146.2713724.02   12.7311328.2411499.24   16.44
Bank Sta=8365.32,8523.7
XS Rating Curve= 0
Vertical n Elevations= 2
       5      12
Vertical n for Station=0
     .07      .1
Vertical n for Station=7625.98
     .12     .24
Vertical n for Station=8378.18
    .035    .035
Vertical n for Station=8523.7
     .12     .24
Vertical n for Station=8611.47
     .12     .24
Vertical n for Station=8634.82
     .07      .1
Vertical n for Station=8977.37
     .12     .24
Vertical n for Station=9628.4
     .07      .1
Vertical n for Station=9713.33
     .15     .15
Vertical n for Station=11347.6
     .07      .1
Vertical n for Station=12002.02
     .15     .15
Vertical n Flow= 0
Exp/Cntr=.5,.3

Type RM Length L Ch R = 1 ,57171.49,378.99,1310.92,1280.62
XS GIS Cut Line= 5
     3198065.008    13760541.911     3202489.159    13753352.997
     3202520.022    13753062.895     3202109.223    13752736.236
     3203652.015    13748446.806
#Sta/Elev= 30
       0   20.36  124.49    9.38  145.86    18.5  432.17   16.34  473.23   18.97
  500.19   37.34  508.89   18.01  669.22   18.01  718.27   37.34  758.17   20.34
  803.28   37.34  840.23   18.01 1032.69   18.01 1043.62   37.34 1072.13   21.19
 1117.49   17.22 3376.44   17.15 3405.06    1.98 3420.41   17.15  6907.2   13.05
 7261.65    1.82 7713.62   12.01 8909.71     .84 8919.17    -.85 9007.64  -16.19
 9082.78     .46  9744.1   11.2211543.04   18.5612529.29   18.3513816.22   19.12
#Mann= 7 ,-1 , 0
       0     .07       0 7713.62     .12       0 8919.17    .035       0
 9082.78     .07       0  9744.1     .15       011543.04     .07       0
12529.29     .15       0
#XS Ineff= 2 ,-1
       0 8231.84   17.0910417.2913816.22   17.59
Permanent Ineff=
       F       F
#Block Obstruct= 4 ,-1
 -119.55 5609.81   12.47 3227.48 3483.97   14.08 7117.56 7587.79     8.9
10568.0411445.25   12.48
Bank Sta=8909.71,9082.78
XS Rating Curve= 0
Vertical n Elevations= 2
       5      12
Vertical n for Station=0
     .07      .1
Vertical n for Station=7713.62
     .12     .24
Vertical n for Station=8919.17
    .035    .035
Vertical n for Station=9082.78
     .07      .1
Vertical n for Station=9744.1
     .15     .15
Vertical n for Station=11543.04
     .07      .1
Vertical n for Station=12529.29
     .15     .15
Vertical n Flow= 0
Exp/Cntr=.5,.3

Type RM Length L Ch R = 1 ,55860.57,412.02,245.15,384.8
XS GIS Cut Line= 6
     3198094.694    13760571.597     3199737.351    13758641.971
     3202835.439    13753195.618     3203293.692    13752529.262
     3203299.463    13752363.826     3205300.572    13748861.984
#Sta/Elev= 30
       0   19.85  124.37    9.38  501.04   18.02  531.81   37.34  543.25   18.01
  665.96   19.06  696.69   32.53  731.33   19.36  797.57   32.09  843.67   18.01
  985.31   18.01 1006.17   37.34 1038.23   18.93 1152.37   15.52 3357.59   17.15
 3377.26    1.98 3393.83   17.15 7029.57   13.84 7499.01   -1.01 8164.05   11.54
 9150.72    4.66 9316.69    1.72 9333.97      .5 9410.85  -16.22 9523.69    1.85
10737.99   15.7211253.76   16.0312352.75   17.2512391.96    7.5513817.26   20.21
#Mann= 7 ,-1 , 0
       0     .07       0 8164.05     .12       0 9150.72     .07       0
 9333.97    .035       0 9523.69     .07       010737.99     .15       0
11253.76     .07       0
#XS Ineff= 2 ,-1
       0  9169.9      17    962013817.26    17.5
Permanent Ineff=
       F       F
#Block Obstruct= 4 ,-1
 -140.41  6732.6   11.56 3141.98 3483.97   15.39 7138.93 7758.78    11.6
10219.6712782.78   11.49
Bank Sta=9316.69,9523.69
XS Rating Curve= 0
Vertical n Elevations= 2
       5      12
Vertical n for Station=0
     .07      .1
Vertical n for Station=8164.05
     .12     .24
Vertical n for Station=9150.72
     .07      .1
Vertical n for Station=9333.97
    .035    .035
Vertical n for Station=9523.69
     .07      .1
Vertical n for Station=10737.99
     .15     .15
Vertical n for Station=11253.76
     .07      .1
Vertical n Flow= 0
Exp/Cntr=.5,.3

Type RM Length L Ch R = 3 ,55625   ,,,
BEGIN DESCRIPTION:
IH45
END DESCRIPTION:
Bridge Culvert--1,0,-1,-1, 0
Deck Dist Width WeirC Skew NumUp NumDn MinLoCord MaxHiCord MaxSubmerge Is_Ogee
5,235,2.6,0, 53, 53, , , .95, 0, 0,0,,
       0     650     867    1378    1772    2212    2750    3412    3912    4345
    5842    6791    6889    8083    8137    8478    8668    8874    9074    9169
    9170    9210    9250    9290    9330    9370    9420    9460    9500    9540
    9580    9620    9621    9929   10124   10252   10329   10482   10612   10842
   10934   11079   11137   11350   11351   11543   11544   11779   12162   12422
   12535   13260   13968
    23.9    23.9    23.8    23.7    22.2    21.4    21.4    21.4    21.5    20.8
    20.8    20.3    19.8    16.9    17.5    16.9   17.34   17.49   17.86   18.07
   18.07   18.25   18.36   18.44   18.53   18.57   18.59   18.57   18.43   18.36
   18.28   18.18   18.18   17.08   17.51      19      21      25      29      35
      37      39      40      40    15.1    15.1      40    39.6      33      25
      23      23      23
                                                                                
                                                                                
     8.8     9.5    10.1    10.7    11.3    11.8    11.8    11.7    11.4    10.8
    10.2     9.6
                                                                                
                        
       0     315     532    1043    1437    1877    2415    3077    3577    4010
    5507    6456    6554    7748    7802    8143    8333    8539    8739    8834
    8835    8875    8915    8955    8995    9035    9085    9125    9165    9205
    9245    9285    9286    9594    9789    9917    9994   10147   10277   10507
   10599   10744   10802   11015   11016   11208   11209   11444   11827   12087
   12200   12925   13633
    23.9    23.9    23.8    23.7    22.2    21.4    21.4    21.4    21.5    20.8
    20.8    20.3    19.8    16.9    17.5    16.9   17.34   17.49   17.86   18.07
   18.07   18.25   18.36   18.44   18.53   18.57   18.59   18.57   18.43   18.36
   18.28   18.18   18.18   17.08   17.51      19      21      25      29      35
      37      39      40      40    15.1    15.1      40    39.6      33      25
      23      23      23
                                                                                
                                                                                
     8.8     9.5    10.1    10.7    11.3    11.8    11.8    11.7    11.4    10.8
    10.2     9.6
                                                                                
                        
Pier Skew, UpSta & Num, DnSta & Num=  ,9210, 2 ,8875, 2 , 0 , 0 , 0 ,,
    1.33    1.33
     -30      17
    1.33    1.33
     -30      17
Pier Skew, UpSta & Num, DnSta & Num=  ,9250, 2 ,8915, 2 , 0 , 0 , 0 ,,
    1.33    1.33
     -30      17
    1.33    1.33
     -30      17
Pier Skew, UpSta & Num, DnSta & Num=  ,9290, 2 ,8955, 2 , 0 , 0 , 0 ,,
    1.33    1.33
     -30      17
    1.33    1.33
     -30      17
Pier Skew, UpSta & Num, DnSta & Num=  ,9330, 2 ,8995, 2 , 0 , 0 , 0 ,,
    1.33    1.33
     -30      17
    1.33    1.33
     -30      17
Pier Skew, UpSta & Num, DnSta & Num=  ,9370, 2 ,9035, 2 , 0 , 0 , 0 ,15,15
    1.33    1.33
     -30      17
    1.33    1.33
     -30      17
Pier Skew, UpSta & Num, DnSta & Num=  ,9420, 2 ,9085, 2 , 0 , 0 , 0 ,15,15
    1.33    1.33
     -30      17
    1.33    1.33
     -30      17
Pier Skew, UpSta & Num, DnSta & Num=  ,9460, 2 ,9125, 2 , 0 , 0 , 0 ,,
    1.33    1.33
     -30      17
    1.33    1.33
     -30      17
Pier Skew, UpSta & Num, DnSta & Num=  ,9500, 2 ,9165, 2 , 0 , 0 , 0 ,,
    1.33    1.33
     -30      17
    1.33    1.33
     -30      17
Pier Skew, UpSta & Num, DnSta & Num=  ,9540, 2 ,9205, 2 , 0 , 0 , 0 ,,
    1.33    1.33
     -30      17
    1.33    1.33
     -30      17
Pier Skew, UpSta & Num, DnSta & Num=  ,9582, 2 ,9245, 2 , 0 , 0 , 0 ,,
    1.33    1.33
     -30      17
    1.33    1.33
     -30      17
Abutment Skew #Up #Dn= , 2 , 2
    9169    9200
       8       1
    8834    8870
       9       2
Abutment Skew #Up #Dn= , 2 , 2
    9590    9620
       1       8
    9258    9288
       1       9
BR Coef=-1 , 1 , 1 ,1.25, 0 ,,,.8,-1,2,0,
WSPro=,,,, 1 ,,,, 0 ,,,, 0 ,,,,-1 ,-1 ,-1 , 0 , 0 , 0 , 0 , 0
BC Design=,, 0 ,, 0 ,,,,,,
BC HTab HWMax=37.34

Type RM Length L Ch R = 1 ,55615.42,544.26,704.9,753.03
XS GIS Cut Line= 6
     3198661.309    13760499.525     3200047.144    13758852.032
     3203270.051    13753239.017     3203376.007    13752865.711
     3203624.564    13752558.117     3205665.661    13749023.695
#Sta/Elev= 30
       0   20.31  228.37   20.52  285.34   37.37  413.44   20.52  721.85   15.42
  4983.2   12.88 7109.33   14.52 7281.33    2.39 7367.25    8.18 7382.42   -1.01
 7507.53   12.82 7570.25     5.1 7780.16   10.18 8201.71    2.24 8587.38     -.2
 8698.68     .19 8948.23    1.75 8955.27     .84  9012.8  -16.08 9141.99    1.84
 9153.25    2.27 9593.82    5.61  9794.6   15.9110237.29    14.810317.92   13.68
11790.71   16.5112014.93    7.5512040.08   14.72 12312.6   18.8813510.66   20.42
#Mann= 9 ,-1 , 0
       0     .07       0  4983.2     .12       0 8201.71     .07       0
 8587.38    .035       0 8698.68     .07       0 8955.27    .035       0
 9141.99     .07       010237.29     .15       010317.92     .07       0
#XS Ineff= 2 ,-1
       0 8834.89   14.06    928513510.66   14.48
Permanent Ineff=
       F       F
#Block Obstruct= 1 ,-1
11821.8912206.21   11.29
Bank Sta=8948.23,9153.25
XS Rating Curve= 0
Vertical n Elevations= 2
       5      12
Vertical n for Station=0
     .07      .1
Vertical n for Station=4983.2
     .12     .24
Vertical n for Station=8201.71
     .07      .1
Vertical n for Station=8587.38
    .035    .035
Vertical n for Station=8698.68
     .07      .1
Vertical n for Station=8955.27
    .035    .035
Vertical n for Station=9141.99
     .07      .1
Vertical n for Station=10237.29
     .15     .15
Vertical n for Station=10317.92
     .07      .1
Vertical n Flow= 0
Exp/Cntr=.5,.3

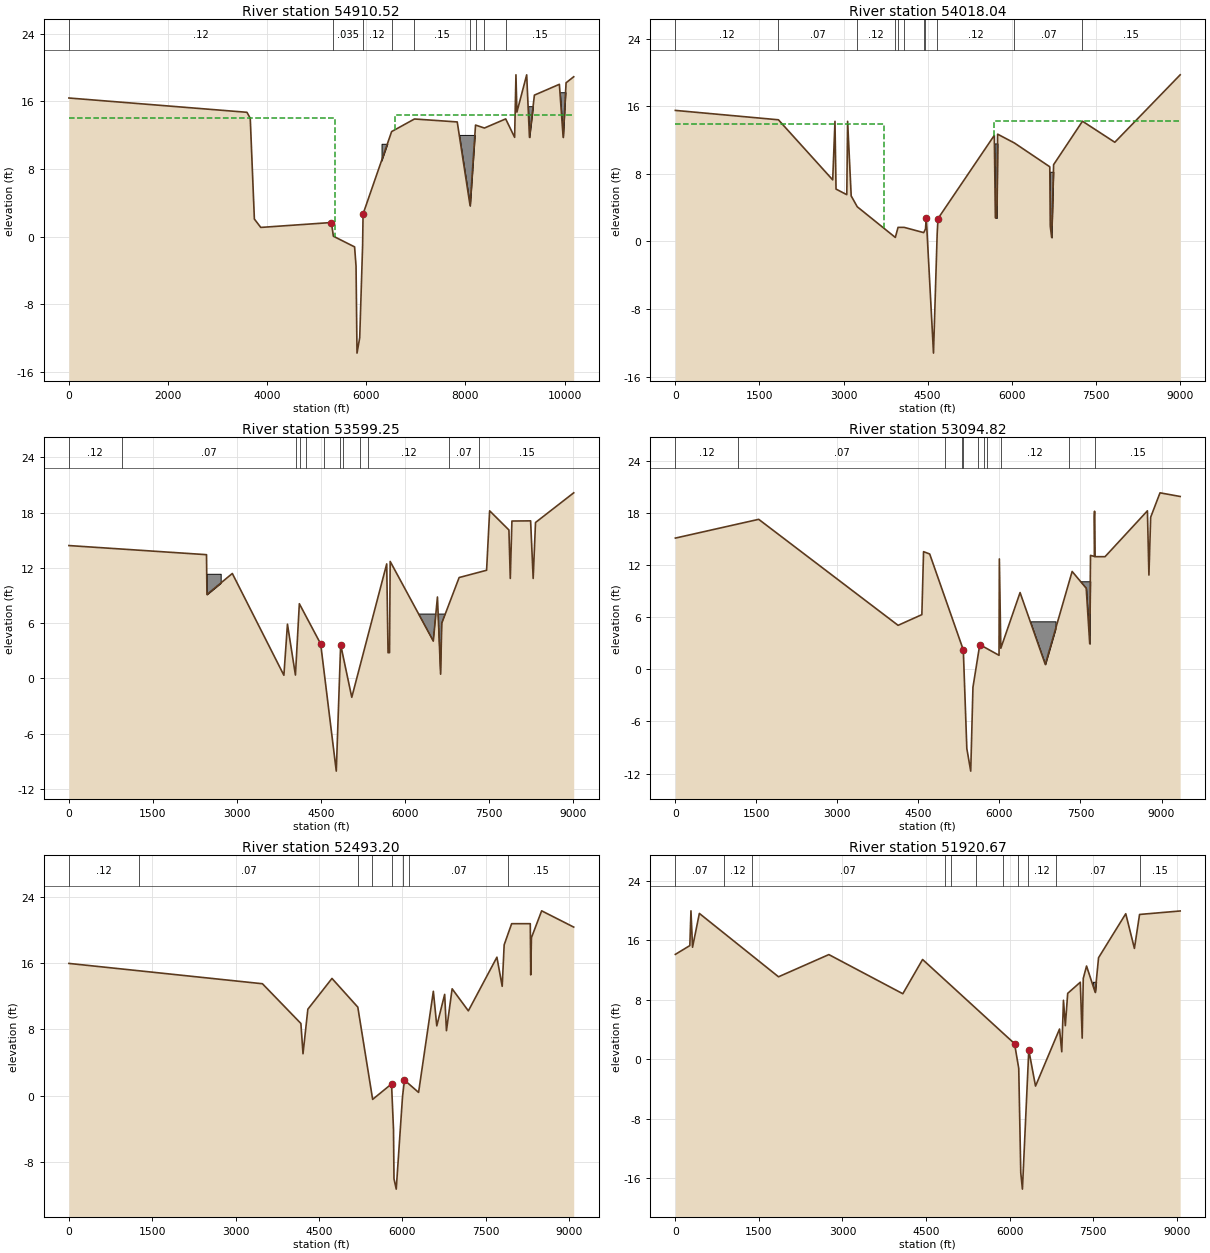
Type RM Length L Ch R = 1 ,54910.52,1195.2,892.49,724.99
XS GIS Cut Line= 4
     3200999.149    13758298.751       3203676.8    13753459.761
     3204122.147    13753140.943     3206158.399    13749574.401
#Sta/Elev= 30
       0   16.39 3592.49    14.7  3658.9   13.99  3742.1    2.08 3871.03    1.09
 5296.73    1.67    5336     .05 5764.03   -1.21 5793.39   -3.48 5812.93  -13.77
 5867.41  -11.95 5926.09    -.98 5935.08    2.68 6511.32   12.42 6972.36   13.91
 7835.17   13.56 8094.48    3.65 8204.29   13.19 8383.42   12.84 8812.63   13.92
 8992.97   11.74 9019.77   19.13 9038.88   14.72 9236.32   19.13 9292.53   11.74
 9392.02   16.73 9896.01   18.01    9972   11.7410031.11   18.1910185.01    18.9
#Mann= 9 ,-1 , 0
       0     .12       0    5336    .035       0 5926.09     .12       0
 6511.32     .07       0 6972.36     .15       0 8094.48     .07       0
 8204.29     .15       0 8383.42     .07       0 8812.63     .15       0
#XS Ineff= 2 ,-1
       0 5369.33      14 6572.2910185.01   14.42
Permanent Ineff=
       F       F
#Block Obstruct= 4 ,-1
 6307.68 6715.68   10.98 7767.94 8244.27   12.03 9141.98 9490.08   15.42
 9709.9210058.02   17.07
Bank Sta=5296.73,5935.08
XS Rating Curve= 0
Vertical n Elevations= 2
       5      12
Vertical n for Station=0
     .12     .24
Vertical n for Station=5336
    .035    .035
Vertical n for Station=5926.09
     .12     .24
Vertical n for Station=6511.32
     .07      .1
Vertical n for Station=6972.36
     .15     .15
Vertical n for Station=8094.48
     .07      .1
Vertical n for Station=8204.29
     .15     .15
Vertical n for Station=8383.42
     .07      .1
Vertical n for Station=8812.63
     .15     .15
Vertical n Flow= 0
Exp/Cntr=.5,.3

Type RM Length L Ch R = 1 ,54018.04,1245.14,418.78,325.45
XS GIS Cut Line= 6
     3202024.247    13757589.462     3204193.565    13754773.333
     3204502.002    13754095.261     3204667.897    13753557.342
     3204660.224    13753236.104     3206564.182    13749922.216
#Sta/Elev= 30
       0   15.51 1838.12    14.4 2806.88    7.29 2847.29   14.22 2866.19     6.2
 3058.04    5.54 3072.84   14.22 3136.85    5.39 3244.56    4.11 3924.07     .48
 3972.55    1.67 4081.91    1.67 4430.43    1.05 4462.33    1.48 4476.31    2.81
 4605.07  -13.21  4670.7     .91 4685.19    2.71 5689.91   12.56 5708.88     2.8
 5735.92     2.8 5748.99    12.7 6049.69   11.65  6679.7    8.84 6688.49    1.81
  6713.3     .47  6747.9    9.09    7263   14.23 7839.83   11.74 9005.86   19.72
#Mann= 11 ,-1 , 0
       0     .12       0 1838.12     .07       0 3244.56     .12       0
 3924.07    .035       0 3972.55     .12       0 4081.91    .035       0
 4430.43     .12       0 4462.33    .035       0  4670.7     .12       0
 6049.69     .07       0    7263     .15       0
#XS Ineff= 2 ,-1
 5676.12 9005.86   14.31       0 3715.19   13.88
Permanent Ineff=
       F       F
#Block Obstruct= 2 ,-1
 5633.59 5832.06    11.6  6137.4 6961.83    8.25
Bank Sta=4476.31,4685.19
XS Rating Curve= 0
Vertical n Elevations= 2
       5      12
Vertical n for Station=0
     .12     .24
Vertical n for Station=1838.12
     .07      .1
Vertical n for Station=3244.56
     .12     .24
Vertical n for Station=3924.07
    .035    .035
Vertical n for Station=3972.55
     .12     .24
Vertical n for Station=4081.91
    .035    .035
Vertical n for Station=4430.43
     .12     .24
Vertical n for Station=4462.33
    .035    .035
Vertical n for Station=4670.7
     .12     .24
Vertical n for Station=6049.69
     .07      .1
Vertical n for Station=7263
     .15     .15
Vertical n Flow= 0
Exp/Cntr=.5,.3

Type RM Length L Ch R = 1 ,53599.25,589.22,504.43,517.09
XS GIS Cut Line= 6
     3202498.376    13757656.528      3204989.63    13754663.531
      3205053.74    13754150.946     3204938.316    13753530.899
      3204989.63     13752989.05     3206767.074    13750067.139
#Sta/Elev= 30
       0   14.42 2455.04   13.43 2462.39    9.11 2915.34   11.39 3835.38     .35
 3898.96    5.89 4041.56     .37 4111.04    8.11 4491.69    3.75 4770.12  -10.05
 4848.14    3.67 5046.54   -2.04  5669.8   12.43 5693.43     2.8 5720.36     2.8
 5731.49    12.7 6500.81    4.06 6574.83    8.84 6631.21     .47 6652.14       6
 6961.74   10.95 7451.53   11.74 7505.93   18.19 7849.87   16.11 7874.37   10.85
 7903.44   17.08 8236.93    17.1 8282.63   10.85 8324.41   16.92 9005.77   20.14
#Mann= 12 ,-1 , 0
       0     .12       0     942     .07       0 4045.12     .12       0
 4118.07     .07       0    4231     .12       0 4556.11    .035       0
 4831.41     .12       0 4896.26    .035       0 5197.14     .07       0
 5329.97     .12       0 6783.32     .07       0 7324.66     .15       0
#Block Obstruct= 2 ,-1
 2195.68 2707.62   11.36 6183.21 6854.96    6.99
Bank Sta=4491.69,4848.14
XS Rating Curve= 0
Exp/Cntr=.3,.1

Type RM Length L Ch R = 1 ,53094.82,362.15,601.62,972.42
XS GIS Cut Line= 6
     3202634.099    13758073.389      3204962.18    13754883.135
     3205602.823    13753883.824     3205283.918    13753345.333
     3205456.289    13752659.644      3207056.92    13750270.031
#Sta/Elev= 30
       0    15.1 1542.76   17.26  4123.1    5.06 4563.29    6.29  4594.6   13.54
 4708.31   13.27 5330.62    2.23 5395.91   -9.13 5468.02  -11.72  5509.2   -2.07
 5635.24    2.84 5991.65    1.61 5997.99    12.7 6024.97    2.42 6381.48    8.83
  6848.5     .56 7345.44   11.26 7605.87    9.33 7671.11    2.94  7685.3   13.11
 7756.15   12.99 7756.16   17.57 7760.54   18.19 7767.66   12.96 7954.65   12.96
    8739   18.24  8766.8   10.85 8799.18    17.5 8972.36   20.31 9345.44   19.89
#Mann= 11 ,-1 , 0
       0     .12       0 1166.59     .07       0 4996.91     .12       0
 5299.24     .07       0 5333.07    .035       0  5598.2     .07       0
 5706.42    .035       0 5776.88     .07       0 6023.42     .12       0
 7282.34     .07       0 7774.01     .15       0
#Block Obstruct= 2 ,-1
 6580.15 7038.17    5.52 7496.18 7740.46   10.13
Bank Sta=5330.62,5635.24
XS Rating Curve= 0
Exp/Cntr=.3,.1

Type RM Length L Ch R = 1 ,52493.20,373.65,572.53,740.76
XS GIS Cut Line= 5
     3202731.043    13758276.972     3205071.982    13754883.135
     3206018.345    13753690.903      3205999.44    13753191.579
     3207810.518    13750878.706
#Sta/Elev= 30
       0   15.95 3482.06    13.5 4173.99    8.71 4212.05    5.06 4299.09   10.43
 4733.25   14.14  5197.9   10.68 5464.88    -.44 5804.74    1.42 5840.12   -4.08
 5848.78  -10.01 5889.28  -11.26  6002.5    -.09  6037.4    1.88 6291.44      .4
 6557.06   12.59 6618.83    8.42  6760.5   12.22 6792.65    7.84 6894.95   12.89
 7186.82   10.23 7700.65    16.7 7795.68   13.19 7831.11   18.19  7965.8   20.74
 8300.97   20.74 8309.13   14.57 8321.73   19.05 8505.66   22.29 9082.32   20.33
#Mann= 8 ,-1 , 0
       0     .12       0 1257.45     .07       0 5207.07     .12       0
 5445.85     .07       0  5813.5    .035       0  6002.5     .12       0
 6119.76     .07       0 7899.44     .15       0
Bank Sta=5804.74,6037.4
XS Rating Curve= 0
Exp/Cntr=.3,.1

Type RM Length L Ch R = 1 ,51920.67,242.74,411.98,350.07
XS GIS Cut Line= 5
     3202837.682    13758519.333     3205231.821     13754833.59
     3206419.028    13753928.344     3206656.469    13753334.741
      3208489.22     13751583.61
#Sta/Elev= 30
       0   14.13  259.63   15.31  279.83   19.99  308.08   15.09  430.65   19.64
 1851.95   11.11 2755.17    14.1 4083.23    8.83    4438   13.44 6088.88    2.11
 6164.15   -1.21  6200.7  -15.27 6230.29  -17.47 6344.61    1.24 6465.53    -3.6
 6896.53    4.08  6936.4    1.02 6966.98    7.95 7000.48    4.53 7043.12    8.88
  7269.1   10.38 7303.32    2.86 7322.54   10.89 7381.53   12.56 7536.56    9.02
 7597.05   13.68 8085.44    19.6 8240.71   14.93  8333.1    19.5  9062.2   19.97
#Mann= 11 ,-1 , 0
       0     .07       0   870.7     .12       0 1372.65     .07       0
 4831.88     .12       0 4947.33     .07       0 5404.52     .12       0
 5873.12     .07       0 6149.88    .035       0  6325.6     .12       0
 6837.98     .07       0 8344.84     .15       0
#Block Obstruct= 1 ,-1
 7498.59 7625.11   10.44
Bank Sta=6088.88,6344.61
XS Rating Curve= 0
Exp/Cntr=.3,.1

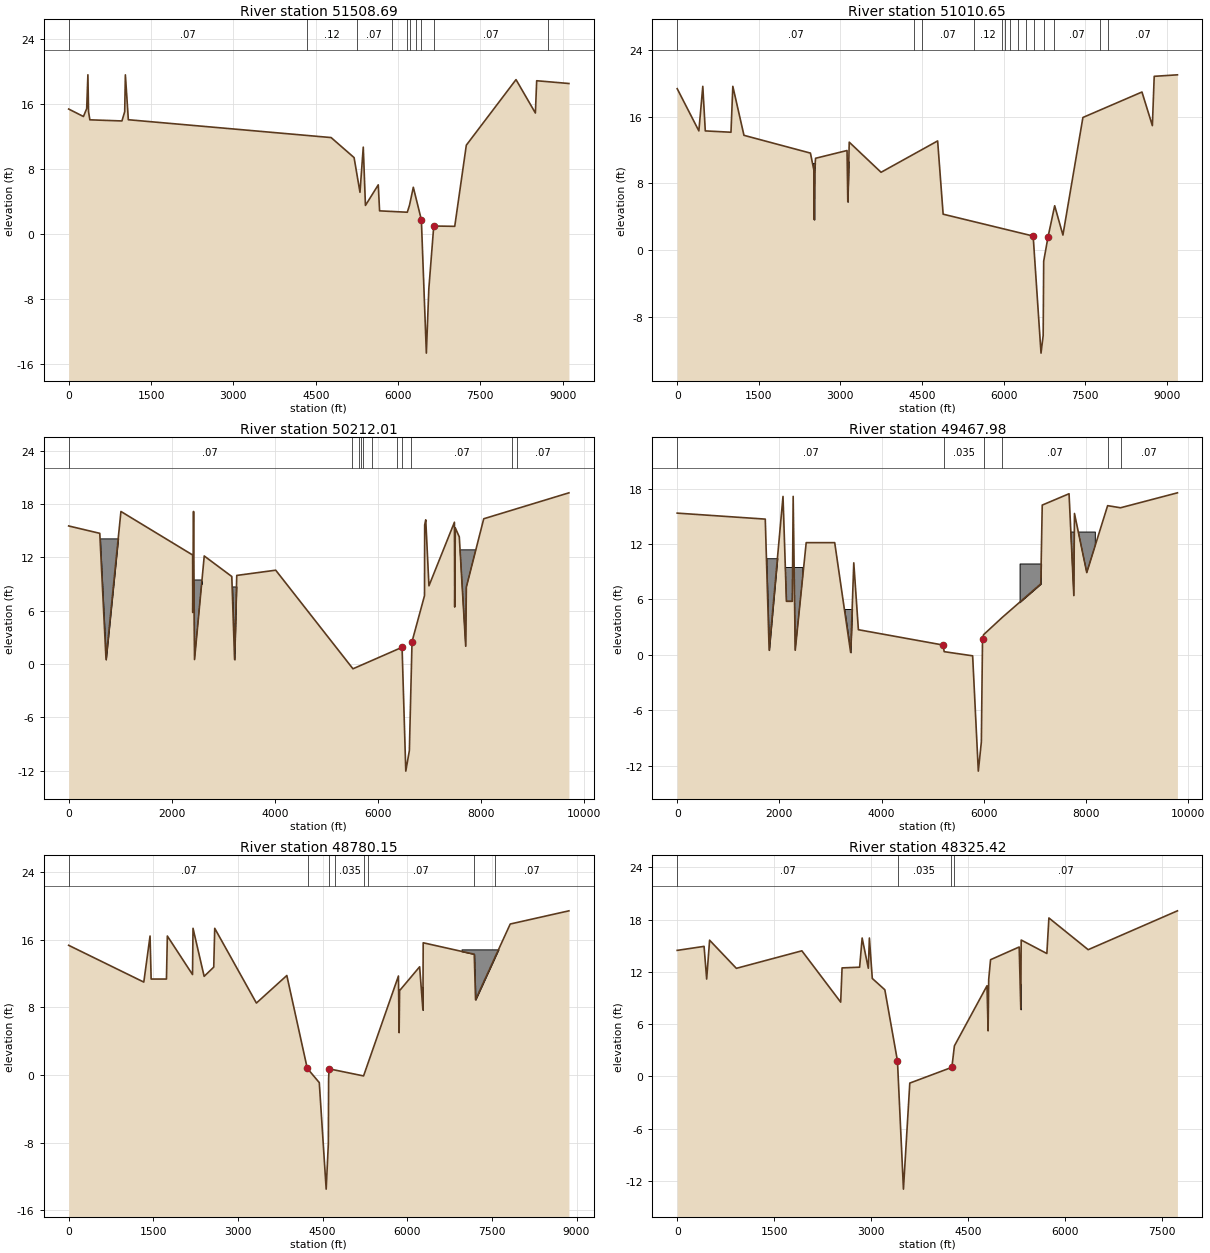
Type RM Length L Ch R = 1 ,51508.69,160.77,498.05,680.48
XS GIS Cut Line= 5
     3203012.182    13758742.306     3205320.861     13754922.63
      3206841.97    13753987.705     3207053.489    13753436.048
     3208622.781    13751791.372
#Sta/Elev= 30
       0   15.42  269.07    14.5  328.18   15.47  350.24   19.64  361.79   15.09
  385.91   14.09  970.15   13.95 1020.64   15.09 1032.68   19.64 1086.99    14.1
 4780.94    11.9 5199.25    9.43 5306.57    5.15 5366.47   10.72 5406.14    3.53
 5639.57    6.07 5663.82    2.86 6168.56    2.69 6208.75    3.55 6278.05    5.77
 6424.63    1.76 6515.69  -14.69 6560.39   -6.79 6650.44     .99  7032.8     .95
 7243.59   10.96 8149.02   19.05 8501.97   14.93 8525.53   18.91 9112.69   18.57
#Mann= 10 ,-1 , 0
       0     .07       0 4342.93     .12       0 5246.63     .07       0
 5881.61     .12       0 6168.56     .07       0 6208.75     .12       0
 6318.83     .07       0 6424.63    .035       0 6657.46     .07       0
 8723.22     .15       0
Bank Sta=6424.63,6650.44
XS Rating Curve= 0
Exp/Cntr=.3,.1

Type RM Length L Ch R = 1 ,51010.65,201.05,798.64,629.34
XS GIS Cut Line= 6
     3203144.006    13758849.457     3205498.942    13755100.711
      3206609.21    13754251.773      3207186.28    13754071.549
     3207652.801    13753787.818     3208964.571    13751994.972
#Sta/Elev= 30
       0   19.36  398.47    14.3  470.81   19.64  516.57    14.3  988.95   14.14
 1022.88   19.64 1227.71   13.77 2449.65   11.64 2512.79    9.61 2519.61    3.67
 2526.63    9.61 2543.98   11.02 3122.67   11.95 3136.57     5.8 3163.02   12.95
 3748.14    9.34 4788.33    13.1 4889.31    4.32 6544.53     1.7 6688.81  -12.33
 6728.38  -10.23 6737.95   -1.31 6818.04     1.6 6940.11    5.33  7091.6    1.82
  7459.1   15.91 8544.82   18.96  8736.1   14.93 8769.84   20.84 9196.77   21.02
#Mann= 14 ,-1 , 0
       0     .07       0  4362.4     .12       0  4505.5     .07       0
 5463.25     .12       0 5972.48     .07       0 6031.34    .035       0
 6116.04     .07       0 6269.62    .035       0 6408.77     .12       0
 6554.91    .035       0  6738.2     .12       0 6929.95     .07       0
 7770.81     .12       0 7915.94     .07       0
#Block Obstruct= 2 ,-1
 2442.75 2595.42   10.45  3068.7 3221.37   10.65
Bank Sta=6544.53,6818.04
XS Rating Curve= 0
Exp/Cntr=.3,.1

Type RM Length L Ch R = 1 ,50212.01,213.77,744.03,361.23
XS GIS Cut Line= 6
     3203303.015    13759071.917     3205839.569    13755139.435
      3206730.67    13754343.867     3207039.261     13754560.03
     3207470.833    13754792.415     3209258.679    13752422.728
#Sta/Elev= 30
       0   15.54  603.71   14.71  725.05      .5 1014.32   17.17 2406.45   12.27
 2408.06     5.8 2423.63   17.17 2442.57      .5 2631.28   12.16 3166.06    9.85
 3220.21      .5 3262.36    9.97 4018.43   10.56 5518.05    -.54 6471.03    1.88
 6543.21  -12.06  6612.8   -9.74 6664.39    2.52 6906.51    7.69 6909.89   15.65
 6930.47   16.23 6992.62     8.8 7487.47   15.96 7492.49    6.42 7504.49   15.32
 7581.69   14.31 7706.27       2 7718.84    8.66 8056.21   16.35 9709.55   19.27
#Mann= 11 ,-1 , 0
       0     .07       0 5492.31    .035       0 5630.28     .07       0
 5668.92     .12       0 5714.46     .07       0 5895.93    .035       0
    6375     .12       0 6471.03    .035       0 6653.37     .07       0
 8599.95     .12       0 8695.97     .07       0
#Block Obstruct= 5 ,-1
  488.55 1007.63   14.14 2290.08 2580.15    9.46 2580.15 3007.63    9.37
 3145.04 3343.51    8.73 7419.85 7984.73   12.85
Bank Sta=6471.03,6664.39
XS Rating Curve= 0
Exp/Cntr=.3,.1

Type RM Length L Ch R = 1 ,49467.98,1169.18,687.83,307.56
XS GIS Cut Line= 6
     3203433.851    13759168.287      3205776.32    13755548.227
     3206342.108    13754929.949     3206944.773    13755349.511
     3207174.919    13755512.841      3209299.36    13752577.292
#Sta/Elev= 30
       0   15.36 1723.76   14.71 1799.72      .5 2070.94   17.17 2138.06     5.8
 2253.32     5.8 2269.72   17.17 2310.22      .5 2524.72   12.16 3082.71   12.16
 3394.75     .26 3455.88    9.97  3546.3    2.72 5203.05    1.06 5225.35     .34
  5782.3    -.11  5893.2  -12.61 5952.79   -9.45 5975.59    1.76 5996.43    2.18
 6363.16    4.06 7115.65    7.69 7144.24   16.23 7668.89   17.46 7762.46    6.42
  7775.1   15.32  8015.6    8.91 8423.98   16.17 8676.62   15.94  9790.1   17.56
#Mann= 6 ,-1 , 0
       0     .07       0 5225.35    .035       0 5996.43     .12       0
 6363.16     .07       0 8423.98     .12       0 8676.62     .07       0
#Block Obstruct= 5 ,-1
 1679.39 2015.27   10.47 2076.34 2458.02    9.46 3099.24 3465.65    4.97
    6701 7222.59     9.9 7618.32 8183.21   13.31
Bank Sta=5203.05,5975.59
XS Rating Curve= 0
Exp/Cntr=.3,.1

Type RM Length L Ch R = 1 ,48780.15,654.83,454.73,282.18
XS GIS Cut Line= 4
     3203781.666    13759342.194     3206370.563    13755982.793
     3207067.717    13755868.972     3209400.821    13752722.056
#Sta/Elev= 30
       0   15.35 1331.34      11 1442.17   16.45 1461.39   11.36 1732.88   11.36
 1748.65   16.45 2194.78   11.89 2203.58   17.36 2400.69   11.68 2570.71   12.77
 2588.34   17.36 3326.84    8.52 3865.94   11.78 4228.12      .8 4441.17    -.89
 4563.26  -13.49 4601.64   -8.11 4606.56    -.39 4614.53     .74 5225.81     -.1
 5843.92   11.72 5856.22    5.02 5864.41    9.99  6219.5   12.81 6277.79    7.69
 6282.55   15.65 7187.35    14.3  7210.3    8.91 7825.12   17.87 8865.06   19.43
#Mann= 8 ,-1 , 0
       0     .07       0 4243.53    .035       0 4614.53     .12       0
 4727.03    .035       0 5226.93     .12       0 5295.99     .07       0
 7187.35     .12       0 7563.23     .07       0
#Block Obstruct= 2 ,-1
 6178.39 6363.99   10.44 6961.83 7618.32   14.87
Bank Sta=4228.12,4614.53
XS Rating Curve= 0
Exp/Cntr=.3,.1

Type RM Length L Ch R = 1 ,48325.42,644.52,616.41,501.53
XS GIS Cut Line= 4
     3204854.094    13759110.318      3206760.35       13756466.
     3207101.672    13756005.957     3209458.988    13752896.556
#Sta/Elev= 30
       0   14.46  415.51   14.92  455.75   11.17  501.02   15.63  914.85    12.4
 1927.84   14.41 2528.03    8.52 2549.33   12.45 2820.85   12.53 2859.72   15.88
 2955.02   12.41 2971.65   15.88 3016.55   11.24  3210.6    9.94 3405.68    1.78
 3498.26  -12.94 3596.52    -.77 4247.18    1.04  4286.2     3.5 4790.36    10.4
 4807.22    5.23 4816.53   11.12 4845.02   13.39 5287.94   14.85 5312.89    7.69
  5318.7   15.65 5715.72    14.1 5747.36   18.18 6354.79   14.54 7734.59      19
#Mann= 4 ,-1 , 0
       0     .07       0  3412.5    .035       0 4228.42     .12       0
  4286.2     .07       0
#Block Obstruct= 1 ,-1
 5215.02 5424.35   10.63
Bank Sta=3405.68,4247.18
XS Rating Curve= 0
Exp/Cntr=.5,.3

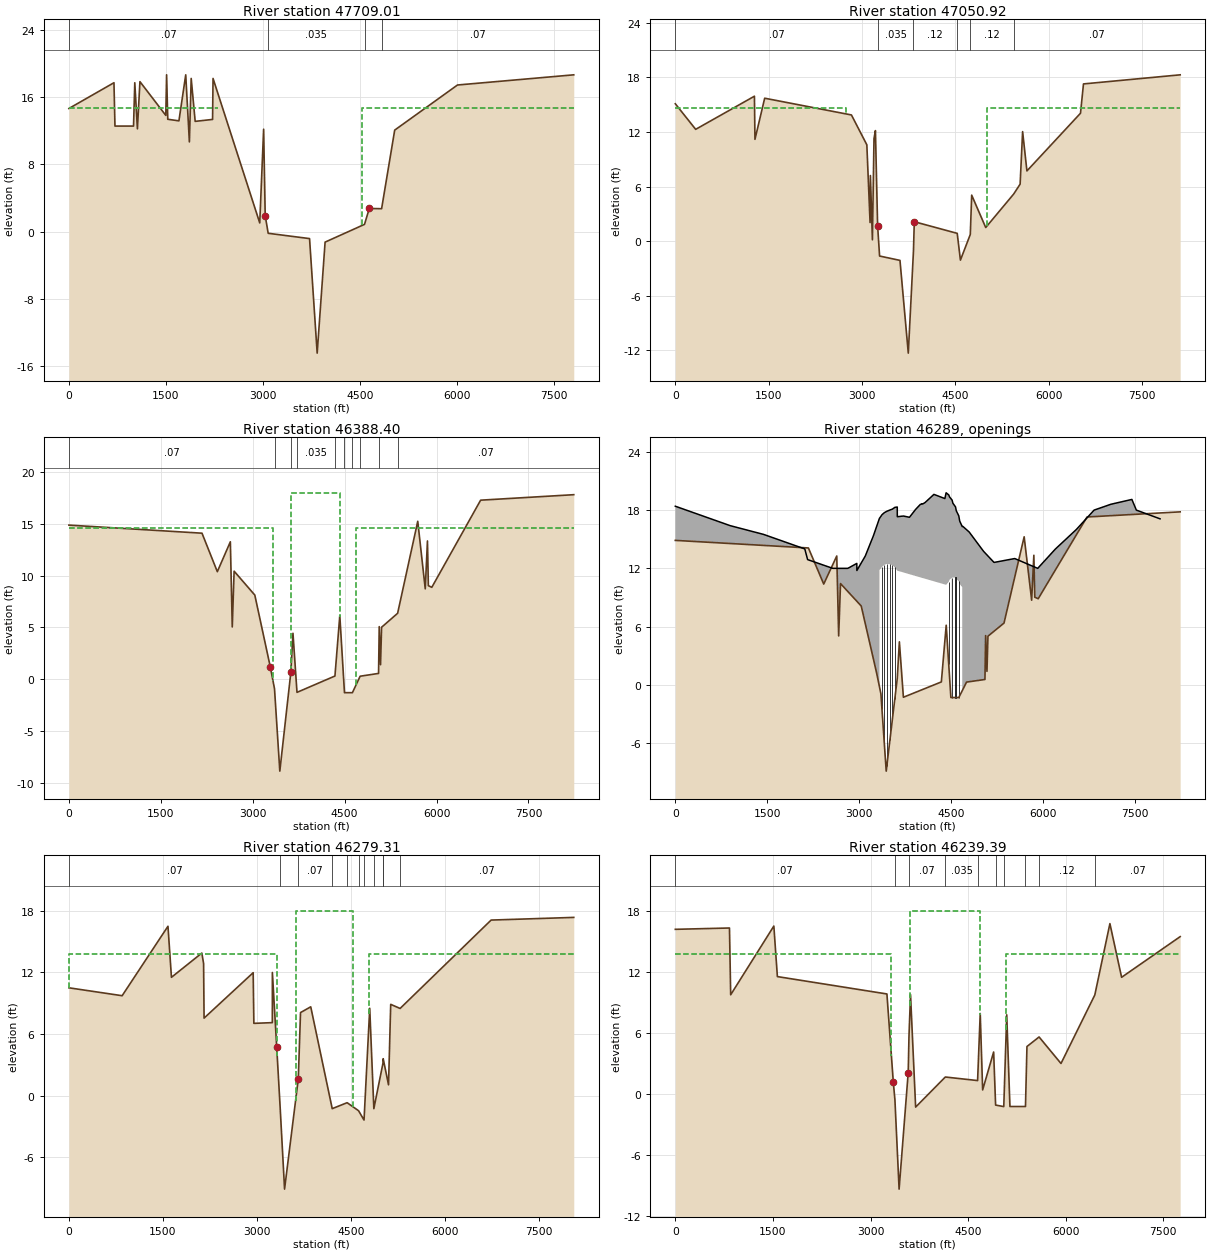
Type RM Length L Ch R = 1 ,47709.01,291.12,658.09,124.94
XS GIS Cut Line= 5
     3205154.654    13759566.333     3207279.753    13756762.801
     3207621.075    13756302.759     3208310.276    13754608.877
      3209507.46    13753158.306
#Sta/Elev= 30
       0   14.62  696.12   17.68  711.48   12.53  998.58   12.53 1017.87   17.68
 1058.37    12.2 1097.47   17.81 1496.97    13.8 1509.31   18.62 1527.53   13.34
 1699.78   13.15 1804.98   18.62 1861.47   10.65 1889.32   18.19 1950.84   13.09
 2219.83   13.32 2226.92   18.19 2948.49    1.02 3008.65   12.16 3032.88    1.89
 3078.89    -.21 3717.98    -.84 3835.82  -14.45 3958.18   -1.26 4567.19     .85
 4640.99    2.74 4831.42    2.71 5033.66   12.05 6003.53   17.41 7800.29   18.62
#Mann= 4 ,-1 , 0
       0     .07       0 3078.89    .035       0 4567.19     .12       0
 4831.42     .07       0
#XS Ineff= 2 ,-1
       0 2308.89   14.65  4531.5 7800.29   14.65
Permanent Ineff=
       F       F
Bank Sta=3032.88,4640.99
XS Rating Curve= 0
Exp/Cntr=.5,.3

Type RM Length L Ch R = 1 ,47050.92,534.62,662.52,256.06
XS GIS Cut Line= 6
      3205222.76     13759917.34     3207368.793    13757089.283
     3207712.702    13757083.062     3207695.275    13756391.799
     3208438.873    13754673.176     3209483.723     13753435.43
#Sta/Elev= 30
       0   15.11  327.14    12.3 1270.93   15.94  1279.5    11.2 1435.71   15.72
 2829.53   13.88 3076.94    10.6 3128.91    2.06 3134.09    7.22 3166.21     .17
 3191.97   11.29 3214.82   12.16 3249.89    1.72  3281.6   -1.62 3609.15    -2.1
 3742.82  -12.29 3826.06   -1.05 3839.15    2.15 4528.93     .87 4580.23   -2.07
 4738.98     .75 4761.33    5.07 4986.71    1.51 5435.87    5.19 5539.44    6.28
 5579.36   12.05 5648.58    7.73 6509.34   14.07 6557.18   17.29 8110.52   18.29
#Mann= 6 ,-1 , 0
       0     .07       0 3249.89    .035       0 3826.06     .12       0
 4528.93    .035       0 4738.98     .12       0 5435.87     .07       0
#XS Ineff= 2 ,-1
       0 2734.14   14.59 5009.14 8110.52   14.59
Permanent Ineff=
       F       F
Bank Sta=3249.89,3839.15
XS Rating Curve= 0
Exp/Cntr=.5,.3

Type RM Length L Ch R = 1 ,46388.40,154.16,109.08,269.89
XS GIS Cut Line= 6
     3205346.709    13760248.062     3207757.711    13757540.005
     3208105.109    13756875.964     3208295.505    13755194.585
     3208620.452     13754544.69     3209523.084    13753490.416
#Sta/Elev= 30
       0   14.88 2172.02    14.1 2422.12   10.38 2634.73   13.27 2665.89    5.04
 2696.07   10.43 3033.94    8.12 3285.59    1.21 3355.29    -.93 3441.91   -8.89
 3622.02     .66 3656.53    4.43 3722.23   -1.28 4341.55      .3 4420.86    6.14
 4497.17   -1.31 4626.55   -1.31 4752.87     .28  5053.3     .55 5064.13    5.07
 5085.86    1.39 5102.44    5.01 5364.31    6.36    5693   15.25 5815.26    8.72
 5851.16   13.35 5865.97    9.03 5922.28    8.87 6719.08   17.29 8238.97   17.82
#Mann= 10 ,-1 , 0
       0     .07       0 3355.29    .035       0 3622.02     .07       0
 3722.23    .035       0 4341.55     .07       0 4497.17    .035       0
 4626.55     .07       0 4752.87    .035       0  5053.3     .12       0
 5364.31     .07       0
#XS Ineff= 3 ,-1
       0    3332   14.58 3623.17 4419.63      18 4682.87 8238.97   14.58
Permanent Ineff=
       F       F       F
Bank Sta=3285.59,3622.02
XS Rating Curve= 0
Exp/Cntr=.5,.3

Type RM Length L Ch R = 4 ,46289   ,,,
BEGIN DESCRIPTION:
SH3
END DESCRIPTION:
Bridge Culvert--1,0,-1,-1, 0
Deck Dist Width WeirC Skew NumUp NumDn MinLoCord MaxHiCord MaxSubmerge Is_Ogee
5,98,2.6,0, 56, 56, , , .95, 0, 0,0,,
       0     895    1439    2113    2159    2570    2812    2833    2962    2963
    3100    3231    3331    3332    3372    3412    3452    3502    3542    3582
    3622    3623    3723    3821    3921    3999    4021    4022    4042    4076
    4220    4399    4419    4420    4462    4476    4517    4530    4573    4585
    4626    4641    4682    4695    4796    5031    5201    5539    5914    6204
    6544    6834    7107    7451    7524    7911
    18.4    16.4    15.5      14    12.9      12      12   12.06   12.51   11.78
   13.27   15.33   17.15   17.15   17.52   17.74   17.88   18.01    18.1   18.28
   18.32   17.32   17.39   17.26   18.07   18.59   18.62   18.65   18.65   18.78
   19.62   19.19   19.78   19.78   19.57   19.35   19.03   18.71   18.33   17.94
   17.41   16.87   16.31   16.31   15.74   13.75   12.61   13.01      12      14
      16      18    18.6    19.1      18    17.1
                                                                                
                           11.82   12.14   12.36   12.46   12.42   12.33    12.1
   11.76
                            10.3   10.62   10.83   11.04   11.05   11.06   10.88
   10.69   10.38   10.07
                                                
       0     887    1431    2105    2151    2562    2804    2825    2954    2955
    3092    3223    3323    3324    3364    3404    3444    3494    3534    3574
    3614    3615    3715    3813    3913    3991    4013    4113    4156    4190
    4334    4513    4533    4534    4576    4590    4631    4644    4687    4699
    4740    4755    4796    4809    4910    5145    5315    5653    6028    6318
    6658    6948    7221    7565    7638    8025
    18.4    16.4    15.5      14    12.9      12      12   12.06   12.51   11.78
   13.27   15.33   17.15   17.15   17.52   17.74   17.88   18.01    18.1   18.28
   18.32   18.32   17.39   17.26   18.07   18.59   18.62   18.65   18.65   18.78
   19.62   19.19   19.78   19.78   19.57   19.35   19.03   18.71   18.33   17.94
   17.41   16.87   16.31   16.31   15.74   13.75   12.61   13.01      12      14
      16      18    18.6    19.1      18    17.1
                                                                                
                           11.82   12.14   12.36   12.46   12.42   12.33    12.1
   11.76
                            10.3   10.62   10.83   11.04   11.05   11.06   10.88
   10.69   10.38   10.07
                                                
Pier Skew, UpSta & Num, DnSta & Num=  ,3372, 2 ,3364, 2 , 0 , 0 , 0 ,,
    1.33    1.33
     -30      14
    1.33    1.33
     -30      14
Pier Skew, UpSta & Num, DnSta & Num=  ,3412, 2 ,3404, 2 , 0 , 0 , 0 ,,
    1.33    1.33
     -30      14
    1.33    1.33
     -30      14
Pier Skew, UpSta & Num, DnSta & Num=  ,3452, 2 ,3444, 2 , 0 , 0 , 0 ,,
    1.33    1.33
     -30      14
    1.33    1.33
     -30      14
Pier Skew, UpSta & Num, DnSta & Num=  ,3502, 2 ,3494, 2 , 0 , 0 , 0 ,,
    1.33    1.33
     -30      14
    1.33    1.33
     -30      14
Pier Skew, UpSta & Num, DnSta & Num=  ,3542, 2 ,3534, 2 , 0 , 0 , 0 ,,
    1.33    1.33
     -30      14
    1.33    1.33
     -30      14
Pier Skew, UpSta & Num, DnSta & Num=  ,3582, 2 ,3574, 2 , 0 , 0 , 0 ,,
    1.33    1.33
     -30      14
    1.33    1.33
     -30      14
Pier Skew, UpSta & Num, DnSta & Num=  ,4462, 2 ,4576, 2 , 0 , 0 , 0 ,,
    1.67    1.67
     -30      14
    1.67    1.67
     -30      14
Pier Skew, UpSta & Num, DnSta & Num=  ,4517, 2 ,4631, 2 , 0 , 0 , 0 ,,
    1.67    1.67
     -30      14
    1.67    1.67
     -30      14
Pier Skew, UpSta & Num, DnSta & Num=  ,4573, 2 ,4687, 2 , 0 , 0 , 0 ,,
    1.67    1.67
     -30      14
    1.67    1.67
     -30      14
Pier Skew, UpSta & Num, DnSta & Num=  ,4626, 2 ,4740, 2 , 0 , 0 , 0 ,,
    1.67    1.67
     -30      14
    1.67    1.67
     -30      14
Abutment Skew #Up #Dn= , 2 , 2
    3332    3362
      10      -1
    3324    3355
      10      -1
Abutment Skew #Up #Dn= , 2 , 2
    3593    3623
      -1      10
    3585    3615
      -1      10
Abutment Skew #Up #Dn= , 2 , 2
    4420    4445
       9       0
    4534    4559
       9       0
Abutment Skew #Up #Dn= , 2 , 2
    4658    4683
       0       9
    4771    4796
       0       9
BR Coef=-1 , 1 , 1 ,1.25, 0 ,,,.8,-1,2,0,
WSPro=,,,, 1 ,,,, 0 ,,,, 0 ,,,,-1 ,-1 ,-1 , 0 , 0 , 0 , 0 , 0
BR Coef=-1 , 0 , 0 ,1.25, 0 ,,,.8,-1,2,0,
WSPro=,,,, 1 ,,,, 0 ,,,, 0 ,,,,-1 ,-1 ,-1 , 0 , 0 , 0 , 0 , 0
BC Mult= 3 ,0,4100,0,4100
BC Mult= 3 ,4100,8238.97,4100,8056.71
BC Design=,, 0 ,, 0 ,,,,,,
BC HTab HWMax=18.95

Type RM Length L Ch R = 1 ,46279.31,19.4,39.92,677.79
XS GIS Cut Line= 6
      3205457.63    13760350.419     3208237.736    13757108.165
     3208266.743    13756567.243     3208483.252    13755266.796
     3208674.721     13754774.23     3209537.526    13753714.269
#Sta/Elev= 30
       0   10.51  849.41    9.74 1580.91    16.5 1636.44   11.53  2121.3   13.89
 2149.29   12.88 2156.99    7.56  2940.6   11.98 2951.49    7.05  3246.3    7.12
 3246.97      12 3316.21    4.74 3373.49   -1.39  3441.5   -9.08  3660.5    1.64
 3696.22     8.1 3859.23    8.66 4202.12   -1.25 4439.81    -.67 4622.37   -1.45
 4709.73   -2.36 4800.65    8.52 4866.38   -1.25 5011.76    3.17 5015.39    3.61
 5100.59    1.07 5135.49     8.9 5285.38     8.5 6737.77    17.1 8056.71   17.36
#Mann= 11 ,-1 , 0
       0     .07       0 3373.49    .035       0  3660.5     .07       0
 4202.12    .035       0 4439.81     .07       0 4622.37    .035       0
 4709.73     .07       0 4866.38    .035       0 5011.76     .07       0
 5015.39     .12       0 5285.38     .07       0
#XS Ineff= 3 ,-1
 3617.14 4533.75      18       0    3324   13.83 4796.24 8056.71   13.83
Permanent Ineff=
       F       F       F
Bank Sta=3316.21,3660.5
XS Rating Curve= 0
Exp/Cntr=.5,.3

Type RM Length L Ch R = 1 ,46239.39,72.22,25.25,162.89
XS GIS Cut Line= 6
      3205469.48    13760360.158     3208469.154    13756875.681
      3208691.75    13756703.125      3209017.61    13756212.754
     3210071.884    13754999.617     3210525.029    13754545.803
#Sta/Elev= 30
       0   16.18  832.19   16.31  850.81    9.74 1514.06    16.5 1568.46   11.53
 3251.59    9.82 3349.85    1.14 3374.63    -.59 3438.85   -9.38 3578.78    2.08
 3590.63    5.66 3614.33    9.76 3692.87   -1.31 4148.81    1.65 4645.04     1.3
 4685.37     7.9 4722.65     .38 4891.44    4.11 4921.77   -1.11 5047.26   -1.26
 5092.57    7.77 5141.91   -1.25 5380.84   -1.25  5403.5    4.65 5589.85    5.59
 5926.52    2.98 6446.12    9.72  6678.1   16.74 6857.84   11.46 7757.81   15.46
#Mann= 10 ,-1 , 0
       0     .07       0 3374.63    .035       0 3590.63     .07       0
 4148.81    .035       0 4645.04     .07       0 4921.77    .035       0
 5047.26     .07       0 5380.84     .07       0 5589.85     .12       0
 6446.12     .07       0
#XS Ineff= 3 ,-1
 3608.08  4686.1      18       0 3320.19    13.8 5085.09 7757.81    13.8
Permanent Ineff=
       F       F       F
Bank Sta=3349.85,3578.78
XS Rating Curve= 0
Exp/Cntr=.5,.3