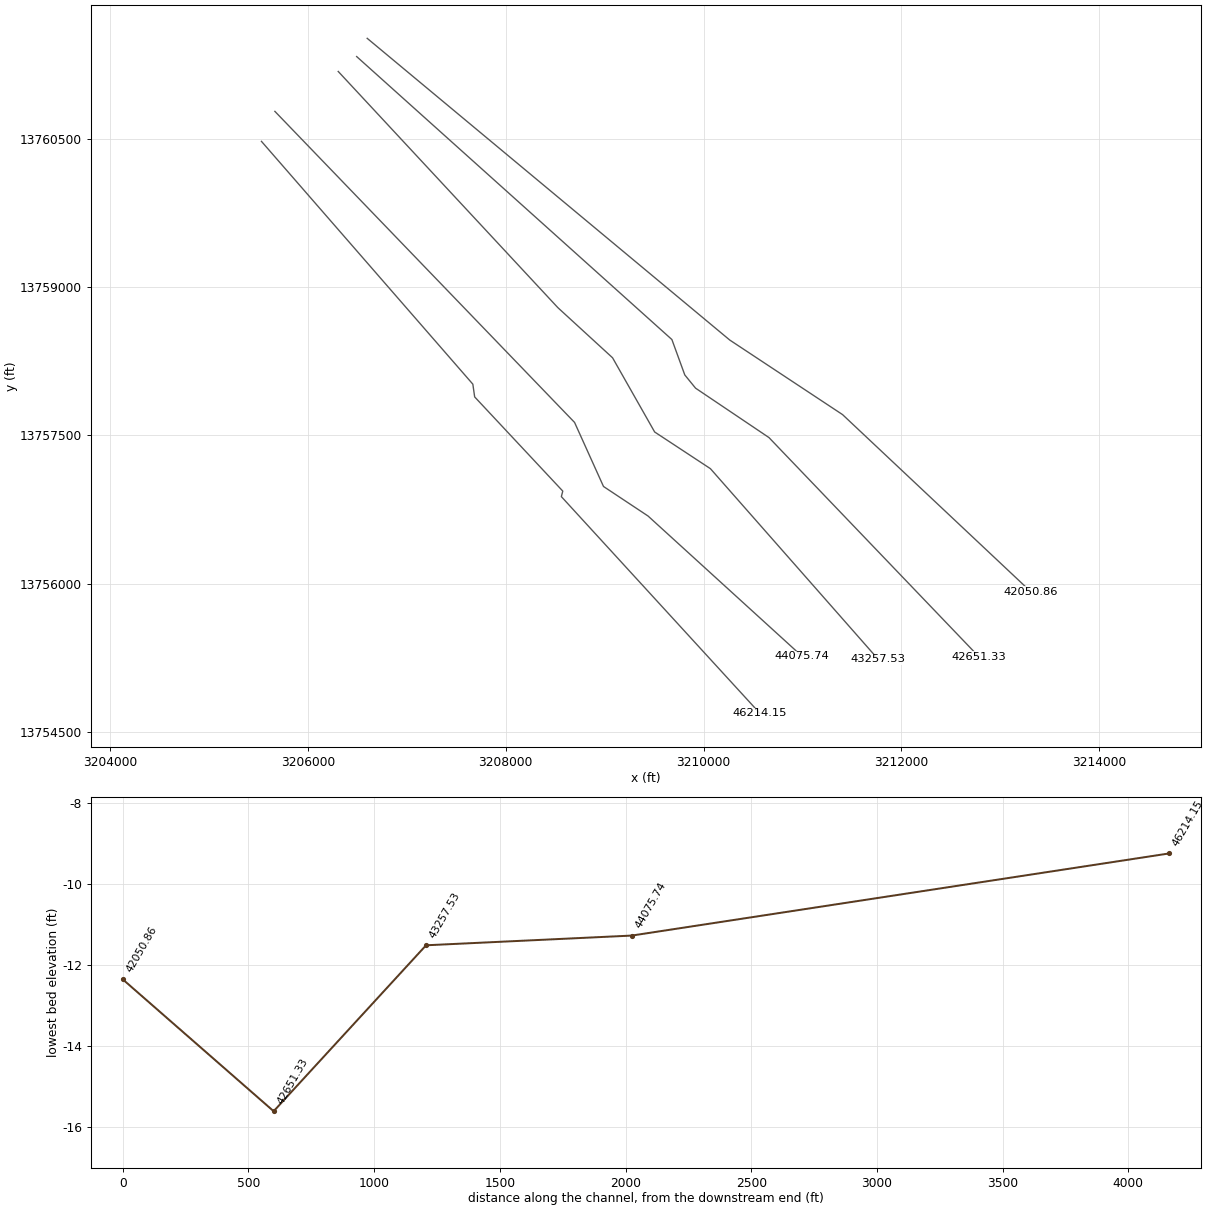
HEC-RAS study A100-00-00.prj: A100-00-00

--- A100-00-00.g01 (geometry) --- (continued)

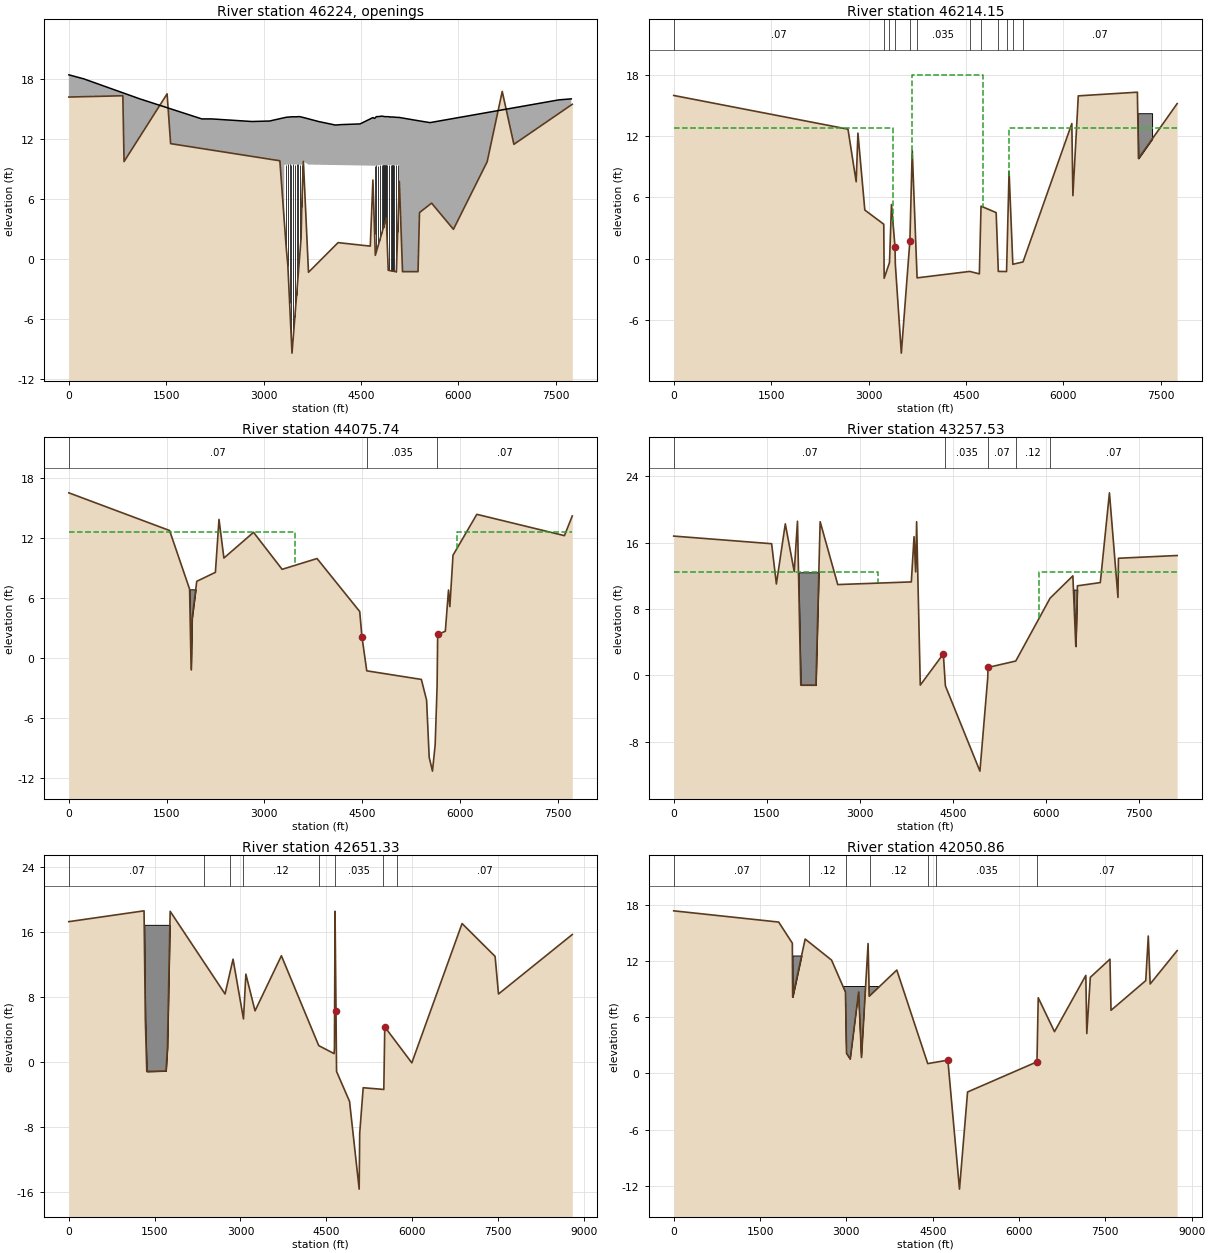
Type RM Length L Ch R = 4 ,46224   ,,,
BEGIN DESCRIPTION:
MKT-RR
END DESCRIPTION:
Bridge Culvert--1,0,-1,-1, 0
Deck Dist Width WeirC Skew NumUp NumDn MinLoCord MaxHiCord MaxSubmerge Is_Ogee
5,17,2.6,0, 48, 48, , , .95, 0, 0,0,,
       0     229    1094    2049    2199    2821    3094    3319    3320    3348
    3375    3402    3429    3456    3483    3510    3537    3564    3589    3607
    3608    3854    4106    4109    4194    4487    4685    4686    4712    4739
    4765    4794    4822    4849    4879    4906    4934    4961    4988    5015
    5042    5067    5086    5087    5394    5565    7550    7742
    18.4      18      16      14      14   13.74   13.79   14.12   14.12   14.16
   14.18   14.19   14.21   14.21   14.21   14.21   14.23   14.22   14.18   14.15
   14.15   13.73   13.39   13.39   13.43    13.5   14.13   14.13   14.05   14.23
   14.23   14.25   14.28   14.25   14.22   14.23   14.21   14.19   14.19   14.18
   14.16   14.15   14.15   14.15   13.81   13.63    15.9      16
                                                                    9.43    9.42
    9.45    9.45    9.44    9.46    9.44    9.46    9.46    9.43    9.42    9.45
                                                            9.33    9.32    9.37
    9.34     9.4    9.43    9.39     9.4    9.38     9.4     9.4    9.42    9.41
    9.37    9.41    9.43
       0     289    1154    2109    2259    2881    3154    3379    3380    3408
    3435    3462    3489    3516    3543    3570    3597    3624    3649    3667
    3668    3914    4166    4169    4267    4560    4758    4759    4785    4812
    4838    4867    4895    4922    4952    4979    5007    5034    5061    5088
    5115    5140    5159    5160    5467    5638    7623    7815
    18.4      18      16      14      14   13.74   13.79   14.12   14.12   14.16
   14.18   14.19   14.21   14.21   14.21   14.21   14.23   14.22   14.18   14.15
   14.15   13.73   13.39   13.39   13.43    13.5   14.13   14.13   14.05   14.23
   14.23   14.25   14.28   14.25   14.22   14.23   14.21   14.19   14.19   14.18
   14.16   14.15   14.15   14.15   13.81   13.63    15.9      16
                                                                    9.43    9.42
    9.45    9.45    9.44    9.46    9.44    9.46    9.46    9.43    9.42    9.45
                                                            9.33    9.32    9.37
    9.34     9.4    9.43    9.39     9.4    9.38     9.4     9.4    9.42    9.41
    9.37    9.41    9.43
Pier Skew, UpSta & Num, DnSta & Num=  ,3348, 2 ,3408, 2 , 0 , 0 , 0 ,,
       2       2
     -30      12
       2       2
     -30      12
Pier Skew, UpSta & Num, DnSta & Num=  ,3375, 2 ,3435, 2 , 0 , 0 , 0 ,,
       2       2
     -30      12
       2       2
     -30      12
Pier Skew, UpSta & Num, DnSta & Num=  ,3402, 2 ,3462, 2 , 0 , 0 , 0 ,,
       2       2
     -30      12
       2       2
     -30      12
Pier Skew, UpSta & Num, DnSta & Num=  ,3429, 2 ,3489, 2 , 0 , 0 , 0 ,,
       2       2
     -30      12
       2       2
     -30      12
Pier Skew, UpSta & Num, DnSta & Num=  ,3456, 2 ,3516, 2 , 0 , 0 , 0 ,,
       2       2
     -30      12
       2       2
     -30      12
Pier Skew, UpSta & Num, DnSta & Num=  ,3483, 2 ,3543, 2 , 0 , 0 , 0 ,,
       2       2
     -30      12
       2       2
     -30      12
Pier Skew, UpSta & Num, DnSta & Num=  ,3510, 2 ,3570, 2 , 0 , 0 , 0 ,,
       2       2
     -30      12
       2       2
     -30      12
Pier Skew, UpSta & Num, DnSta & Num=  ,3537, 2 ,3597, 2 , 0 , 0 , 0 ,,
       2       2
     -30      12
       2       2
     -30      12
Pier Skew, UpSta & Num, DnSta & Num=  ,3564, 2 ,3624, 2 , 0 , 0 , 0 ,,
       2       2
     -30      12
       2       2
     -30      12
Pier Skew, UpSta & Num, DnSta & Num=  ,3589, 2 ,3649, 2 , 0 , 0 , 0 ,,
       2       2
     -30      12
       2       2
     -30      12
Pier Skew, UpSta & Num, DnSta & Num=  ,4712, 2 ,4785, 2 , 0 , 0 , 0 ,,
       2       2
     -30      12
       2       2
     -30      12
Pier Skew, UpSta & Num, DnSta & Num=  ,4739, 2 ,4812, 2 , 0 , 0 , 0 ,,
       2       2
     -30      12
       2       2
     -30      12
Pier Skew, UpSta & Num, DnSta & Num=  ,4765, 2 ,4838, 2 , 0 , 0 , 0 ,,
       2       2
     -30      12
       2       2
     -30      12
Pier Skew, UpSta & Num, DnSta & Num=  ,4794, 2 ,4867, 2 , 0 , 0 , 0 ,,
       2       2
     -30      12
       2       2
     -30      12
Pier Skew, UpSta & Num, DnSta & Num=  ,4822, 2 ,4895, 2 , 0 , 0 , 0 ,,
       2       2
     -30      12
       2       2
     -30      12
Pier Skew, UpSta & Num, DnSta & Num=  ,4849, 2 ,4922, 2 , 0 , 0 , 0 ,,
       2       2
     -30      12
       2       2
     -30      12
Pier Skew, UpSta & Num, DnSta & Num=  ,4879, 2 ,4952, 2 , 0 , 0 , 0 ,,
       2       2
     -30      12
       2       2
     -30      12
Pier Skew, UpSta & Num, DnSta & Num=  ,4906, 2 ,4979, 2 , 0 , 0 , 0 ,,
       2       2
     -30      12
       2       2
     -30      12
Pier Skew, UpSta & Num, DnSta & Num=  ,4934, 2 ,5007, 2 , 0 , 0 , 0 ,,
       2       2
     -30      12
       2       2
     -30      12
Pier Skew, UpSta & Num, DnSta & Num=  ,4961, 2 ,5034, 2 , 0 , 0 , 0 ,,
       2       2
     -30      12
       2       2
     -30      12
Pier Skew, UpSta & Num, DnSta & Num=  ,4988, 2 ,5061, 2 , 0 , 0 , 0 ,,
       2       2
     -30      12
       2       2
     -30      12
Pier Skew, UpSta & Num, DnSta & Num=  ,5015, 2 ,5088, 2 , 0 , 0 , 0 ,,
       2       2
     -30      12
       2       2
     -30      12
Pier Skew, UpSta & Num, DnSta & Num=  ,5042, 2 ,5115, 2 , 0 , 0 , 0 ,,
       2       2
     -30      12
       2       2
     -30      12
Pier Skew, UpSta & Num, DnSta & Num=  ,5067, 2 ,5140, 2 , 0 , 0 , 0 ,,
       2       2
     -30      12
       2       2
     -30      12
BR Coef=-1 , 1 , 1 ,1.05, 0 ,,,.8,-1,1.2,0,
WSPro=,,,, 1 ,,,, 0 ,,,, 0 ,,,,-1 ,-1 ,-1 , 0 , 0 , 0 , 0 , 0
BR Coef=-1 , 0 , 0 ,1.05, 0 ,,,.8,-1,1.2,0,
WSPro=,,,, 1 ,,,, 0 ,,,, 0 ,,,,-1 ,-1 ,-1 , 0 , 0 , 0 , 0 , 0
BC Mult= 3 ,0,4100,0,4200
BC Mult= 3 ,4100,7757.81,4200,7750.87
BC Design=,, 0 ,, 0 ,,,,,,
BC HTab HWMax=16.74

Type RM Length L Ch R = 1 ,46214.15,1192.1,2138.4,511.35
XS GIS Cut Line= 6
     3205529.841    13760473.177     3207667.273    13758018.018
      3207685.81    13757888.973     3208576.713     13756936.65
     3208562.334    13756880.857     3210570.137    13754689.112
#Sta/Elev= 30
       0   15.98 2683.06   12.68 2809.17    7.53 2836.24   12.29 2942.38    4.76
 3234.08    3.37  3240.1   -1.92 3322.19    -.38  3352.5     5.3 3407.45    1.14
 3411.72    -.51 3504.28   -9.25 3636.28    1.75 3672.23   10.63  3747.2   -1.88
  4557.7   -1.25 4705.65   -1.49 4731.48    5.14 4964.39    4.51 4997.62   -1.25
 5124.47   -1.26 5163.16    8.52 5221.17    -.55 5377.74    -.32 6129.36   13.23
 6145.66    6.17 6228.73   15.94 7138.64    16.3 7155.31    9.81 7750.87   15.18
#Mann= 12 ,-1 , 0
       0     .07       0 3234.08    .035       0 3322.19     .07       0
 3411.72    .035       0 3636.28     .07       0  3747.2    .035       0
  4557.7    .035       0 4731.48     .07       0 4997.62    .035       0
 5124.47     .07       0 5221.17    .035       0 5377.74     .07       0
#XS Ineff= 3 ,-1
       0 3379.69   12.76  3668.8 4759.19      18 5161.61 7750.87   12.76
Permanent Ineff=
       F       F       F
#Block Obstruct= 3 ,-1
 1099.24 1709.92   12.21                         6974.05 7364.89   14.24
Bank Sta=3407.45,3636.28
XS Rating Curve= 0
Exp/Cntr=.5,.3

Type RM Length L Ch R = 1 ,44075.74,758.54,818.21,792.41
XS GIS Cut Line= 5
     3205665.588      13760776.4     3208696.067    13757630.906
     3208988.446    13756983.469     3209438.987    13756684.689
     3210994.738    13755267.937
#Sta/Elev= 30
       0   16.55 1545.63   12.78 1852.54    6.92 1876.12   -1.13 1891.45    4.02
 1962.21     7.7 2248.25     8.6 2303.49   13.89 2378.79   10.03  2833.4    12.6
 3271.76     8.9 3807.48    9.98 4462.11    4.68 4496.12    2.16 4570.24   -1.25
 5407.83   -2.11 5488.05   -4.19 5527.76   -9.89 5578.07  -11.28 5619.46   -8.65
  5649.1    -2.8 5657.85    2.32 5665.46     2.4 5775.42    2.71 5824.11    6.83
 5844.73    5.17 5893.09   10.31  6258.5    14.4 7602.47   12.27    7723   14.24
#Mann= 3 ,-1 , 0
       0     .07       0 4570.24    .035       0  5649.1     .07       0
#XS Ineff= 2 ,-1
       0 3466.24   12.59 5947.79    7723   12.59
Permanent Ineff=
       F       F
#Block Obstruct= 1 ,-1
 1575.57 2015.27     6.9
Bank Sta=4496.12,5665.46
XS Rating Curve= 0
Exp/Cntr=.5,.3

Type RM Length L Ch R = 1 ,43257.53,619.02,606.21,696.26
XS GIS Cut Line= 6
     3206306.296    13761179.809     3208526.475    13758792.237
     3209080.195     13758284.66     3209505.766    13757534.486
      3210069.69    13757163.484      3211766.32    13755235.787
#Sta/Elev= 30
       0   16.79 1578.86   15.87 1655.45   11.02 1799.14   18.26 1943.39   12.51
 1995.54   18.58  2048.8   -1.16 2292.57   -1.16 2361.14   18.52 2644.75   10.95
 3831.09   11.27    3875   16.72 3900.99   12.48 3916.44   18.52 3975.53   -1.16
 4347.25     2.6 4380.36   -1.25 4937.12  -11.52 5062.89    -.29 5068.05     .97
 5514.83    1.74 6068.12    9.31 6435.68      12 6482.99     3.5  6508.6    10.8
 6877.91   11.19 7025.17      22 7162.82     9.4  7170.2   14.12 8116.97   14.45
#Mann= 5 ,-1 , 0
       0     .07       0 4380.36    .035       0 5062.89     .07       0
 5514.83     .12       0 6068.12     .07       0
#XS Ineff= 2 ,-1
       0 3300.77    12.5 5896.74 8116.97    12.5
Permanent Ineff=
       F       F
#Block Obstruct= 2 ,-1
 1847.33 2412.21   12.43 6335.88 6549.62   10.34
Bank Sta=4347.25,5068.05
XS Rating Curve= 0
Exp/Cntr=.5,.3

Type RM Length L Ch R = 1 ,42651.33,402.98,600.47,660.43
XS GIS Cut Line= 6
     3206492.488    13761330.722     3209680.059    13758469.233
     3209810.467    13758111.268     3209919.354    13757977.635
     3210661.407    13757478.197     3212784.182       13755262.
#Sta/Elev= 30
       0   17.25 1314.78   18.58 1337.25    5.19 1362.62   -1.16 1698.33    -1.1
  1723.7     1.8 1771.27   18.52 2730.71    8.36 2870.44   12.64  3052.8     5.3
 3094.41    10.8 3254.65    6.29 3715.41   13.06 4367.89    2.02 4636.94    1.03
  4642.8    1.69 4653.22   18.52  4669.9    6.27 4679.75   -1.16 4906.73   -4.84
 5075.09  -15.62 5084.12   -8.77 5145.19   -3.16 5505.65   -3.37 5522.42    4.32
 5995.19     -.1 6873.68   17.02 7451.05   12.98 7510.35    8.36  8800.2   15.67
#Mann= 8 ,-1 , 0
       0     .07       0 2366.99     .12       0 2816.77     .07       0
 3048.39     .12       0 4367.89     .07       0 4659.35    .035       0
 5492.91     .12       0 5730.25     .07       0
#Block Obstruct= 1 ,-1
 1175.57 1816.79   16.86
Bank Sta=4669.9,5522.42
XS Rating Curve= 0
Exp/Cntr=.3,.1

Type RM Length L Ch R = 1 ,42050.86,432.22,630.32,910.72
XS GIS Cut Line= 4
     3206599.126    13761514.917      3210265.08     13758464.18
     3211405.727    13757710.193     3213307.682    13755921.222
#Sta/Elev= 30
       0   17.35 1823.78   16.15 2061.35    13.9 2066.73    8.13 2284.05   14.34
 2742.66   12.09 2984.42    8.68 3002.85    2.14  3067.9    1.52 3213.68    8.68
 3263.15    1.69 3377.36   13.86 3397.78    8.23 3876.61   11.03 4413.93    1.04
 4763.47    1.41 4965.58  -12.36 5105.96   -1.99 6311.92    1.23 6333.88    8.07
 6616.58    4.45  7160.8   10.46 7177.61    4.25  7238.8   10.25 7580.15   12.19
 7598.38    6.73 8202.16     9.9 8246.01   14.66 8278.74    9.54 8747.73    13.1
#Mann= 7 ,-1 , 0
       0     .07       0 2354.01     .12       0 3002.22     .07       0
 3416.16     .12       0 4413.93     .07       0 4565.79    .035       0
 6311.92     .07       0
#Block Obstruct= 3 ,-1
    2000 2244.27   12.58 2778.63 3435.11    7.54 2814.75 3592.92    9.27
Bank Sta=4763.47,6311.92
XS Rating Curve= 0
Exp/Cntr=.3,.1