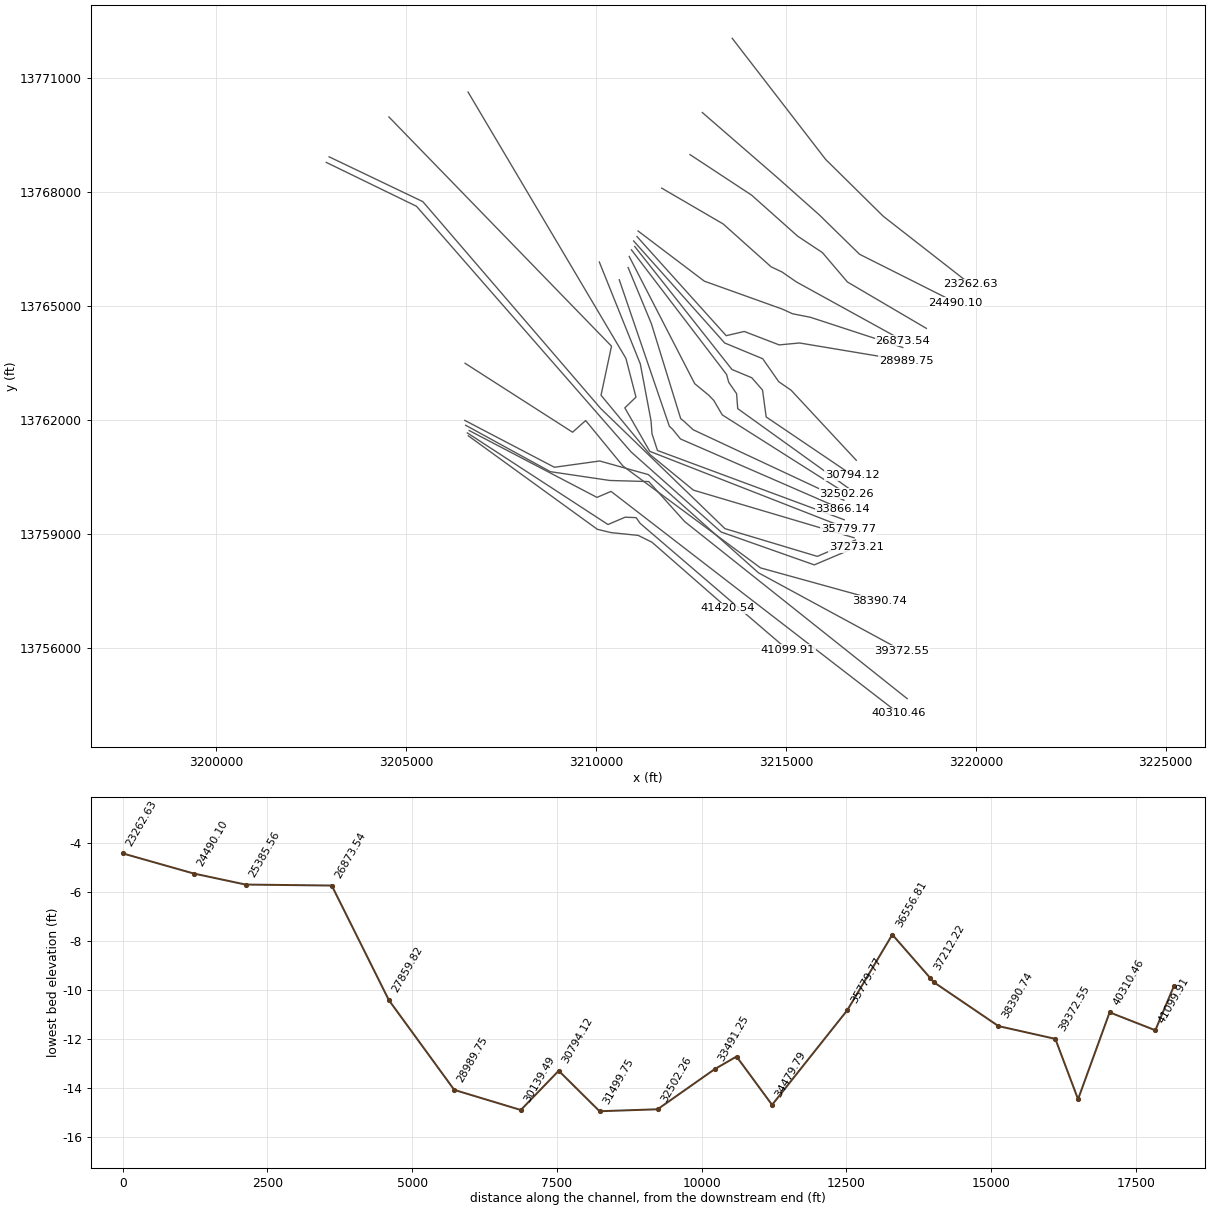
HEC-RAS study A100-00-00.prj: A100-00-00

--- A100-00-00.g01 (geometry) --- (continued)

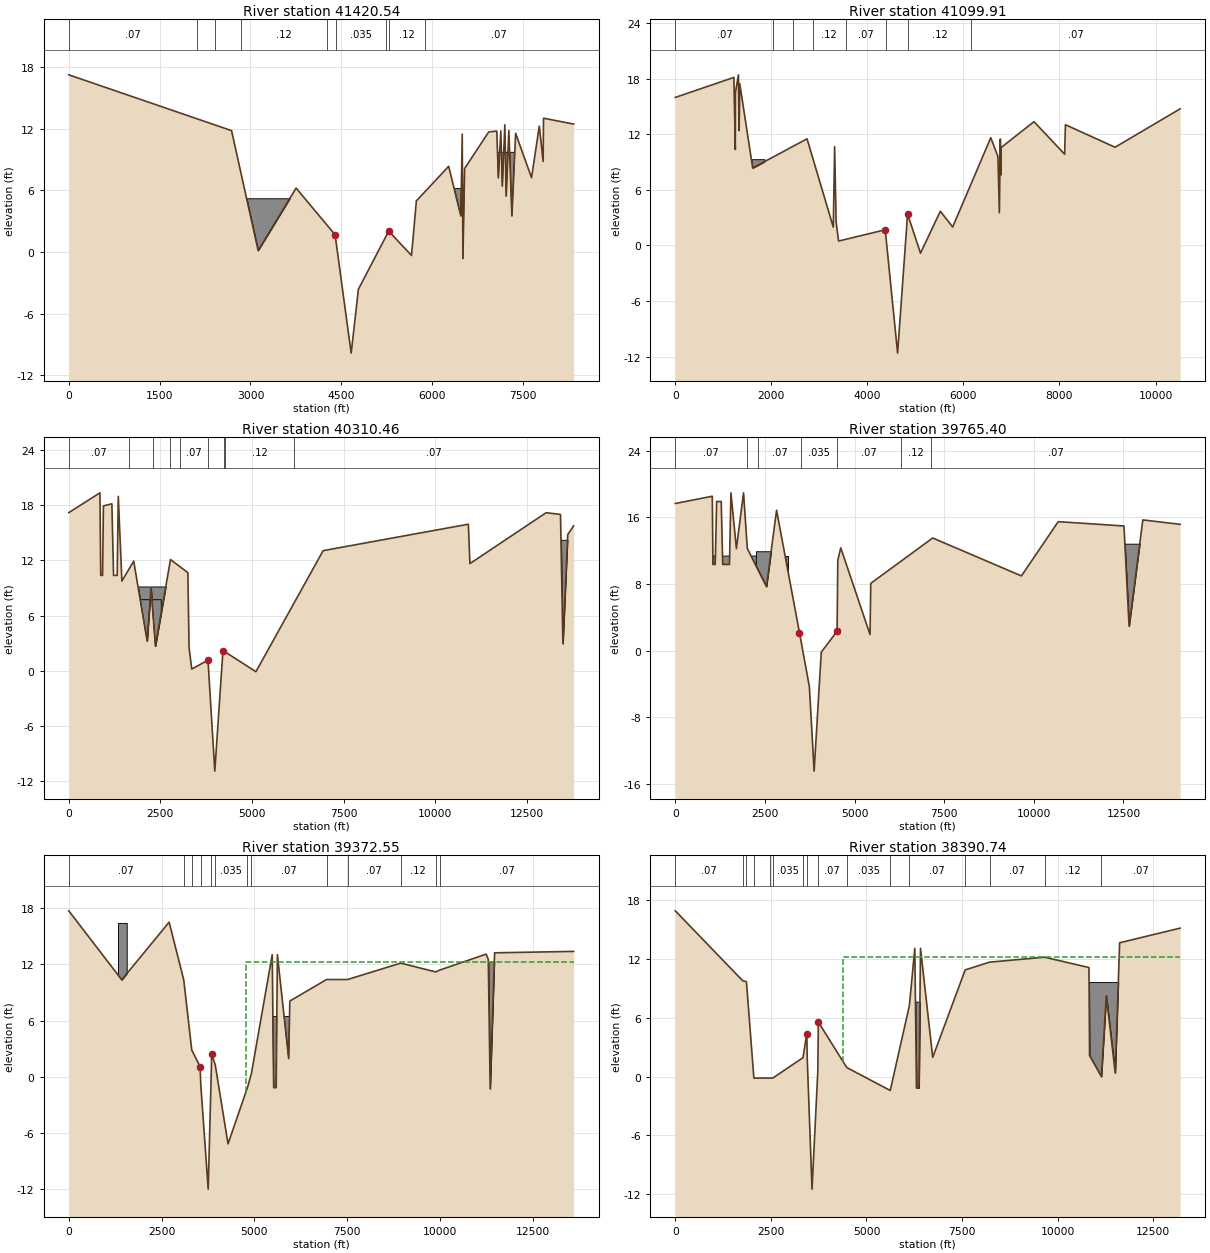
Type RM Length L Ch R = 1 ,41420.54,396.08,320.63,213.81
XS GIS Cut Line= 6
     3206634.599    13761583.908     3210033.085    13759121.501
     3210390.745    13759034.503      3211108.06    13758960.973
     3211472.716      13758780.4     3213463.813     13757038.79
#Sta/Elev= 30
       0   17.25 2688.36   11.82 3127.27     .16 3754.63    6.23 4398.19    1.69
 4663.95   -9.83 4783.11   -3.62 5283.91    2.04 5660.52    -.33 5740.51    4.98
 6274.57    8.35 6475.75    3.52 6498.11   11.48 6509.53    -.63 6537.65    8.13
 6936.22    11.7 7069.08   11.77 7094.78    7.23  7135.5   11.79 7160.62    6.42
 7201.93   12.39  7224.5    5.45 7268.36   11.83 7318.69    3.52 7380.05   11.56
 7642.79    7.24 7770.96   12.26 7834.52    8.82 7840.62   13.03 8338.19   12.46
#Mann= 9 ,-1 , 0
       0     .07       0 2121.49     .12       0 2419.66     .07       0
 2843.99     .12       0 4261.48     .07       0 4417.66    .035       0
 5243.72     .07       0 5283.91     .12       0  5881.1     .07       0
#Block Obstruct= 3 ,-1
  2885.5 3755.73    5.24 6351.15 6610.69    6.18 6916.03 7450.38    9.71
Bank Sta=4398.19,5283.91
XS Rating Curve= 0
Exp/Cntr=.3,.1

Type RM Length L Ch R = 1 ,41099.91,575.19,789.45,271.9
XS GIS Cut Line= 6
     3206608.821    13761660.333     3210313.413    13759247.166
     3210766.764    13759440.397     3211054.839     13759428.11
     3211160.378    13759277.878     3215052.682    13755940.611
#Sta/Elev= 30
       0   15.98 1219.36   18.14 1249.28   10.36 1250.75   16.47 1314.17   18.42
 1328.82   12.39 1343.07   17.44 1611.25    8.36  2743.1   11.51 3289.86    1.97
  3317.4   10.66 3348.66    2.54 3399.94     .47 4371.07    1.69 4628.96  -11.63
 4836.82    3.39 5105.98    -.84 5518.44    3.69 5776.26    1.99 6569.12   11.63
  6718.3    9.61 6747.95    3.52  6768.5   11.48 6778.08     7.6 6784.54   10.57
 7469.54   13.36 8106.99    9.85 8123.88   13.03 9157.84    10.610513.11   14.75
#Mann= 8 ,-1 , 0
       0     .07       0 2043.54     .12       0 2451.97     .07       0
 2865.03     .12       0  3544.5     .07       0 4382.39    .035       0
 4849.91     .12       0 6161.42     .07       0
#Block Obstruct= 1 ,-1
 1160.41 1856.66    9.31
Bank Sta=4371.07,4836.82
XS Rating Curve= 0
Exp/Cntr=.3,.1

Type RM Length L Ch R = 1 ,40310.46,490.96,545.07,1111.67
XS GIS Cut Line= 4
      3206657.67    13761722.338     3210023.852     13759961.78
     3210394.521    13760119.314      3217970.71    13754273.167
#Sta/Elev= 30
       0   17.18  850.48   19.33  870.52   10.36  921.78   10.36  944.63   17.91
 1175.22   18.14 1220.97   10.36 1320.08   10.36 1349.97   18.95 1448.86    9.75
  1771.2   11.91  2137.7    3.24 2242.18    9.01 2363.77    2.68 2774.04   12.08
 3248.61   10.66 3280.56    2.54 3353.93     .19 3796.78    1.15 3983.24   -10.9
 4205.36     2.2 5104.28     -.1 6938.24   13.0510899.88   15.9210941.85   11.64
13019.91   17.1713412.48   16.9813478.44    2.9513610.38   14.7913771.07   15.75
#Mann= 9 ,-1 , 0
       0     .07       0 1648.81     .12       0 2310.37     .07       0
 2774.04     .12       0 3039.83     .07       0 3803.02    .035       0
 4239.29     .07       0 4269.72     .12       0 6144.37     .07       0
#Block Obstruct= 3 ,-1
 1162.68 2739.48    9.16  1731.3 2522.14    7.7213123.6613636.64   14.23
Bank Sta=3796.78,4205.36
XS Rating Curve= 0
Exp/Cntr=.3,.1

Type RM Length L Ch R = 1 ,39765.40,350.82,392.85,451.06
XS GIS Cut Line= 6
     3206565.384    13761860.768     3208795.773    13760639.141
     3210361.745    13760407.145     3211386.394    13760378.146
     3212333.711    13759324.498     3218193.682    13754660.945
#Sta/Elev= 30
       0   17.67  1031.2   18.54 1050.25   10.36 1113.65   10.36 1153.37   17.91
 1281.17   17.91 1322.12   10.36 1510.72   10.36 1551.48   18.95 1703.86   12.25
  1903.3   18.95 2009.06   12.27 2543.03     7.7 2824.43   16.86 3463.75    2.18
 3739.54   -4.31 3872.14  -14.44 4071.88    -.17 4512.19    2.34 4532.99   10.85
 4614.79   12.35 5432.25    1.95  5452.3    8.09 7181.07   13.53 9655.08    8.98
10681.48   15.4912515.16   14.9712658.41    2.9513041.89    15.7 14083.4   15.17
#Mann= 7 ,-1 , 0
       0     .07       0 2007.87     .12       0 2316.16     .07       0
  3494.8    .035       0 4500.07     .07       0 6293.31     .12       0
 7139.72     .07       0
#Block Obstruct= 3 ,-1
  491.47 3149.03   11.36 2247.33 2687.02   11.9412213.7413019.85   12.85
Bank Sta=3463.75,4512.19
XS Rating Curve= 0
Exp/Cntr=.5,.3

Type RM Length L Ch R = 1 ,39372.55,1253.35,981.81,166.76
XS GIS Cut Line= 6
      3206540.96    13761989.945     3208902.105    13760755.139
     3210095.597     13760920.46     3211376.727    13760561.809
     3214278.053    13757974.322     3218057.123    13755925.668
#Sta/Elev= 30
       0   17.72 1426.83   10.36 2702.98   16.51 3096.52   10.36 3312.81    2.87
 3537.27     1.1 3556.62    -.88 3755.76  -11.98 3841.38     .92 3848.34    2.44
 3945.45    1.29 4290.04   -7.15 4813.29   -1.14 4917.97     .33 5480.65   13.04
  5519.6   -1.15 5587.29   -1.15 5619.32   13.04 5924.01    1.95 5954.78    8.09
 6944.55   10.39 7510.85   10.39 8942.05   12.14 9885.51    11.2 9988.29   11.39
11243.76    13.111300.64   12.5511351.93   -1.2711471.26   13.2413600.31   13.39
#Mann= 13 ,-1 , 0
       0     .07       0 3096.52     .12       0 3312.81     .07       0
 3556.62    .035       0 3841.38     .07       0 3945.45    .035       0
 4813.29    .035       0 4917.97     .07       0 6944.55     .12       0
 7510.85     .07       0 8942.05     .12       0 9885.51     .12       0
 9988.29     .07       0
#XS Ineff= 1 ,-1
 4768.6813600.31   12.29
Permanent Ineff=
       F
#Block Obstruct= 3 ,-1
 1325.19 1560.31   16.43 5407.63 5984.73    6.4411135.8811541.98    12.3
Bank Sta=3537.27,3848.34
XS Rating Curve= 0
Exp/Cntr=.5,.3

Type RM Length L Ch R = 1 ,38390.74,1269.91,1117.53,1325.44
XS GIS Cut Line= 6
     3206550.654    13763492.583     3209380.534    13761678.502
     3209725.738    13761985.593     3210709.706    13760786.124
      3214331.63    13758104.472     3217457.519    13757240.599
#Sta/Elev= 30
       0   16.86 1761.88    9.75  1861.3    9.64 2054.77    -.16 2488.89    -.16
 2549.58    -.16  3340.7    1.92 3439.13    4.36 3450.94    1.82 3576.68  -11.46
 3727.05     .48 3742.16    5.54 4486.42     .91 5622.34   -1.42 6123.21    7.22
 6264.63   13.04 6308.55   -1.15 6375.21   -1.15 6413.87   13.04 6733.63    1.95
 7583.03   10.85 8223.59   11.64 9660.74   12.1410820.53   11.0910836.17    2.13
11146.14    -.0111274.01    8.2211508.01     .3711623.11   13.6113206.52    15.1
#Mann= 16 ,-1 , 0
       0     .07       0 1761.88     .15       0  1861.3     .07       0
 2054.77    .035       0 2488.89     .07       0 2549.58    .035       0
  3340.7     .07       0 3450.94    .035       0 3727.05     .07       0
 4486.42    .035       0 5622.34     .12       0 6123.21     .07       0
 7583.03     .12       0 8223.59     .07       0 9660.74     .12       0
11146.14     .07       0
#XS Ineff= 1 ,-1
 4390.2413206.52   12.19
Permanent Ineff=
       F
#Block Obstruct= 3 ,-1
  461.89 1067.12     9.1 6198.47 6454.96    7.6210387.7911648.85    9.61
Bank Sta=3439.13,3742.16
XS Rating Curve= 0
Exp/Cntr=.5,.3

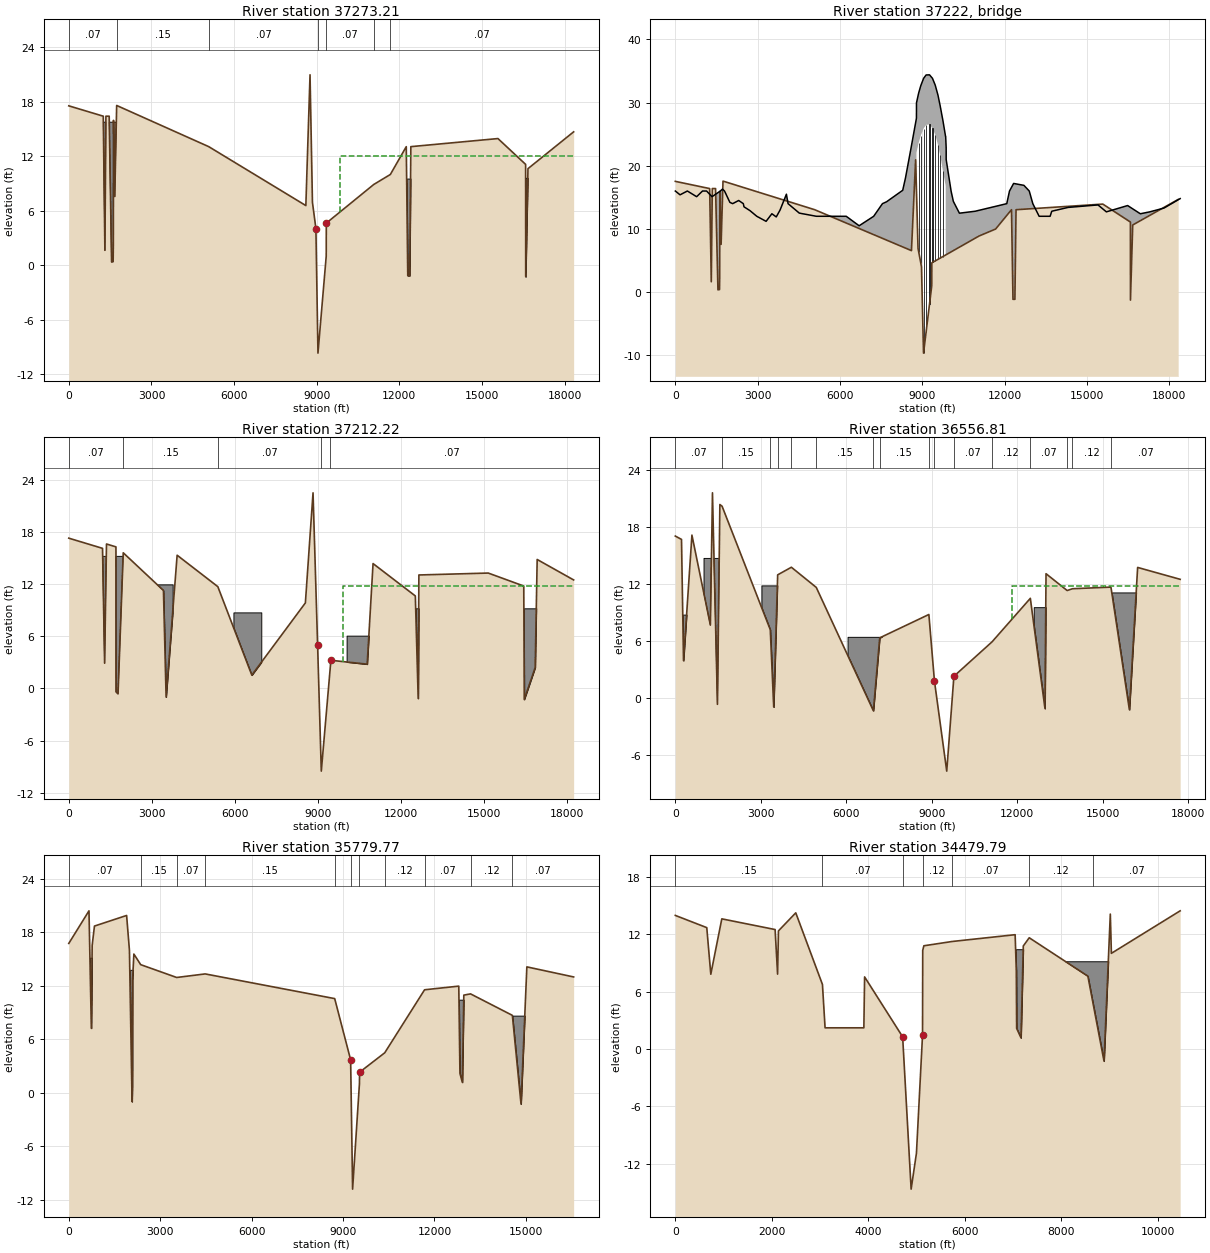
Type RM Length L Ch R = 1 ,37273.21,60.8,60.99,183
XS GIS Cut Line= 6
     3202894.155    13768784.612     3205269.883    13767629.243
     3210924.127    13761156.561     3213292.475    13759050.629
     3215747.634    13758184.102     3216855.348    13758653.807
#Sta/Elev= 30
       0   17.53 1251.99   16.39    1311    1.64 1347.96   16.39  1466.8   16.39
 1554.08     .36 1610.13     .39 1617.68    2.32 1623.38   15.93 1669.03    7.56
 1738.19   17.57 5081.06   13.04 8606.19    6.56 8757.99   20.94 8845.66    6.92
 8971.36    4.03 9046.05   -9.67 9345.92       1 9349.18    4.6311071.89    8.88
11673.81    9.9812251.77   13.0412305.91   -1.1512376.27   -1.1512417.83   13.04
15579.99   13.9316584.77   11.0916587.76   -1.27 16670.1   10.6218327.88   14.67
#Mann= 7 ,-1 , 0
       0     .07       0 1738.19     .15       0 5081.06     .07       0
 9046.05    .035       0 9345.92     .07       011071.89     .12       0
11673.81     .07       0
#XS Ineff= 2 ,-1
 9853.4418327.88      12       0    8775    10.4
Permanent Ineff=
       F       F
#Block Obstruct= 3 ,-1
 1129.77 1801.53   15.7312183.2112519.08    9.5316366.4117007.63    9.61
Bank Sta=8971.36,9349.18
XS Rating Curve= 0
Exp/Cntr=.5,.3

Type RM Length L Ch R = 3 ,37222   ,,,
BEGIN DESCRIPTION:
FM270
END DESCRIPTION:
Bridge Culvert--1,0,-1,-1, 0
Deck Dist Width WeirC Skew NumUp NumDn MinLoCord MaxHiCord MaxSubmerge Is_Ogee
5,50,2.6,0, 71, 71, , , .95, 0, 0,0,,
       0     173     439     777     991    1139    1339    1639    1719    1793
    1989    2089    2309    2479    2503    2719    2969    3308    3519    3679
    3819    4049    4109    4519    5141    6229    6699    7229    7549    7699
    8249    8287    8388    8589    8788    8789    8868    8948    9048    9140
    9264    9373    9473    9573    9653    9753    9853    9854    9871    9872
   10053   10133   10353   10929   12079   12179   12329   12704   12899   13029
   13259   13659   13719   14309   15404   15709   16484   16947   17290   17808
   18399
      16    15.4      16    15.1      16      16    15.1      16    16.3      16
    14.2      14    14.5      14    13.5    12.9      12    11.2    12.4    11.9
      13    15.5      14    12.5      12      12    10.5      12      14    14.3
      16   16.11   18.07   22.77   27.54   29.96   31.51   32.71   33.84   34.38
    34.4   33.84   32.76   31.17   29.48   27.15   24.54   24.54   22.85   20.97
   15.93   14.36   12.49    12.8      14      16    17.2    16.9      16      14
      12      12    12.8    13.4    13.8    12.7    13.7    12.4    12.7    13.3
    14.8
                                                                                
                                                                                
                                                                                
                                            22.1   23.64   24.79   25.89   26.46
   26.55   25.92    24.9   23.31   21.67   19.24   16.83
                                                                                
                                                                                
        
       0     245     511     849    1063    1211    1411    1711    1791    1865
    2061    2161    2381    2551    2575    2791    3041    3380    3591    3751
    3891    4121    4181    4591    5213    6301    6771    7301    7621    7771
    8321    8359    8460    8661    8860    8861    8940    9020    9120    9212
    9336    9445    9545    9645    9725    9825    9925    9926    9943    9944
   10125   10205   10425   11001   12151   12251   12401   12776   12971   13101
   13331   13731   13791   14381   15476   15781   16556   17019   17362   17880
   18471
      16    15.4      16    15.1      16      16    15.1      16    16.3      16
    14.2      14    14.5      14    13.5    12.9      12    11.2    12.4    11.9
      13    15.5      14    12.5      12      12    10.5      12      14    14.3
      16   16.11   18.07   22.77   27.54   29.96   31.51   32.71   33.84   34.38
    34.4   33.84   32.76   31.17   29.48   27.15   24.54   24.54   22.85   20.97
   15.93   14.36   12.49    12.8      14      16    17.2    16.9      16      14
      12      12    12.8    13.4    13.8    12.7    13.7    12.4    12.7    13.3
    14.8
                                                                                
                                                                                
                                                                                
                                            22.1   23.64   24.79   25.89   26.46
   26.55   25.92    24.9   23.31   21.67   19.24   16.83
                                                                                
                                                                                
        
Pier Skew, UpSta & Num, DnSta & Num=  ,8868, 2 ,8940, 2 , 0 , 0 , 0 ,,
       3       3
     -30      30
       3       3
     -30      30
Pier Skew, UpSta & Num, DnSta & Num=  ,8948, 2 ,9020, 2 , 0 , 0 , 0 ,,
       3       3
     -30      30
       3       3
     -30      30
Pier Skew, UpSta & Num, DnSta & Num=  ,9048, 2 ,9120, 2 , 0 , 0 , 0 ,,
       3       3
     -30      30
       3       3
     -30      30
Pier Skew, UpSta & Num, DnSta & Num=  ,9140, 2 ,9212, 2 , 0 , 0 , 0 ,,
       3       3
     -30      30
       3       3
     -30      30
Pier Skew, UpSta & Num, DnSta & Num=  ,9264, 2 ,9336, 2 , 0 , 0 , 0 ,,
       3       3
     -30      30
       3       3
     -30      30
Pier Skew, UpSta & Num, DnSta & Num=  ,9373, 2 ,9445, 2 , 0 , 0 , 0 ,,
       3       3
     -30      30
       3       3
     -30      30
Pier Skew, UpSta & Num, DnSta & Num=  ,9473, 2 ,9545, 2 , 0 , 0 , 0 ,,
       3       3
     -30      30
       3       3
     -30      30
Pier Skew, UpSta & Num, DnSta & Num=  ,9573, 2 ,9645, 2 , 0 , 0 , 0 ,,
       3       3
     -30      30
       3       3
     -30      30
Pier Skew, UpSta & Num, DnSta & Num=  ,9653, 2 ,9725, 2 , 0 , 0 , 0 ,,
       3       3
     -30      25
       3       3
     -30      25
Pier Skew, UpSta & Num, DnSta & Num=  ,9753, 2 ,9825, 2 , 0 , 0 , 0 ,,
       3       3
     -30      25
       3       3
     -30      25
BR Coef=-1 , 1 , 1 ,1.05, 0 ,,,.8,-1,1.2,0,
WSPro=,,,, 1 ,,,, 0 ,,,, 0 ,,,,-1 ,-1 ,-1 , 0 , 0 , 0 , 0 , 0
BC Design=,, 0 ,, 0 ,,,,,,
BC HTab HWMax=20.94

Type RM Length L Ch R = 1 ,37212.22,1147.54,655.41,245.56
XS GIS Cut Line= 6
     3202969.054    13768931.359     3205435.967    13767752.001
     3210123.701    13762300.563     3213394.598    13759138.312
     3215827.066    13758407.955     3216832.276     13758838.38
#Sta/Elev= 30
       0   17.27 1220.39    16.1 1295.79    2.91 1363.38    16.6 1705.47   16.27
  1709.9    -.39 1780.38    -.62  1969.5   15.59 3423.01   11.26 3519.36    -.99
 3918.36   15.31 5389.48    11.7 6618.77    1.53 8555.61    9.83 8832.48   22.48
 8998.07    4.96 9131.22    -9.5 9462.71    2.66  9464.4    3.2410790.96    2.79
11002.83   14.3512531.31   10.6312635.15   -1.1512660.16   13.0415169.18   13.26
16452.67   11.7716470.75   -1.2716865.86    2.4116937.63   14.8218256.33   12.47
#Mann= 5 ,-1 , 0
       0     .07       0  1969.5     .15       0 5389.48     .07       0
 9131.22    .035       0 9462.71     .07       0
#XS Ineff= 2 ,-1
 9924.5118256.33    11.8       0    8775    10.4
Permanent Ineff=
       F       F
#Block Obstruct= 6 ,-1
 1038.17 1984.73   15.18 3145.04 3755.73   11.96  5954.2 6961.83    8.74
 10045.8 11022.9    6.0712366.41 12885.5    9.2116122.1417099.24    9.21
Bank Sta=8998.07,9464.4
XS Rating Curve= 0
Exp/Cntr=.5,.3

Type RM Length L Ch R = 1 ,36556.81,509.44,777.04,415.65
XS GIS Cut Line= 6
     3204544.017    13769981.334     3210406.377    13763943.977
     3210130.272    13762653.074      3211424.78    13761085.505
     3212564.659    13760152.401     3216793.726    13758898.264
#Sta/Elev= 30
       0      17  217.35   16.65  288.04    3.89  583.36    17.1 1230.47    7.64
 1303.92   21.55  1479.1     -.7 1564.24   20.32 1641.79   20.14  3333.1    7.15
 3454.35    -.99 3592.88   12.92 4073.62   13.72 4947.26    11.6 6952.37   -1.38
  7174.5    6.29 8899.82    8.75 9094.52    1.77 9526.75   -7.73 9778.37    2.25
 11116.5    5.8712461.17   10.4512975.03   -1.1513012.01   13.0413753.86   11.27
13939.39   11.4615290.79   11.6315938.03   -1.2716227.08    13.717720.17   12.45
#Mann= 16 ,-1 , 0
       0     .07       0 1641.79     .15       0  3333.1     .07       0
 3592.88     .15       0 4073.62     .07       0 4947.26     .15       0
 6952.37     .07       0  7174.5     .15       0 8899.82     .07       0
 9094.52    .031       0 9778.37     .07       0 11116.5     .12       0
12461.17     .07       013753.86     .12       013939.39     .12       0
15290.79     .07       0
#XS Ineff= 1 ,-1
11817.2317720.17    11.7
Permanent Ineff=
       F
#Block Obstruct= 7 ,-1
   45.51  750.85    8.74 1007.63 1557.25   14.65  3022.9 3633.59   11.81
  6045.8 7480.92     6.411328.2411877.86    5.2112580.1513282.44    9.52
15328.2416366.41   11.07
Bank Sta=9094.52,9778.37
XS Rating Curve= 0
Exp/Cntr=.5,.3

Type RM Length L Ch R = 1 ,35779.77,330.51,1299.97,402.11
XS GIS Cut Line= 6
      3206628.21    13770637.389     3210785.535    13763623.152
     3211050.586    13762602.507     3210757.299    13762319.333
     3211414.211    13761174.231     3216642.571    13759130.083
#Sta/Elev= 30
       0   16.76  662.92   20.42  740.37    7.24  767.49   16.54  842.46   18.71
 1897.71    19.9 1990.38   15.99 2076.91    -.99 2086.92     .89 2091.55   12.59
 2135.76   15.57 2359.81   14.38 3540.88   12.94 4476.09   13.34 8725.93   10.57
 9248.89     3.7 9313.51  -10.81 9538.26    1.03 9543.09    2.3110368.39    4.49
 11675.4   11.5612797.84   11.9712836.18    2.1712915.09    1.1712963.27   10.96
13183.72    11.114556.35    8.6914840.44   -1.2715031.75   14.1316567.05      13
#Mann= 11 ,-1 , 0
       0     .07       0 2359.81     .15       0 3540.88     .07       0
 4476.09     .15       0 8725.93     .07       0 9248.89    .031       0
 9538.26     .07       010368.39     .12       0 11675.4     .07       0
13183.72     .12       014556.35     .07       0
#XS Ineff= 1 ,-1
11798.0616567.05    11.5
Permanent Ineff=
       F
#Block Obstruct= 4 ,-1
  549.62  796.95   15.16 1758.78 2225.95    13.812751.1513080.92   10.45
   1440015169.47    8.66
Bank Sta=9248.89,9543.09
XS Rating Curve= 0
Exp/Cntr=.5,.3

Type RM Length L Ch R = 1 ,34479.79,242.12,613.66,1165.94
XS GIS Cut Line= 6
     3210085.552    13766160.591     3211164.693    13763477.322
     3211446.196    13761985.847     3211473.461    13761635.231
     3211616.933    13761196.752     3216535.932    13759372.445
#Sta/Elev= 30
       0   13.99  652.37   12.71  735.97    7.83  964.31   13.63  2069.6   12.51
 2120.98    7.84 2138.96   12.37 2497.96   14.26 3051.25    6.76 3105.78    2.22
 3909.97    2.22 3925.46    7.55 4714.19    1.28 4890.51  -14.67 5000.59   -10.9
 5126.94    1.47 5130.78   10.33  5154.5   10.81 5742.03   11.26 7047.25   11.97
  7071.4    8.15 7078.36    2.17  7168.8    1.17 7216.57   10.79 7339.37   11.65
 8555.52    7.63  8890.5   -1.27    9021   14.13 9043.12   10.0210469.56   14.47
#Mann= 7 ,-1 , 0
       0     .15       0 3051.25     .07       0    4729    .031       0
 5126.94     .12       0 5742.03     .07       0 7339.37     .12       0
 8651.73     .07       0
#Block Obstruct= 2 ,-1
 6888.55  7291.6   10.45 7951.15 9087.02    9.19
Bank Sta=4714.19,5126.94
XS Rating Curve= 0
Exp/Cntr=.3,.1

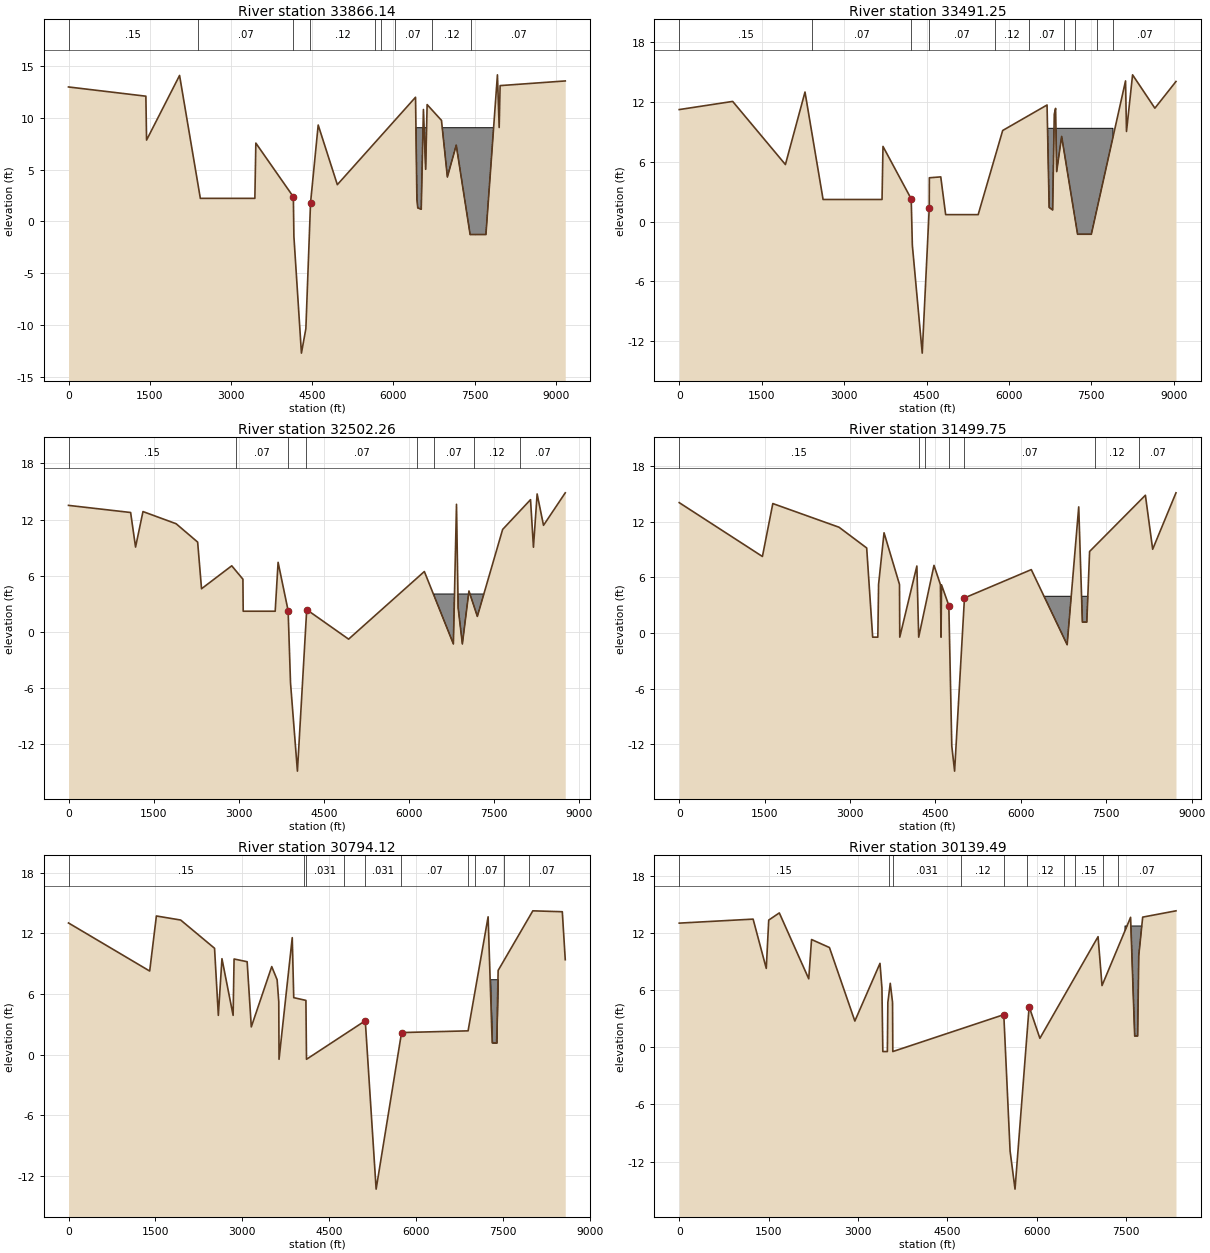
Type RM Length L Ch R = 1 ,33866.14,433.08,374.89,661.74
XS GIS Cut Line= 5
     3210610.539    13765693.936     3211930.447    13761833.893
     3212010.469     13761761.44     3212223.734    13761500.152
      3216487.46    13759643.889
#Sta/Elev= 30
       0   12.96 1428.99   12.07 1441.88    7.84 2051.39   14.07 2435.13    2.22
 3442.09    2.22  3460.2    7.55 4152.96    2.37 4163.02   -1.45  4302.2   -12.7
  4384.2  -10.34 4470.43    1.79 4611.83    9.29 4965.27    3.54 6409.83   11.97
 6434.67    2.17 6451.11     1.3 6514.93    1.17  6555.5   10.79 6596.52    5.02
  6623.8   11.26  6888.8    9.74 6997.87    4.28 7161.47    7.35 7417.95   -1.27
 7709.63   -1.27 7922.34   14.13 7954.45    9.05 7971.82   13.09 9174.97   13.54
#Mann= 9 ,-1 , 0
       0     .15       0 2387.97     .07       0 4152.96    .031       0
 4467.11     .12       0 5656.46     .07       0 5764.45     .12       0
 6026.76     .07       0 6708.37     .12       0  7442.1     .07       0
#Block Obstruct= 1 ,-1
 6290.08 7877.86    9.03
Bank Sta=4152.96,4470.43
XS Rating Curve= 0
Exp/Cntr=.3,.1

Type RM Length L Ch R = 1 ,33491.25,471.46,988.99,814.02
XS GIS Cut Line= 6
     3210843.867    13766014.761     3211456.779    13764536.338
     3212228.242    13762036.131     3212308.101    13761972.661
     3212557.475    13761742.873     3216526.238     13759886.25
#Sta/Elev= 30
       0   11.25  972.59   12.07 1932.36    5.73 2288.82   13.01 2617.92    2.22
 3690.62    2.22 3707.98    7.55 4221.48    2.28 4242.16   -2.37 4422.05  -13.21
 4549.64    1.36 4551.75     4.4 4759.15    4.49 4848.41      .7    5440      .7
 5886.16    9.15 6693.39   11.71 6731.85    1.42 6795.68    1.17 6825.02   10.79
 6848.83   11.37 6868.45    5.02 6958.68    8.56 7248.88   -1.27 7499.42   -1.27
 8121.61   14.13 8139.07    9.05 8249.88   14.74 8655.54   11.39 9039.64   14.07
#Mann= 10 ,-1 , 0
       0     .15       0 2418.74     .07       0 4225.04    .031       0
 4541.97     .07       0 5745.87     .12       0 6364.36     .07       0
 7000.75     .12       0 7205.95     .07       0 7599.99     .12       0
 7897.66     .07       0
#Block Obstruct= 1 ,-1
 6610.69 7893.13    9.37
Bank Sta=4221.48,4549.64
XS Rating Curve= 0
Exp/Cntr=.3,.1

Type RM Length L Ch R = 1 ,32502.26,726.92,1002.5,333.29
XS GIS Cut Line= 6
     3210873.033    13766306.421     3212597.928    13762956.474
     3212966.039    13762653.766     3213100.407    13762514.765
     3213322.809    13762134.829     3216594.099     13760060.75
#Sta/Elev= 30
       0   13.52 1094.31   12.76 1181.32    9.07 1312.04   12.86 1896.06   11.56
 2275.32     9.6 2343.59    4.62 2875.85    7.07 3072.68    5.64  3077.7    2.22
 3641.28    2.22 3692.55    7.44 3869.04    2.29 3911.42   -5.43 4033.03  -14.85
 4196.57    2.39 4934.95    -.76 6269.12    6.46 6780.52   -1.27 6835.33   13.63
 6864.74    2.58 6938.97   -1.27 7054.99    4.38 7202.68    1.67 7648.29   10.95
 8139.68   14.13 8191.16    9.05    8256   14.74 8368.49   11.39  8751.5   14.86
#Mann= 8 ,-1 , 0
       0     .15       0 2948.73     .07       0 3869.04    .031       0
 4191.18     .07       0 6143.64     .12       0 6438.56     .07       0
  7149.1     .12       0 7950.65     .07       0
#Block Obstruct= 1 ,-1
 6442.75 7465.65    4.06
Bank Sta=3869.04,4196.57
XS Rating Curve= 0
Exp/Cntr=.3,.1

Type RM Length L Ch R = 1 ,31499.75,199.41,705.63,281.65
XS GIS Cut Line= 6
     3210931.365    13766481.417     3213437.336    13763199.194
     3213493.144    13762993.564     3213700.283    13762693.527
     3213730.623    13762299.107     3216671.654    13760186.778
#Sta/Elev= 30
       0   14.09 1461.01    8.27 1643.69   13.99 2806.72   11.43 3292.01    9.19
 3397.12    -.45 3487.79    -.45 3500.93    5.25 3596.95   10.83 3868.37    5.24
 3872.96    -.45 4173.28    7.24 4205.47    -.45 4474.05    7.31 4586.77    5.24
    4598    -.45 4606.38     5.2 4734.69    2.97  4786.7  -12.22 4836.08  -14.93
 5009.25    3.79 6182.85    6.85 6812.57   -1.27 7015.86   13.63 7080.07    1.18
 7157.71    1.18 7206.76    8.81 8186.65   14.89  8314.4    9.05 8723.76   15.15
#Mann= 7 ,-1 , 0
       0     .15       0 4214.45    .031       0 4311.45     .07       0
  4744.5    .031       0 5003.25     .07       0 7307.19     .12       0
 8074.01     .07       0
#Block Obstruct= 1 ,-1
 6213.74 7206.11    3.97
Bank Sta=4734.69,5009.25
XS Rating Curve= 0
Exp/Cntr=.3,.1

Type RM Length L Ch R = 1 ,30794.12,475.55,654.63,930.28
XS GIS Cut Line= 6
     3211018.863    13766568.915     3213578.922    13763330.668
     3214100.561      13763112.8     3214383.854    13762789.294
     3214479.894    13762080.205      3216749.21    13760545.472
#Sta/Elev= 30
       0   13.02 1402.16    8.27 1517.73   13.71 1936.98   13.31 2522.08   10.52
 2587.68    3.89 2650.16    9.49 2842.89    3.89 2859.42    9.46 3085.24    9.19
 3156.86    2.75  3509.8    8.71 3602.71    7.41 3631.33    5.25 3635.91    -.45
 3864.01   11.57 3889.79    5.64 4100.07    5.37 4110.08    -.45 5125.24    3.36
 5312.62  -13.28 5751.95    2.19 6900.88    2.36 7246.65   13.63 7316.92    1.18
 7393.81    1.18 7419.98    8.33  8018.9   14.22 8527.92   14.13 8578.81    9.39
#Mann= 10 ,-1 , 0
       0     .15       0 4066.27     .07       0 4103.85    .031       0
 4750.09     .12       0 5125.24    .031       0 5744.37     .07       0
 6900.88     .12       0 7027.59     .07       0 7528.68     .12       0
  7951.1     .07       0
#Block Obstruct= 1 ,-1
 7206.11 7419.85    7.46
Bank Sta=5125.24,5751.95
XS Rating Curve= 0
Exp/Cntr=.3,.1

Type RM Length L Ch R = 1 ,30139.49,274.89,1149.74,1416.22
XS GIS Cut Line= 6
     3210989.697    13766714.745     3213386.769    13764028.489
      3214387.99    13763613.841     3214812.751    13763007.041
     3215136.378    13762784.547     3216852.058    13760939.882
#Sta/Elev= 30
       0   13.02 1239.87   13.44 1460.75    8.27 1502.19   13.34 1679.75   14.09
 2173.56    7.18 2220.73    11.3 2521.13   10.46 2947.38    2.75 3369.25     8.8
 3401.87    6.22 3416.87    -.45    3493    -.45 3501.18     4.7 3541.72    6.71
 3579.79    4.71 3584.33    -.45 5447.05    3.42 5552.64  -10.88 5635.42  -14.88
 5872.26    4.26  6052.7     .94 7028.96    11.6 7095.36    6.47 7574.98   13.63
 7643.64    1.18 7693.59    1.18 7711.99     9.6 7777.94   13.65 8336.59   14.31
#Mann= 10 ,-1 , 0
       0     .15       0 3525.96     .07       0  3589.4    .031       0
 4736.35     .12       0 5447.05    .031       0 5837.95     .12       0
 6461.44     .07       0 6647.43     .15       0 7114.87     .12       0
 7365.05     .07       0
#Block Obstruct= 1 ,-1
 7480.92 7816.79   12.72
Bank Sta=5447.05,5872.26
XS Rating Curve= 0
Exp/Cntr=.3,.1

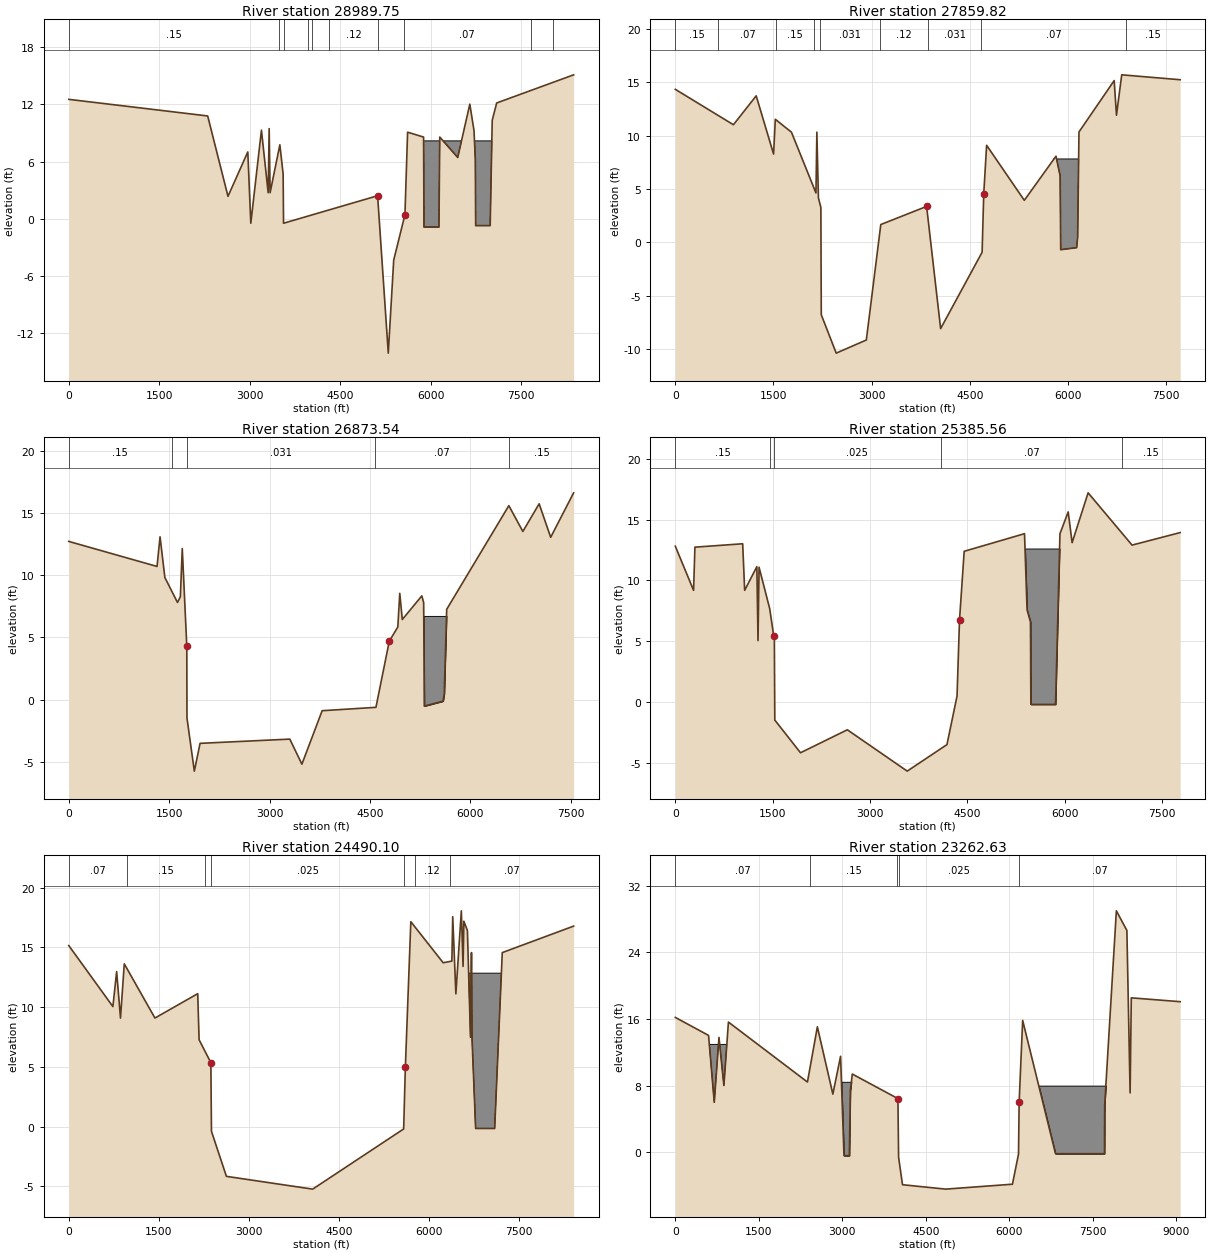
Type RM Length L Ch R = 1 ,28989.75,767.9,1129.93,721.55
XS GIS Cut Line= 6
     3211077.195    13766831.409     3213427.222    13764220.642
     3213902.549    13764331.889     3214822.864    13763977.922
     3215358.871    13764028.489     3218164.599    13763560.445
#Sta/Elev= 30
       0   12.53 2303.48   10.79  2640.1    2.37 2968.73    7.02 3018.58    -.45
 3194.87     9.3 3306.49    2.75 3322.93    9.46 3338.68    2.75 3500.24    7.77
 3554.76     4.7 3561.28    -.45 5121.31    2.43 5298.06  -14.06 5388.41   -4.31
  5574.6     .44 5618.52    9.09 5883.59    8.58 5890.36    -.85 6138.48    -.85
 6151.76    8.58 6449.92    6.44 6650.41   12.03 6719.77    9.26 6741.86    6.22
 6747.37     -.7 6988.03     -.7 7022.04   10.34 7095.71   12.15 8372.12    15.1
#Mann= 10 ,-1 , 0
       0     .15       0 3492.26     .07       0  3566.1    .031       0
 3960.18     .12       0 4033.43    .031       0 4309.63     .12       0
 5130.35    .031       0 5553.06     .07       0 7662.75     .15       0
 8028.61     .07       0
#Block Obstruct= 1 ,-1
 5770.99 7160.31    8.18
Bank Sta=5121.31,5574.6
XS Rating Curve= 0
Exp/Cntr=.3,.1

Type RM Length L Ch R = 1 ,27859.82,1593.92,986.28,670.34
XS GIS Cut Line= 6
     3211106.361    13766977.239     3212850.762    13765656.737
     3214903.385    13764921.623     3215176.831    13764797.103
     3215642.045    13764706.083     3218077.349    13763909.445
#Sta/Elev= 30
       0   14.34  887.91   11.02 1235.85   13.73 1501.46    8.27 1528.18   11.53
 1774.44   10.32 2148.93    4.62 2162.73   10.32 2186.52    4.16 2223.86    3.26
 2230.26    -6.8  2458.4   -10.4 2918.49   -9.17 3139.69    1.66 3839.67    3.36
  4053.9    -8.1 4687.48    -.94 4712.65    4.56  4756.6    9.09 5332.35    3.93
 5816.45    8.07 5880.06    6.22 5888.35     -.7 6131.87    -.51 6147.43     .48
 6167.57   10.34 6705.41   15.16 6740.56   11.91 6820.67    15.7 7713.71   15.24
#Mann= 9 ,-1 , 0
       0     .15       0  658.67     .07       0 1543.59     .15       0
 2120.96     .07       0 2217.85    .031       0 3131.38     .12       0
 3857.71    .031       0 4675.21     .07       0 6880.02     .15       0
#Block Obstruct= 1 ,-1
  5777.1 6229.01    7.81
Bank Sta=3839.67,4712.65
XS Rating Curve= 0
Exp/Cntr=.3,.1

Type RM Length L Ch R = 1 ,26873.54,1088.99,1487.99,850.99
XS GIS Cut Line= 6
     3211727.488    13768107.139     3213345.596    13767164.165
     3214608.896    13766035.235     3214897.937    13765898.097
     3215277.095    13765635.604     3218077.349    13764093.639
#Sta/Elev= 30
       0   12.71  1318.9    10.7 1363.99   13.08 1436.06    9.81 1624.57    7.81
 1667.48    8.26 1695.95   12.14 1763.69    4.29 1766.23   -1.46 1876.34   -5.73
 1962.14    -3.5 3302.88   -3.16    3484   -5.17 3786.41    -.88 4590.34    -.61
 4789.67     4.7 4917.31    5.84 4946.24    8.54 4984.18    6.44 5275.93    8.34
 5303.68     7.8 5312.77    -.51 5593.61    -.11 5611.48     .48 5647.91    7.26
 6576.52   15.58 6785.81   13.51 7029.35   15.73 7201.75   13.04 7544.86   16.61
#Mann= 5 ,-1 , 0
       0     .15       0 1536.81     .07       0 1763.69    .031       0
 4572.79     .07       0 6582.59     .15       0
#Block Obstruct= 1 ,-1
 5190.84 5728.24    6.73
Bank Sta=1763.69,4789.67
XS Rating Curve= 0
Exp/Cntr=.3,.1

Type RM Length L Ch R = 1 ,25385.56,863.44,895.45,713.71
XS GIS Cut Line= 6
      3212473.96    13768989.333     3214096.226    13767922.322
     3215311.343    13766839.949     3215961.143     13766409.02
      3216618.73    13765635.604     3218697.793    13764413.556
#Sta/Elev= 30
       0   12.81  281.31    9.18  302.07   12.73 1037.65   13.01 1068.19    9.18
 1256.09   11.13 1273.73    5.05 1289.97   11.08 1454.43    7.66 1516.56    5.39
  1525.3    5.41 1532.28   -1.49 1928.31   -4.18 2649.43   -2.29 3572.04   -5.69
 4183.84   -3.51 4339.24     .48 4377.39    6.73 4449.27   12.39 5378.51   13.84
 5417.71    7.58 5470.38    6.58 5476.26     -.2 5856.53     -.2 5924.55   13.84
 6051.45   15.63 6111.72    13.1 6358.14    17.2 7035.12    12.9 7776.03   13.93
#Mann= 5 ,-1 , 0
       0     .15       0 1454.43     .07       0 1516.56    .025       0
 4091.74     .07       0 6886.06     .15       0
#Block Obstruct= 1 ,-1
 5325.19 5948.09   12.62
Bank Sta=1516.56,4377.39
XS Rating Curve= 0
Exp/Cntr=.3,.1

Type RM Length L Ch R = 1 ,24490.10,1526.19,1227.47,1186.86
XS GIS Cut Line= 5
     3212797.987    13770097.998     3214782.411    13768377.227
     3215874.652    13767406.346     3216939.555    13766364.753
     3219473.349    13765092.167
#Sta/Elev= 30
       0   15.16  734.99   10.05  797.41   12.98  861.84    9.09  924.63   13.63
 1435.75    9.09 2148.67   11.13 2171.57    7.27 2367.68    5.35 2377.69     -.4
 2626.59   -4.17 4064.33   -5.24 5580.36     -.2 5608.97    5.01 5699.75   17.16
 6239.31   13.72 6383.75   13.86 6397.87   17.58 6450.41   11.12 6541.57   18.07
 6570.44   13.42 6583.33    17.2 6642.83   16.42 6694.07    7.49 6710.48   14.57
 6720.11    7.35 6779.68    -.16 7096.95    -.16 7223.57   14.57 8412.99   16.79
#Mann= 7 ,-1 , 0
       0     .07       0  965.98     .15       0 2270.75     .07       0
 2377.01    .025       0 5593.04     .07       0 5765.68     .12       0
 6346.68     .07       0
#Block Obstruct= 1 ,-1
 6519.08 7389.31   12.85
Bank Sta=2367.68,5608.97
XS Rating Curve= 0
Exp/Cntr=.3,.1

Type RM Length L Ch R = 1 ,23262.63,3004.04,2403.17,1663.48
XS GIS Cut Line= 4
     3213585.468    13772052.118     3216046.579    13768862.668
      3217563.58    13767365.893     3219856.153    13765577.272
#Sta/Elev= 30
       0    16.2  597.23   14.04  699.63    6.01  784.19    13.8  872.49    8.03
  953.96   15.64 2373.34    8.44 2551.43   15.07 2829.62    6.99 2968.24   11.53
 3029.47     -.4 3125.95     -.4 3143.31    7.38 3178.96     9.4 3998.36    6.45
 4010.36     -.6 4080.39   -3.89 4856.05   -4.42 6054.96   -3.83 6164.26     -.2
 6175.31    6.02 6238.63   15.84  6828.1    -.16 7708.32    -.16 7711.44    5.64
 7921.56      29  8110.4   26.64 8168.35    7.14 8189.67   18.55 9067.48   18.09
#Mann= 5 ,-1 , 0
       0     .07       0 2414.58     .15       0 3987.06     .07       0
 4011.45    .025       0 6175.31     .07       0
#Block Obstruct= 3 ,-1
  534.35   931.3   12.96 2900.76 3190.84    8.47 6412.21 7816.79    8.01
Bank Sta=3998.36,6175.31
XS Rating Curve= 0
Exp/Cntr=.3,.1