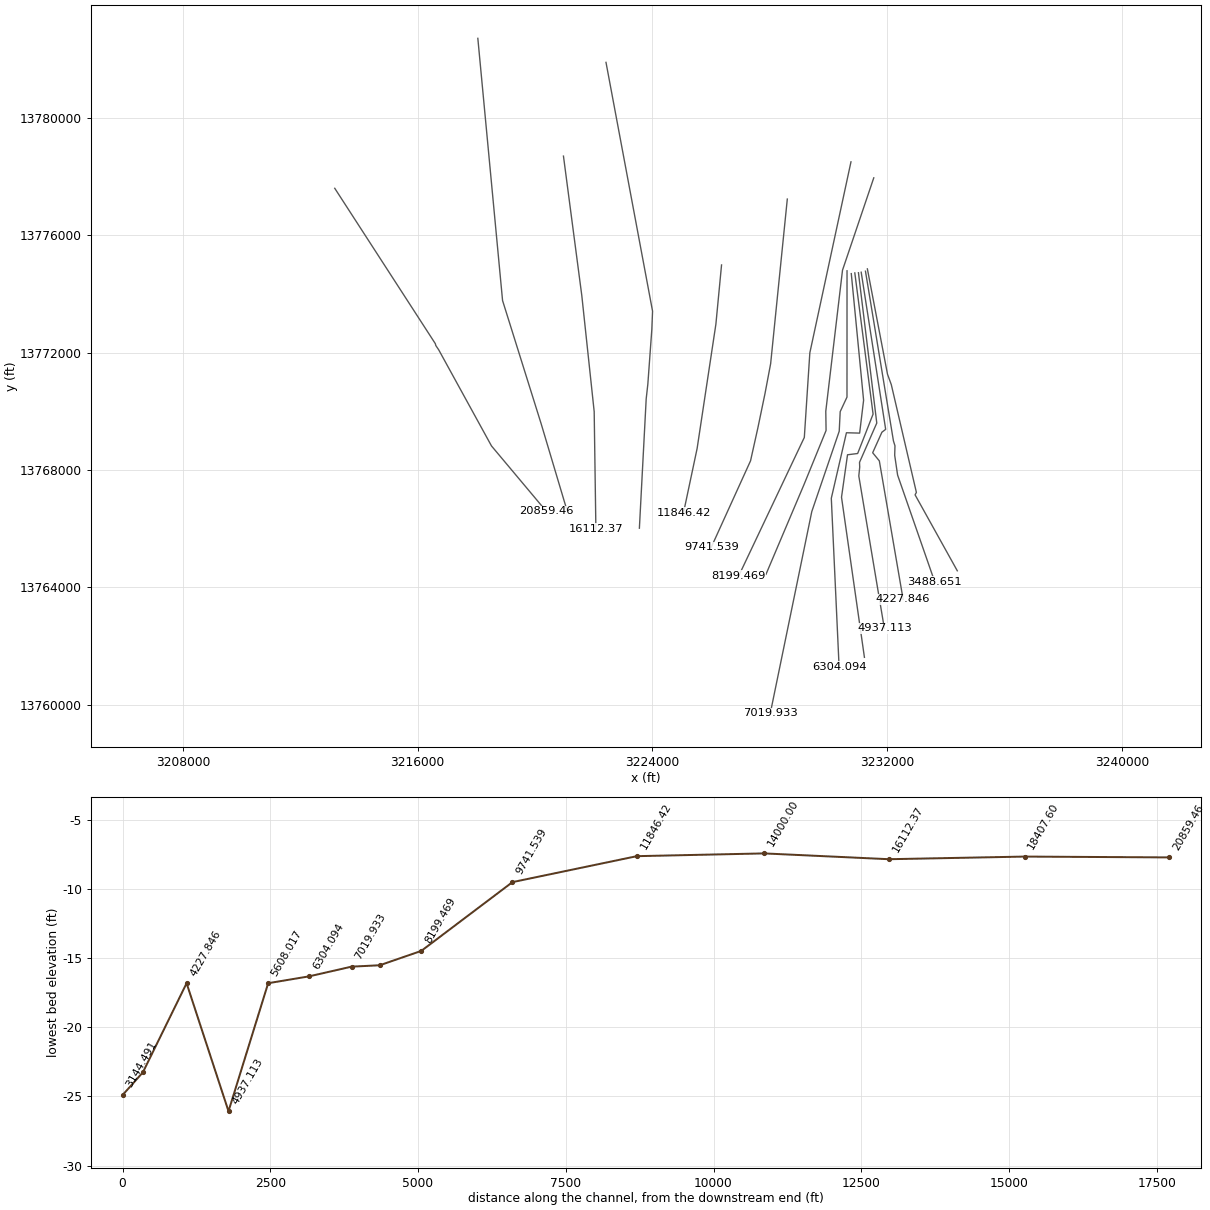
HEC-RAS study A100-00-00.prj: A100-00-00

--- A100-00-00.g01 (geometry) --- (continued)

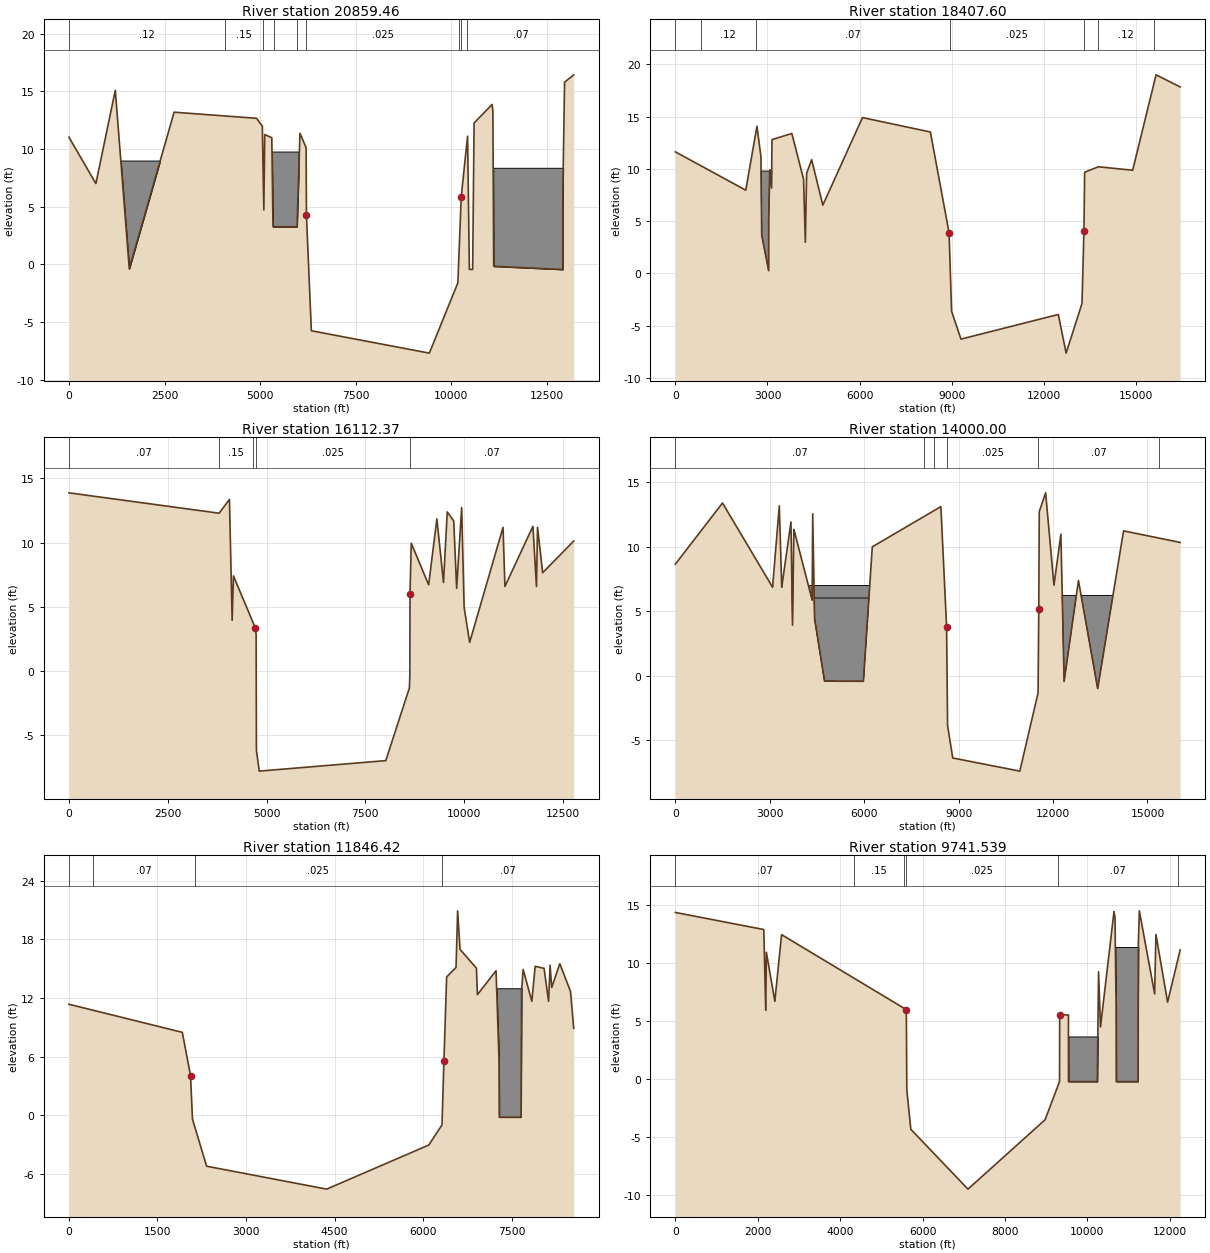
Type RM Length L Ch R = 1 ,20859.46,3215.39,2451.86,1806.43
XS GIS Cut Line= 6
     3213171.981    13777596.537     3216600.611    13772299.855
     3216616.258    13772237.891     3216714.786    13772091.934
     3218513.233    13768816.854     3220384.626    13766585.111
#Sta/Elev= 30
       0   11.04  705.45    7.01 1212.91    15.1 1578.85    -.38 2750.63    13.2
 4907.43   12.67 5057.42   11.99 5096.49    4.73 5120.13   11.26 5304.64   10.99
 5336.28    3.27 5964.88    3.27 6041.78   11.37 6202.15   10.12 6210.76    4.26
 6339.37   -5.75 9424.24   -7.6910169.73    -1.610258.16    5.8910423.75   11.12
10470.34    -.4310556.57    -.4310593.96   12.2611064.75   13.8711085.61   13.28
11106.13    -.1612911.66    -.4412914.68    6.3312959.87    15.813198.66   16.44
#Mann= 9 ,-1 , 0
       0     .12       0  4093.7     .15       0  5066.7     .07       0
  5360.9    .025       0 5962.76     .07       0 6210.76    .025       0
10208.77     .07       010245.72     .12       010416.25     .07       0
#Block Obstruct= 3 ,-1
 1047.33 2372.52    9.01 5151.15 6006.11    9.7910943.5113187.79    8.38
Bank Sta=6210.76,10258.16
XS Rating Curve= 0
Exp/Cntr=.3,.1

Type RM Length L Ch R = 1 ,18407.60,2753.48,2295.24,1803.01
XS GIS Cut Line= 4
     3218048.265    13782706.972     3218891.177    13773770.639
     3220205.239    13769575.287     3221082.626    13766633.583
#Sta/Elev= 30
       0   11.63 2293.12    7.96 2657.09   14.08 2786.99   11.18 2812.41    3.65
 3038.12     .26 3040.59    5.26 3076.17    9.92 3133.29    8.17 3146.94    12.8
 3793.86   13.39 4175.05    9.02 4233.46    2.98  4274.9    9.57  4439.1   10.88
 4803.11    6.53 6094.63   14.91 8305.97   13.53 8914.82    3.89 8996.35   -3.61
 9302.24   -6.2912473.33   -3.9312727.38   -7.6313244.07   -2.88 13307.9    4.06
13330.43    9.6813776.99    10.214894.55    9.8715656.73      1916442.09   17.84
#Mann= 7 ,-1 , 0
       0     .07       0  827.04     .12       0 2624.65     .07       0
 8933.81    .025       013296.06     .07       013776.99     .12       0
15588.25     .07       0
#Block Obstruct= 1 ,-1
 2473.28 3215.27    9.79
Bank Sta=8914.82,13307.9
XS Rating Curve= 0
Exp/Cntr=.3,.1

Type RM Length L Ch R = 1 ,16112.37,2414.11,2112.37,1900.41
XS GIS Cut Line= 4
     3220966.293    13778693.472     3221591.634    13773939.418
      3222013.58    13769985.178      3222071.46    13765984.056
#Sta/Elev= 30
       0   13.88 3801.44   12.29 4062.03   13.37 4130.59    3.94 4163.56     7.4
 4718.11    3.34 4737.43    2.82 4744.85    -6.2 4816.68   -7.82 8018.57      -7
  8615.2   -1.34 8626.22    -.46 8631.08    6.03 8662.67    9.95 9102.45    6.71
 9311.36   11.85 9478.52    6.89  9573.5   12.39  9737.5   11.69 9810.84    6.43
 9938.09   12.7310000.54    4.9610140.16    2.2210985.24   11.1911032.74    6.58
11741.45   11.2711830.74    6.5811857.51   11.1911987.74    7.6512773.22   10.12
#Mann= 5 ,-1 , 0
       0     .07       0 3801.44     .15       0 4663.12     .07       0
 4743.98    .025       0 8618.86     .07       0
Bank Sta=4718.11,8631.08
XS Rating Curve= 0
Exp/Cntr=.3,.1

Type RM Length L Ch R = 1 ,14000.00,2493.66,2153.58,1701.04
XS GIS Cut Line= 6
     3222416.053    13781888.041     3224002.756    13773408.971
     3223978.083    13772791.146     3223842.168    13770925.576
     3223785.755     13770419.18     3223554.039    13766012.697
#Sta/Elev= 30
       0    8.66 1497.12    13.4 3088.54    6.87 3301.67   13.18 3379.58    6.87
 3672.56   11.93 3721.86    3.93 3764.65   11.36 4345.82    5.88 4363.74   12.56
 4423.34    4.43 4739.59    -.42 5973.73    -.43 6256.75      10 8435.54   13.12
 8617.38     3.8 8648.52   -3.87 8812.41   -6.38 10943.4    -7.411522.92   -1.34
11546.16    5.1611561.22   12.7311763.86   14.1912028.34    7.0212248.56   10.98
12351.59    -.4412806.85    7.3913417.58      -114239.81   11.24 16038.6   10.34
#Mann= 6 ,-1 , 0
       0     .07       0 7883.77     .15       0  8220.1     .07       0
 8617.38    .025       0 11534.8     .07       015369.63     .12       0
#Block Obstruct= 3 ,-1
 2846.42 7310.58       7 4149.62 6403.05    6.03 12091.614042.75    6.23
Bank Sta=8617.38,11546.16
XS Rating Curve= 0
Exp/Cntr=.3,.1

Type RM Length L Ch R = 1 ,11846.42,2209.03,2104.89,1751
XS GIS Cut Line= 4
     3226354.039    13774983.705      3226160.71    13772962.913
     3225521.763    13768731.394     3225057.349    13766536.639
#Sta/Elev= 30
       0   11.36 1921.34    8.48 2060.67    4.05 2093.74    -.43 2333.58   -5.25
 4367.41    -7.6    6097   -3.08 6321.71   -1.01 6353.78    5.55 6399.97   14.16
 6559.07   15.14 6586.16   20.94 6626.91   16.99 6904.75   15.06 6921.11   12.34
 7236.92    14.8 7286.85    5.82 7291.35    -.22 7659.62    -.22 7669.84   12.75
 7696.45   14.93  7843.4   11.66 7899.71   15.25 8050.67   15.04 8126.88   11.66
 8153.15   15.36 8179.53   13.07 8317.16   15.52 8499.11   12.67 8552.86    8.89
#Mann= 4 ,-1 , 0
       0     .15       0  411.82     .07       0 2131.03    .025       0
 6316.46     .07       0
#Block Obstruct= 1 ,-1
 7175.57 7709.92      13
Bank Sta=2060.67,6353.78
XS Rating Curve= 0
Exp/Cntr=.3,.1

Type RM Length L Ch R = 1 ,9741.539,1302.38,1542.07,1481.49
XS GIS Cut Line= 6
     3228594.845    13777229.325     3228027.337    13771621.011
     3227834.512    13770599.989     3227588.943     13769418.48
      3227342.16    13768309.448     3226004.715    13765366.601
#Sta/Elev= 30
       0   14.33 2145.33   12.86  2193.2    5.92 2208.51   10.91 2413.63    6.69
 2577.85   12.42 5604.75    5.97  5617.4    -.95 5714.47   -4.33 7101.47   -9.48
  8972.9   -3.51 9323.81    -.22 9327.26    5.51 9539.63    5.51  9541.1    -.22
10240.37    -.2210270.47    9.2210317.97    4.4810644.86    14.410669.48   13.92
10696.57    6.2110699.82    -.22 11228.7    -.2211229.86    5.82 11237.6   11.73
11260.15   14.4711631.98    7.3211662.61   12.4411946.64    6.6112251.46   11.11
#Mann= 6 ,-1 , 0
       0     .07       0 4347.06     .15       0 5540.72     .07       0
 5598.67    .025       0 9283.91     .07       012210.04     .15       0
#Block Obstruct= 3 ,-1
 1783.85 2771.33    6.82 9447.3310280.92    3.6610558.7811328.24   11.36
Bank Sta=5604.75,9327.26
XS Rating Curve= 0
Exp/Cntr=.3,.1

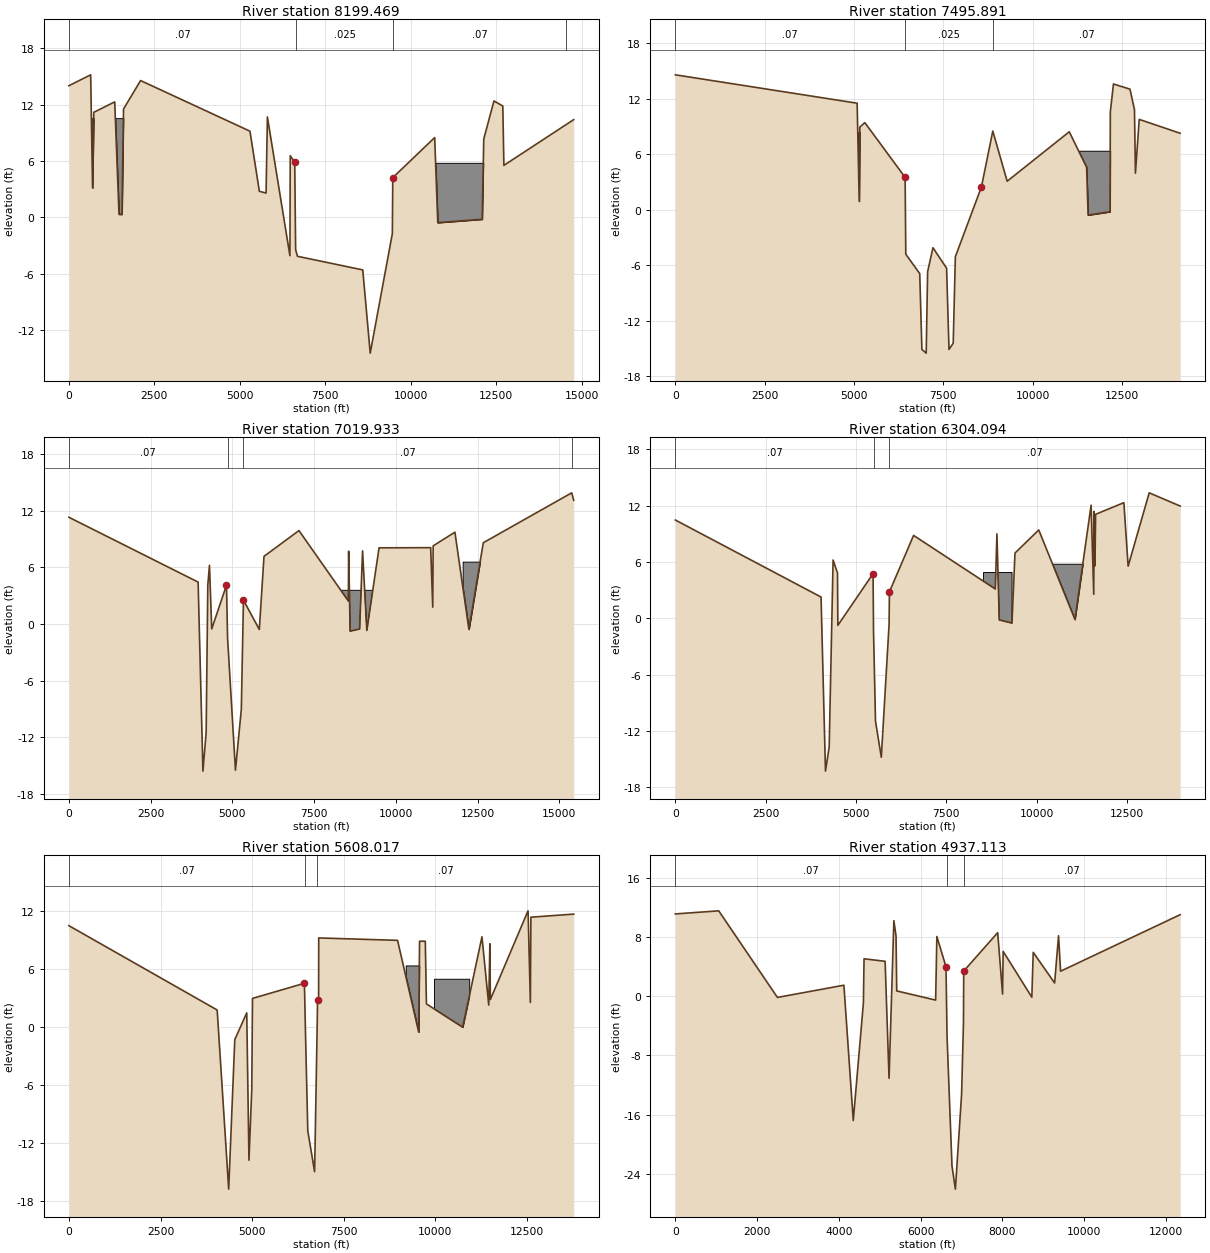
Type RM Length L Ch R = 1 ,8199.469,773.07,703.58,1985.78
XS GIS Cut Line= 4
     3230764.729    13778497.873      3229362.65    13771988.222
     3229174.613    13769105.118     3226938.071    13764384.472
#Sta/Elev= 30
       0   14.01  636.85   15.17  692.14    3.13  728.83   11.18 1340.54   12.29
 1466.45     .32 1553.17     .32 1598.28   11.53  2097.8   14.56 5297.97    9.17
 5573.57    2.77 5769.73    2.58 5808.48   10.69 6467.57   -4.09 6476.94    6.56
  6608.2    5.85 6634.66   -3.44 6688.21   -4.15 8598.97    -5.6 8817.52  -14.46
 9464.94   -1.73 9477.15    4.2210703.79    8.4910794.08    -.5712094.17    -.21
12139.98    8.3412438.45   12.3912697.21   11.8512728.59    5.5314771.83    10.4
#Mann= 4 ,-1 , 0
       0     .07       0 6655.45    .025       0 9474.21     .07       0
14554.24     .15       0
#Block Obstruct= 3 ,-1
  390.84  781.68   10.56  1245.8 1807.63   10.5610552.67 12262.6     5.8
Bank Sta=6608.2,9477.15
XS Rating Curve= 0
Exp/Cntr=.3,.1

Type RM Length L Ch R = 1 ,7495.891,709.85,475.96,549.29
XS GIS Cut Line= 6
     3231541.695    13777952.998     3230476.273    13774806.287
     3229906.396      13769999.5     3229915.985    13769342.908
     3229163.078    13767496.998     3227868.738    13764442.639
#Sta/Elev= 30
       0    14.6 5088.25   11.53 5146.11     .92 5163.06    8.95 5303.21    9.43
 6431.18    3.51    6450    -4.8    6840    -6.9    6901   -15.1    7021   -15.5
    7061    -6.7    7210    -4.1 7591.96   -6.31  7659.6   -15.1 7777.01  -14.43
 7837.48   -5.07 8567.09    2.47  8885.4    8.52 9287.69    3.0911025.98    8.44
11511.49     4.611552.59    -.5712166.78    -.2112175.39   10.5912263.22   13.61
12725.37   13.05 12851.1   10.8312877.73    3.9612984.09    9.7814130.29    8.28
#Mann= 3 ,-1 , 0
       0     .07       0 6431.18    .025       0  8885.4     .07       0
#Block Obstruct= 2 ,-1
 4934.35 5276.34     8.410821.3712360.31    6.39
Bank Sta=6431.18,8567.09
XS Rating Curve= 0
Exp/Cntr=.3,.1

Type RM Length L Ch R = 1 ,7019.933,1035.84,715.84,299.42
XS GIS Cut Line= 6
     3230630.266    13774785.137     3230628.798    13770480.623
     3230397.518    13769985.253     3230364.135    13769317.597
     3229429.416    13766580.205     3228014.154    13759702.056
#Sta/Elev= 30
       0    11.3 3951.92    4.43    4099   -15.6    4198   -11.5 4247.83     4.1
 4298.97    6.21  4368.1    -.53 4819.74     4.1 4852.25   -1.46 5093.87   -15.5
 5273.07   -9.06 5338.62    2.52 5823.83    -.59    5967    7.16 7036.01    9.89
 8546.69    2.43 8555.81     7.7 8601.11    -.77 8891.87    -.54  8981.2    7.74
 9111.66    -.69 9485.71    8.0611064.35    8.0811127.66    1.7811140.56    8.27
11805.65    9.7212233.92    -.58 12673.6     8.615378.82   13.8915438.91    13.1
#Mann= 4 ,-1 , 0
       0     .07       0 4852.25    .035       0 5338.62     .07       0
15378.82     .15       0
#Block Obstruct= 2 ,-1
 8329.77  9331.3    3.5612042.7512970.99     6.6
Bank Sta=4819.74,5338.62
XS Rating Curve= 0
Exp/Cntr=.3,.1

Type RM Length L Ch R = 1 ,6304.094,468.74,696.08,355.4
XS GIS Cut Line= 6
     3230775.079    13774688.595     3231195.036    13770373.168
     3231059.877    13769253.281     3230609.898    13769265.579
     3230094.458    13767032.815      3230360.21     13761282.25
#Sta/Elev= 30
       0   10.47 4032.41    2.26    4155   -16.3    4258   -13.7 4365.79    6.21
 4487.79    4.82 4497.35    -.76 5472.05    4.75 5484.73   -1.36 5539.79  -10.98
 5700.47  -14.82 5916.22    -.62 5924.76    2.81 6593.79    8.83  8855.7    3.12
 8900.75    8.99  8966.1    -.18 9316.75    -.52  9400.7    6.9510058.85    9.41
11060.33    -.1311507.58   12.0511580.75    2.5611592.08   11.3911614.72    5.59
11632.02   11.0812414.32   12.3212532.64    5.5513115.99   13.3713972.87   11.96
#Mann= 3 ,-1 , 0
       0     .07       0 5484.73    .035       0 5916.22     .07       0
#Block Obstruct= 2 ,-1
 8528.24 9319.08    4.8710345.0411370.99    5.81
Bank Sta=5472.05,5924.76
XS Rating Curve= 0
Exp/Cntr=.3,.1

Type RM Length L Ch R = 1 ,5608.017,168.35,670.9,716.82
XS GIS Cut Line= 6
     3230895.756     13774712.73     3231518.038     13769900.35
     3230992.298    13768558.178     3230646.965    13768514.974
     3230442.324    13767068.905     3231223.015    13761611.861
#Sta/Elev= 30
       0   10.51  4045.6    1.77    4360   -16.8    4526    -1.3 4852.45    1.47
    4913   -13.8    4989    -6.5  5009.5    2.97 6426.11    4.54 6455.08    -.57
 6518.25  -10.76 6704.12  -14.99 6775.24     .31  6783.9    2.81 6813.18    2.81
 6816.42    9.24 8967.26    8.99 9543.94    -.52 9567.74     8.9 9724.25     8.9
 9755.41     2.410744.33    -.01 11270.6    9.3611455.63    2.2811486.07    8.63
11499.65    2.8512527.79   12.0512591.44    2.56 12605.5   11.3913773.78   11.71
#Mann= 3 ,-1 , 0
       0     .07       0 6455.08    .035       0 6775.24     .07       0
#Block Obstruct= 2 ,-1
 9190.84 9575.57    6.39 9960.3110922.14    5.01
Bank Sta=6426.11,6783.9
XS Rating Curve= 0
Exp/Cntr=.3,.1

Type RM Length L Ch R = 1 ,4937.113,530.88,709.27,784.49
XS GIS Cut Line= 6
     3231019.432     13774718.75     3231643.957    13769596.005
     3231056.272    13768257.475     3231062.249    13768091.519
     3231031.437     13767793.67     3231901.626    13762600.695
#Sta/Elev= 30
       0   11.11 1061.36   11.53 2497.73    -.17 4124.98    1.48    4354   -16.8
 4602.26    -.92 4618.03    5.05 5133.54    4.71    5230   -11.1 5347.56    10.2
  5400.7    8.15 5417.77     .71 6370.34    -.53 6400.05    8.06 6623.99    3.97
 6649.54   -5.47 6770.61  -22.95 6853.77  -26.07 7005.31  -13.28 7051.07   -3.63
 7057.75    3.39  7888.9    8.58 8008.46     .29 8022.96    6.05 8724.62    -.14
 8758.61    5.92  9282.5    1.78 9378.54    8.16 9428.02    3.3712355.36   11.01
#Mann= 3 ,-1 , 0
       0     .07       0 6649.54    .035       0 7057.75     .07       0
Bank Sta=6623.99,7057.75
XS Rating Curve= 0
Exp/Cntr=.5,.3

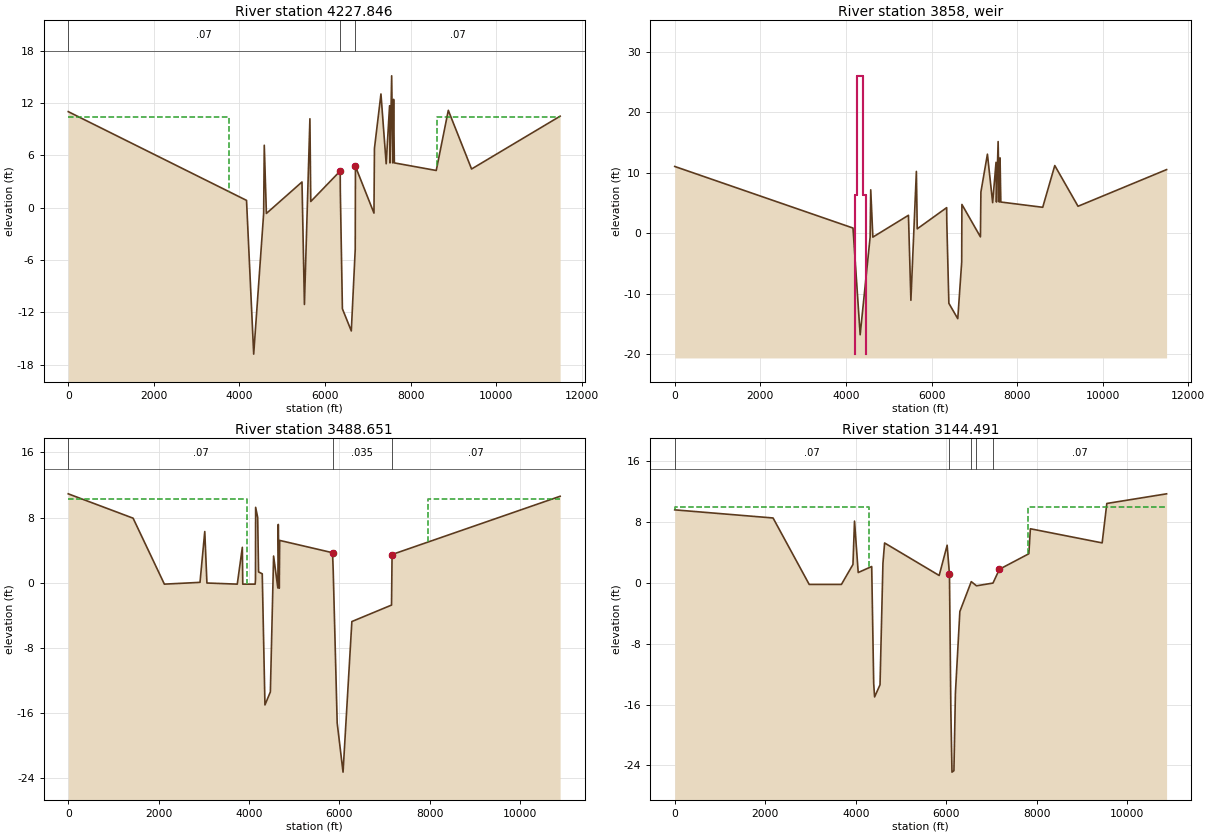
Type RM Length L Ch R = 1 ,4227.846,300.42,739.2,556.32
XS GIS Cut Line= 6
     3231112.976    13774736.866     3231947.132    13769381.369
     3231819.207    13769284.113     3231504.138    13768584.474
     3231731.173    13768306.472      3232541.46    13763589.528
#Sta/Elev= 30
       0   11.02 4165.49     .84    4333   -16.8 4565.71    -.66 4580.03    7.16
  4629.6    -.66 5461.43    2.95 5518.41   -11.1 5646.55    10.2 5666.48     .71
 6354.21    4.21 6356.98    1.93 6405.75   -11.6 6613.77  -14.14 6705.61   -4.77
 6710.44    4.74  7143.3    -.62 7154.41     6.8 7306.48   13.05 7428.79    5.04
 7507.76    11.7 7517.75    5.14 7556.66   15.13 7582.89    5.14 7601.69   12.43
 7619.53    5.14 8598.55    4.27 8880.49   11.17 9423.92    4.4411493.03    10.5
#Mann= 3 ,-1 , 0
       0     .07       0 6356.98    .035       0 6710.44     .07       0
#XS Ineff= 2 ,-1
       0  3759.6   10.35 8617.3611493.03   10.35
Permanent Ineff=
       F       F
Bank Sta=6354.21,6710.44
XS Rating Curve= 0
Exp/Cntr=.5,.3

Type RM Length L Ch R = 5 ,3858    ,,,
BEGIN DESCRIPTION:
Clear Creek 2nd Outlet Gated Structure
END DESCRIPTION:
IW Pilot Flow=0
#Inline Weir SE= 8
  4201.5     -20  4201.5    6.33  4262.5    6.33  4262.5      26  4403.5      26
  4403.5    6.33  4464.5    6.33  4464.5     -20
IW Dist,WD,Coef,Skew,MaxSub,Min_El,Is_Ogee,SpillHt,DesHd
361,20,3,0,.95,, 0 ,,,0,0,
IW Gate Name Wd,H,Inv,GCoef,Exp_T,Exp_O,Exp_H,Type,WCoef,Is_Ogee,SpillHt,DesHd,#Openings
Gate #1     ,20,20,-15,.6,0,1,.5, 0 ,3, 0 ,,, 6 ,0,.8
  4275.5  4298.5  4321.5  4344.5  4367.5  4390.5

Type RM Length L Ch R = 1 ,3488.651,354.03,344.16,474.23
XS GIS Cut Line= 6
     3231258.461    13774770.867     3232212.086    13768986.534
      3232264.01    13768820.776     3232254.743     13768496.44
     3232353.818    13767822.981     3233616.457    13764192.894
#Sta/Elev= 30
       0   10.92 1434.92    7.93 2127.48    -.17 2915.68     .05 3021.07    6.29
 3068.86    -.03 3740.69    -.17 3852.56    4.35 3861.88    -.17 4136.01    -.17
 4143.32     .33 4146.91    9.26 4191.87    8.02 4211.55    1.33    4293     1.1
    4353     -15    4473   -13.4 4544.32    3.28 4638.29    -.64 4647.91    7.16
 4669.91    -.66 4679.35     5.2 5848.77    3.69 5863.63    1.51 5951.64  -17.22
 6081.44  -23.25 6276.47   -4.76 7154.28   -2.74 7166.35    3.4710885.48   10.62
#Mann= 3 ,-1 , 0
       0     .07       0 5863.63    .035       0 7154.28     .07       0
#XS Ineff= 2 ,-1
       0 3964.82   10.24 7966.4310885.48   10.24
Permanent Ineff=
       F       F
Bank Sta=5848.77,7166.35
XS Rating Curve= 0
Exp/Cntr=.5,.3

Type RM Length L Ch R = 1 ,3144.491,94.21,90.31,88.56
XS GIS Cut Line= 6
     3231323.451    13774850.299     3232009.451    13771261.434
     3232139.208    13770903.939     3232993.755    13767233.328
     3232949.127    13767149.838      3234388.07    13764561.164
#Sta/Elev= 30
       0    9.63  2172.8    8.56 2971.53    -.19 3682.77    -.19 3937.96    2.44
 3972.44    8.15 4054.04    1.38 4352.15    2.17    4396   -13.2    4416     -15
    4536   -13.4  4600.4    2.59 4637.27    5.27 5843.12     .99 6018.87    4.97
 6070.28    1.14 6100.71  -16.64 6126.08   -24.9 6168.87  -24.71  6201.6  -14.52
 6299.77   -3.76 6552.01     .18 6667.36    -.37  7031.9    -.01 7173.98    1.81
 7824.37    3.85 7857.84    7.14 9444.08    5.28 9547.09   10.4710867.54   11.74
#Mann= 5 ,-1 , 0
       0     .07       0 6070.28    .035       0 6552.01     .07       0
 6667.36    .035       0  7031.9     .07       0
#XS Ineff= 2 ,-1
       0 4298.87      10 7808.2210867.54      10
Permanent Ineff=
       F       F
Bank Sta=6070.28,7173.98
XS Rating Curve= 0
Exp/Cntr=.5,.3