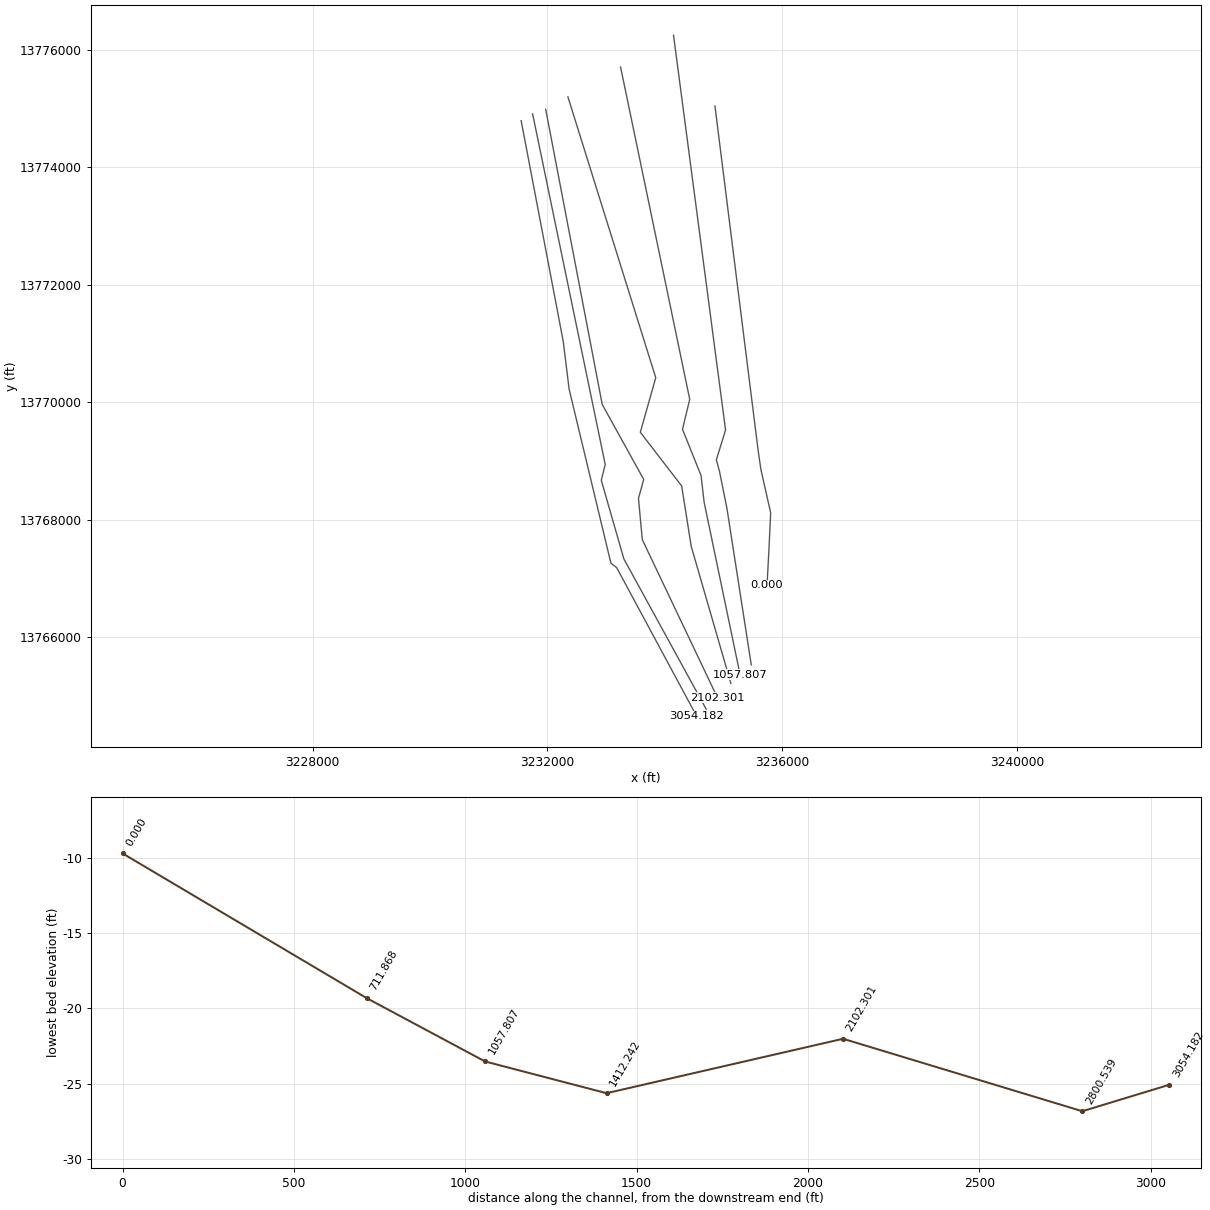
HEC-RAS study A100-00-00.prj: A100-00-00

--- A100-00-00.g01 (geometry) --- (continued)

Type RM Length L Ch R = 3 ,3064    ,,,
BEGIN DESCRIPTION:
SH146
END DESCRIPTION:
Bridge Culvert--1,0,-1,-1, 0
Deck Dist Width WeirC Skew NumUp NumDn MinLoCord MaxHiCord MaxSubmerge Is_Ogee
5,81,2.6,0, 72, 72, , , .95, 0, 0,0,,
       0     585    1049    1199    1579    3223    3710    3798    3885    3886
    3990    4045    4046    4089    4134    4183    4227    4298    4299    4379
    4459    4539    4619    4700    4780    4861    4941    5036    5131    5226
    5321    5416    5511    5606    5701    5796    5891    5987    6096    6231
    6367    6477    6572    6667    6762    6857    6951    7047    7142    7237
    7332    7427    7522    7617    7714    7809    7810    7954    7971    7972
    8154    8297    8795    9009    9192    9559    9949   10361   10599   10839
   10909   11089
    10.8      10     9.6      10    10.6    10.7    10.7    9.75   11.27    9.98
   11.59   11.47   11.53   11.28    11.5   11.72    12.5   14.01   14.01   16.38
   19.54   22.92   26.32   29.77   33.31   36.84   40.34    44.5   48.66   52.59
   56.74   60.86   64.96   69.06   73.14   77.18   80.67   83.23   84.91   85.37
   83.91   81.48   78.24   74.06   69.34   64.64   59.87   55.16   50.39   45.88
    40.9   36.65   32.42   28.16   23.87   19.69   19.69   14.49      13   12.27
   11.57   11.95    10.5    10.3    10.7      10      10    11.3      12      12
    11.5      12
                                                                                
                                                                    5.96    8.33
   11.49   14.88   18.27    21.7   25.27    28.8   32.29   36.48   40.58   44.51
   48.66   52.78   56.88   60.98   65.06    69.1   72.59   75.15   76.83   77.29
   75.83    73.4   70.16   65.98   61.26   56.56   51.79   47.11   42.33   37.55
   32.85    28.6   24.37   20.11   15.82   11.63
                                                                                
                
       0     486     950    1100    1480    3124    3611    3699    3786    3787
    3891    3946    3947    3990    4035    4084    4128    4199    4200    4280
    4360    4440    4520    4601    4681    4762    4842    4937    5032    5127
    5222    5317    5412    5507    5602    5697    5792    5888    5997    6132
    6268    6378    6473    6568    6663    6758    6852    6948    7043    7138
    7233    7328    7423    7518    7615    7710    7711    7855    7872    7873
    8055    8198    8696    8910    9093    9460    9850   10262   10500   10740
   10810   10990
    10.8      10     9.6      10    10.6    10.7    10.7    9.75   11.27    9.98
   11.59   11.47   11.53   11.28    11.5   11.72    12.5   14.01   14.01   16.38
   19.54   22.92   26.32   29.77   33.31   36.84   40.34    44.5   48.66   52.59
   56.74   60.86   64.96   69.06   73.14   77.18   80.67   83.23   84.91   85.37
   83.91   81.48   78.24   74.06   69.34   64.64   59.87   55.16   50.39   45.88
    40.9   36.65   32.42   28.16   23.87   19.69   19.69   14.49      13   12.27
   11.57   11.95    10.5    10.3    10.7      10      10    11.3      12      12
    11.5      12
                                                                                
                                                                    5.96    8.33
   11.49   14.88   18.27    21.7   25.27    28.8   32.29   36.48   40.58   44.51
   48.66   52.78   56.88   60.98   65.06    69.1   72.59   75.15   76.83   77.29
   75.83    73.4   70.16   65.98   61.26   56.56   51.79   47.11   42.33   37.55
   32.85    28.6   24.37   20.11   15.82   11.63
                                                                                
                
Pier Skew, UpSta & Num, DnSta & Num=  ,4379, 2 ,4280, 2 , 0 , 0 , 0 ,,
       3       3
     -30      80
       3       3
     -30      80
Pier Skew, UpSta & Num, DnSta & Num=  ,4459, 2 ,4360, 2 , 0 , 0 , 0 ,,
       3       3
     -30      80
       3       3
     -30      80
Pier Skew, UpSta & Num, DnSta & Num=  ,4539, 2 ,4440, 2 , 0 , 0 , 0 ,,
       3       3
     -30      80
       3       3
     -30      80
Pier Skew, UpSta & Num, DnSta & Num=  ,4619, 2 ,4520, 2 , 0 , 0 , 0 ,,
       3       3
     -30      80
       3       3
     -30      80
Pier Skew, UpSta & Num, DnSta & Num=  ,4700, 2 ,4601, 2 , 0 , 0 , 0 ,,
       3       3
     -30      80
       3       3
     -30      80
Pier Skew, UpSta & Num, DnSta & Num=  ,4780, 2 ,4681, 2 , 0 , 0 , 0 ,,
       3       3
     -30      80
       3       3
     -30      80
Pier Skew, UpSta & Num, DnSta & Num=  ,4861, 2 ,4762, 2 , 0 , 0 , 0 ,,
       3       3
     -30      80
       3       3
     -30      80
Pier Skew, UpSta & Num, DnSta & Num=  ,4941, 2 ,4842, 2 , 0 , 0 , 0 ,,
       3       3
     -30      80
       3       3
     -30      80
Pier Skew, UpSta & Num, DnSta & Num=  ,5036, 2 ,4937, 2 , 0 , 0 , 0 ,,
       3       3
     -30      80
       3       3
     -30      80
Pier Skew, UpSta & Num, DnSta & Num=  ,5131, 2 ,5032, 2 , 0 , 0 , 0 ,,
       3       3
     -30      80
       3       3
     -30      80
Pier Skew, UpSta & Num, DnSta & Num=  ,5226, 2 ,5127, 2 , 0 , 0 , 0 ,,
       3       3
     -30      80
       3       3
     -30      80
Pier Skew, UpSta & Num, DnSta & Num=  ,5321, 2 ,5222, 2 , 0 , 0 , 0 ,,
       3       3
     -30      80
       3       3
     -30      80
Pier Skew, UpSta & Num, DnSta & Num=  ,5416, 2 ,5317, 2 , 0 , 0 , 0 ,,
       3       3
     -30      80
       3       3
     -30      80
Pier Skew, UpSta & Num, DnSta & Num=  ,5521, 2 ,5412, 2 , 0 , 0 , 0 ,,
       3       3
     -30      80
       3       3
     -30      80
Pier Skew, UpSta & Num, DnSta & Num=  ,5606, 2 ,5507, 2 , 0 , 0 , 0 ,,
       3       3
     -30      80
       3       3
     -30      80
Pier Skew, UpSta & Num, DnSta & Num=  ,5701, 2 ,5602, 2 , 0 , 0 , 0 ,,
       3       3
     -30      80
       3       3
     -30      80
Pier Skew, UpSta & Num, DnSta & Num=  ,5796, 2 ,5697, 2 , 0 , 0 , 0 ,,
       3       3
     -30      80
       3       3
     -30      80
Pier Skew, UpSta & Num, DnSta & Num=  ,5891, 2 ,5792, 2 , 0 , 0 , 0 ,,
       3       3
     -30      80
       3       3
     -30      80
Pier Skew, UpSta & Num, DnSta & Num=  ,5987, 2 ,5888, 2 , 0 , 0 , 0 ,,
       3       3
     -30      80
       3       3
     -30      80
Pier Skew, UpSta & Num, DnSta & Num=  ,6096, 2 ,5997, 2 , 0 , 0 , 0 ,,
       3       3
     -30      80
       3       3
     -30      80
Pier Skew, UpSta & Num, DnSta & Num=  ,6231, 2 ,6132, 2 , 0 , 0 , 0 ,,
       3       3
     -30      80
       3       3
     -30      80
Pier Skew, UpSta & Num, DnSta & Num=  ,6367, 2 ,6268, 2 , 0 , 0 , 0 ,,
       3       3
     -30      80
       3       3
     -30      80
Pier Skew, UpSta & Num, DnSta & Num=  ,6477, 2 ,6378, 2 , 0 , 0 , 0 ,,
       3       3
     -30      80
       3       3
     -30      80
Pier Skew, UpSta & Num, DnSta & Num=  ,6572, 2 ,6473, 2 , 0 , 0 , 0 ,,
       3       3
     -30      80
       3       3
     -30      80
Pier Skew, UpSta & Num, DnSta & Num=  ,6667, 2 ,6568, 2 , 0 , 0 , 0 ,,
       3       3
     -30      80
       3       3
     -30      80
Pier Skew, UpSta & Num, DnSta & Num=  ,6762, 2 ,6663, 2 , 0 , 0 , 0 ,,
       3       3
     -30      80
       3       3
     -30      80
Pier Skew, UpSta & Num, DnSta & Num=  ,6857, 2 ,6758, 2 , 0 , 0 , 0 ,,
       3       3
     -30      80
       3       3
     -30      80
Pier Skew, UpSta & Num, DnSta & Num=  ,6951, 2 ,6852, 2 , 0 , 0 , 0 ,,
       3       3
     -30      80
       3       3
     -30      80
Pier Skew, UpSta & Num, DnSta & Num=  ,7047, 2 ,6948, 2 , 0 , 0 , 0 ,,
       3       3
     -30      80
       3       3
     -30      80
Pier Skew, UpSta & Num, DnSta & Num=  ,7142, 2 ,7043, 2 , 0 , 0 , 0 ,,
       3       3
     -30      80
       3       3
     -30      80
Pier Skew, UpSta & Num, DnSta & Num=  ,7237, 2 ,7138, 2 , 0 , 0 , 0 ,,
       3       3
     -30      80
       3       3
     -30      80
Pier Skew, UpSta & Num, DnSta & Num=  ,7332, 2 ,7233, 2 , 0 , 0 , 0 ,,
       3       3
     -30      80
       3       3
     -30      80
Pier Skew, UpSta & Num, DnSta & Num=  ,7427, 2 ,7328, 2 , 0 , 0 , 0 ,,
       3       3
     -30      80
       3       3
     -30      80
Pier Skew, UpSta & Num, DnSta & Num=  ,7522, 2 ,7423, 2 , 0 , 0 , 0 ,,
       3       3
     -30      80
       3       3
     -30      80
Pier Skew, UpSta & Num, DnSta & Num=  ,7617, 2 ,7518, 2 , 0 , 0 , 0 ,,
       3       3
     -30      80
       3       3
     -30      80
Pier Skew, UpSta & Num, DnSta & Num=  ,7714, 2 ,7615, 2 , 0 , 0 , 0 ,,
       3       3
     -30      80
       3       3
     -30      80
Pier Skew, UpSta & Num, DnSta & Num=  ,7807, 2 ,7708, 2 , 0 , 0 , 0 ,,
       3       3
     -30      80
       3       3
     -30      80
BR Coef=-1 , 1 , 1 ,1.05, 0 ,,,.8,-1,1.2,0,
WSPro=,,,, 1 ,,,, 0 ,,,, 0 ,,,,-1 ,-1 ,-1 , 0 , 0 , 0 , 0 , 0
BC Design=,, 0 ,, 0 ,,,,,,
BC HTab HWMax=12.95

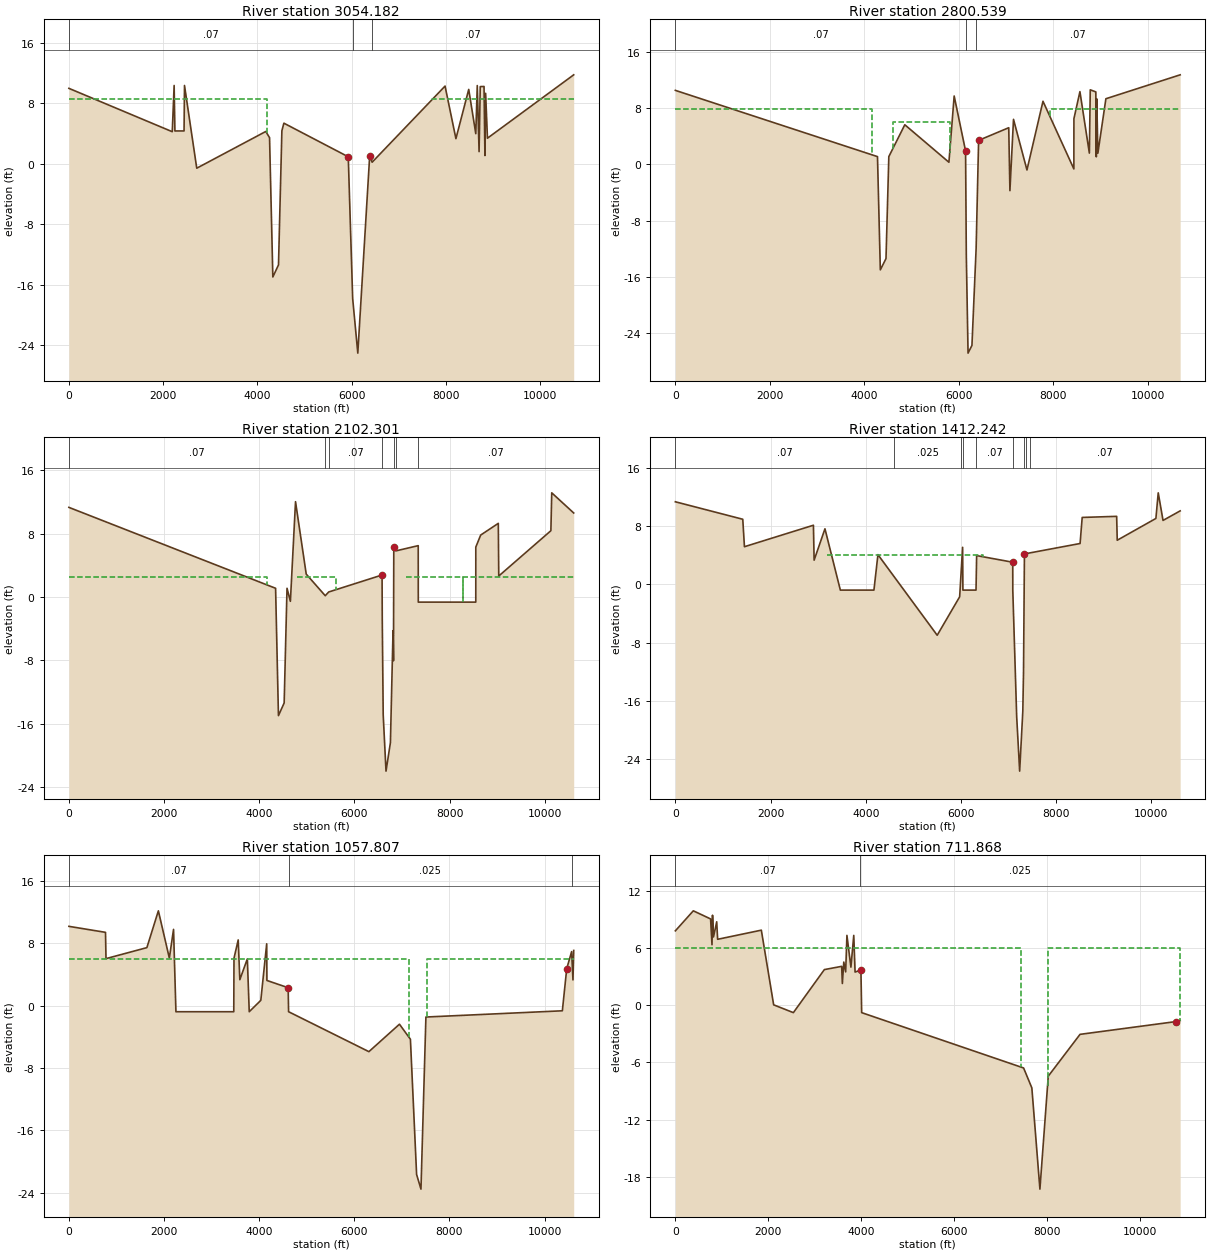
Type RM Length L Ch R = 1 ,3054.182,352.75,253.64,210.01
XS GIS Cut Line= 6
     3231551.075    13774797.627     3232267.656     13771040.22
     3232368.743    13770221.271     3233080.372    13767258.804
     3233179.262    13767181.538     3234544.042    13764646.947
#Sta/Elev= 30
       0    9.97 2193.03    4.23 2232.54   10.35 2248.97    4.33  2443.1    4.33
  2452.5   10.35 2712.42     -.6 4177.01    4.26 4257.15    3.44    4327     -15
    4447   -13.4 4518.89    4.36 4561.32    5.36  5927.1     .91 6020.74  -17.85
 6129.49  -25.08 6382.06    1.07 6433.11     .19 7980.71   10.27 8211.24    3.31
 8483.11    9.83 8632.78    3.97 8664.25   10.34 8702.64     1.6  8727.5    10.2
 8807.62   10.22 8826.58    1.08  8841.6    9.31 8880.19    3.3710710.34   11.76
#Mann= 3 ,-1 , 0
       0     .07       0 6020.74    .035       0 6433.11     .07       0
#XS Ineff= 2 ,-1
       0 4200.49    8.56 7702.7710710.34    8.56
Permanent Ineff=
       F       F
Bank Sta=5927.1,6382.06
XS Rating Curve= 0
Exp/Cntr=.5,.3

Type RM Length L Ch R = 1 ,2800.539,522.98,698.24,480.9
XS GIS Cut Line= 5
     3231746.515    13774912.639     3232983.477    13768940.106
     3232916.343    13768671.572     3233300.797    13767331.954
     3234703.729    13764771.603
#Sta/Elev= 30
       0   10.52    4280     1.1    4340     -15    4460   -13.4    4520     1.1
 4858.41    5.63 5792.37      .3 5903.57    9.72 6145.07    1.91  6160.7   -12.9
 6197.61  -26.84 6279.97  -25.74 6368.51  -11.97 6421.22    3.41 7059.24    5.21
 7084.04   -3.74 7160.05     6.4 7444.92     -.8 7784.26    8.97 8438.32    -.65
 8439.19    6.49 8566.56   10.34 8766.44     1.6 8785.49    10.6 8903.11    10.3
 8913.34    1.08 8923.04    9.31 8946.65    1.59 9116.45    9.33 10689.3   12.73
#Mann= 3 ,-1 , 0
       0     .07       0  6160.7    .035       0 6368.51     .07       0
#XS Ineff= 3 ,-1
       0 4172.14    7.84 7923.12 10689.3    7.84    4600 5807.94       6
Permanent Ineff=
       F       F       F
Bank Sta=6145.07,6421.22
XS Rating Curve= 0
Exp/Cntr=.5,.3

Type RM Length L Ch R = 1 ,2102.301,498.02,690.06,785.54
XS GIS Cut Line= 6
     3231969.488    13774990.195     3232932.528    13769962.452
     3233639.276    13768685.487     3233550.076    13768362.139
     3233614.669    13767660.846     3234896.633    13764964.507
#Sta/Elev= 30
       0   11.33    4343     1.1    4403     -15    4523   -13.4    4583     1.1
 4653.89    -.55  4761.7   12.05 4986.69    2.89 5386.48     .16 5458.18     .63
 6580.27    2.78 6584.12    -2.7 6604.12  -14.91 6663.05  -22.02 6755.59  -18.42
 6810.73   -4.27 6820.02   -8.06 6826.69    6.49 6828.13    6.36 6870.55    5.83
 7339.89    6.49 7341.35    -.65 8549.48    -.65 8549.83    6.31  8652.6    7.83
 9022.56    9.31  9032.1    2.6510127.34    8.3810145.48   13.1710606.96   10.62
#Mann= 7 ,-1 , 0
       0     .07       0 5386.48    .025       0 5458.18     .07       0
 6584.12    .035       0 6826.69     .07       0 6870.55     .15       0
 7339.89     .07       0
#XS Ineff= 4 ,-1
       0 4153.26     2.5    4800 5608.19     2.5 7083.23 8281.28     2.5
 8281.2810606.96     2.5
Permanent Ineff=
       F       F       F       F
Bank Sta=6580.27,6828.13
XS Rating Curve= 0
Exp/Cntr=.5,.3

Type RM Length L Ch R = 1 ,1412.242,591.23,354.43,407.86
XS GIS Cut Line= 6
     3232347.571    13775203.472     3233844.434    13770418.405
     3233581.384    13769488.962     3234285.971    13768573.988
     3234449.055    13767543.517     3235124.609     13765210.02
#Sta/Elev= 30
       0   11.35 1416.49    8.95  1451.7    5.18 2901.61    8.13 2916.07    3.33
 3143.91    7.64 3467.54    -.78 4173.19    -.78 4257.38    4.09 5502.91   -6.98
 5974.77    -1.7 6037.13     5.1 6042.95    -.78 6318.82    -.78 6331.77    3.96
 7090.77    3.05 7091.48    -.77  7173.5  -18.17 7235.93  -25.64 7302.05  -17.42
  7317.3  -11.97 7336.26    4.19 8505.88    5.62 8550.27     9.2 9274.51    9.35
 9286.71    6.0710099.28    9.0610148.27   12.5810249.34    8.79 10609.5    10.1
#Mann= 9 ,-1 , 0
       0     .07       0 4591.26    .025       0 6006.15     .07       0
 6037.13    .025       0 6312.23     .07       0 7094.57    .035       0
 7336.26     .07       0 7361.62     .15       0 7446.39     .07       0
#XS Ineff= 1 ,-1
 3180.54 6468.63       4
Permanent Ineff=
       F
Bank Sta=7090.77,7336.26
XS Rating Curve= 0
Exp/Cntr=.3,.1

Type RM Length L Ch R = 1 ,1057.807,389.25,345.94,385.66
XS GIS Cut Line= 6
     3233245.056     13775711.31     3234423.143    13770050.135
     3234300.113    13769540.306     3234616.046    13768752.423
     3234668.656     13768296.47     3235280.666    13765361.578
#Sta/Elev= 30
       0   10.17  769.46     9.4  779.71    6.03 1639.35    7.44 1880.89   12.16
  2111.6     6.1 2199.81    9.78 2250.03    -.78 3466.23    -.78 3470.68    6.08
 3559.42    8.43 3593.54    3.33 3751.56       6 3791.35    -.78 4034.62     .68
 4158.26    7.93 4162.88    3.23 4609.65     2.3 4618.55    -.78 6307.08    -5.9
  6949.4   -2.38  7179.8   -4.31 7309.92  -21.65 7401.53  -23.53 7505.58   -1.46
10374.18    -.6610465.99    4.7410569.07    6.93 10597.2     3.310612.79    7.08
#Mann= 3 ,-1 , 0
       0     .07       0 4618.55    .025       010569.07     .07       0
#XS Ineff= 2 ,-1
       0 7142.94       6 7530.6210612.79       6
Permanent Ineff=
       F       F
Bank Sta=4609.65,10465.99
XS Rating Curve= 0
Exp/Cntr=.5,.3

Type RM Length L Ch R = 1 ,711.868 ,740.37,711.87,687.15
XS GIS Cut Line= 6
 3234147.080579713776253.1395905      3235033.64    13769527.064
     3234876.916    13769019.984     3234932.829    13768811.509
     3235057.751    13768188.892 3235471.778879713765525.5982451
#Sta/Elev= 30
       0    7.81     386    9.91   757.6    9.06  788.05    6.35  799.25    9.45
  820.67    7.17  889.45    8.76   909.3    6.92 1849.64    7.88 2114.86     .04
 2538.77    -.78 3205.94    3.74  3578.4    4.08 3592.85    2.28 3623.83    4.53
 3663.97     3.5 3691.29    7.33 3777.02       4 3838.32    7.33 3866.66    3.48
 3979.52    3.67 3992.54    3.67 4008.37    -.78 7492.42   -6.59  7670.1   -8.68
 7843.57  -19.31 8023.27   -7.45 8706.68   -3.0610767.47   -1.7210861.42   -1.61
#Mann= 2 ,-1 , 0
       0     .07       0 3979.52    .025       0
#XS Ineff= 2 ,-1
       0 7432.69       6 8008.3410861.42       6
Permanent Ineff=
       F       F
Bank Sta=3992.54,10767.47
XS Rating Curve= 0
Exp/Cntr=.5,.3

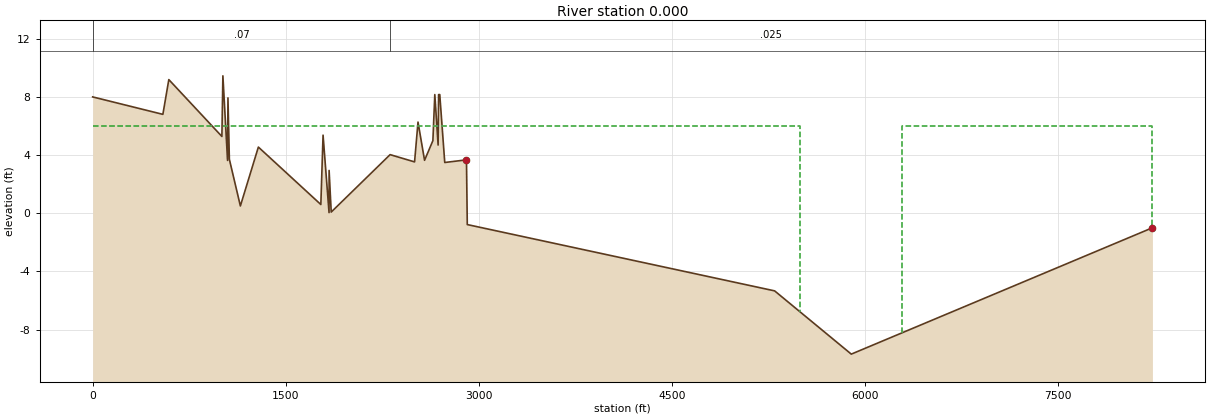
Type RM Length L Ch R = 1 ,0.000   ,0,0,0
XS GIS Cut Line= 6
 3234852.883654713775048.1214266     3235590.511    13769164.933
       3235637.1    13768848.576      3235802.36    13768116.841
     3235773.465    13767507.321 3235740.602214313766885.2060638
#Sta/Elev= 30
       0       8  545.53     6.8  591.66    9.19 1003.95    5.28 1011.69    9.45
 1047.81    3.63 1051.02    7.93 1061.96    3.71 1147.52      .5 1287.35    4.55
 1772.57      .6 1789.81    5.37 1836.34     .04  1836.8    2.94 1853.11     .08
 2310.69    4.03 2500.71    3.53 2527.37    6.27 2578.25    3.64 2642.93    4.99
 2657.85    8.16 2683.59    4.69 2687.32    8.16 2696.36    8.16 2735.08    3.49
 2903.82    3.67 2910.12    -.78 5297.71   -5.34 5893.13   -9.69 8232.37      -1
#Mann= 2 ,-1 , 0
       0     .07       0 2310.69    .025       0
#XS Ineff= 2 ,-1
       0 5492.31       6 6290.52 8232.37       6
Permanent Ineff=
       F       F
Bank Sta=2903.82,8232.37
XS Rating Curve= 0
Exp/Cntr=.5,.3

Chan Stop Cuts=-1